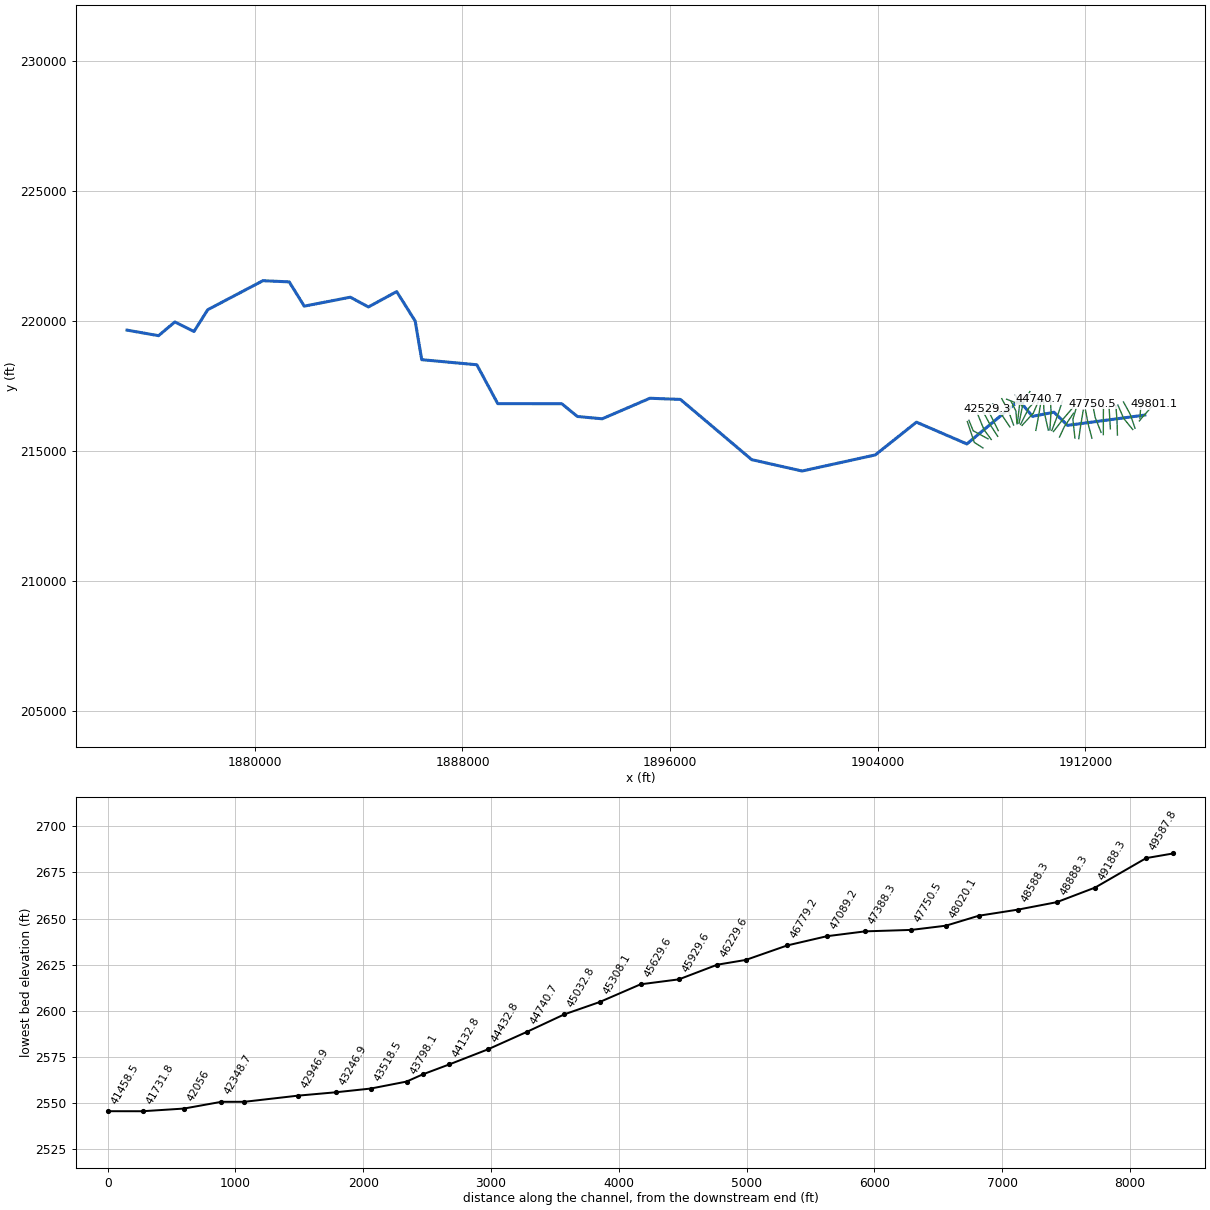
--- TmmyCrk.prj (project) ---

Proj Title=TmmyCrk
Current Plan=p01
Default Exp/Contr=0,0
English Units
Geom File=g01
Flow File=f01
Plan File=p01
BEGIN DESCRIPTION:
END DESCRIPTION:
DSS Export Rating Curves= 0
DSS Export Rating Curve Sorted= 0
DSS Export Volume Flow Curves= 0
DXF OffsetX= 0
DXF OffsetY= 0
DXF ScaleX= 0
DXF ScaleY= 0

--- TmmyCrk.p01 (plan) ---

Plan Title=Floodplain
Program Version=4.00
Geom File=g01
Flow File=f01
K Sum by GR=0
Std Step Tol=0.01
Critical Tol=0.01
Num of Std Step Trials=20
Max Error Tol=0.3
Flow Tol Ratio=0.001
Split Flow NTrial=30
Split Flow Tol=0.02
Split Flow Ratio=0.02
Log Output Level=0
Friction Slope Method=1
Unsteady Friction Slope Method=2
Unsteady Bridges Friction Slope Method=1
Global Log Level=0
CheckData=False
Run HTab=0
Run UNet=0
Run PostProcess=0
UNET Theta=0
UNET Theta Warmup=0
UNET ZTol=0
UNET ZSATol=0
UNET MxIter=0
UNET MaxInSteps=0
UNET DtIC=0
UNET DtMin=0
UNET MaxCRTS=0
UNET WFStab=0
UNET SFStab=0
UNET WFX=0
UNET SFX=0
UNET DSS MLevel=0
UNET DZMax Abort=0
UNET Convert EG Bridges=0
UNET Use Existing IB Tables=0
UNET Froude Limit=0
UNET Froude Power=0
Write IC File=0
Echo Input=False
Echo Output=False
Write Detailed=0

--- TmmyCrk.f01 (steady flow) ---

Flow Title=NFF Regression Equation
Program Version=4.00
Number of Profiles=1
Profile Names=P100yr
River Rch & RM=TmmyCrk,Main      ,49801.1
802.7889
River Rch & RM=TmmyCrk,Main      ,47388.3
888.6882
River Rch & RM=TmmyCrk,Main      ,42529.3
979.3314
River Rch & RM=TmmyCrk,Main      ,42348.7
1157.460
River Rch & RM=TmmyCrk,Main      ,39090.9
1217.335
River Rch & RM=TmmyCrk,Main      ,38773.2
1376.991
River Rch & RM=TmmyCrk,Main      ,36385.6
1474.687
River Rch & RM=TmmyCrk,Main      ,32795.4
1623.489
River Rch & RM=TmmyCrk,Main      ,30988.8
1785.245
River Rch & RM=TmmyCrk,Main      ,26785.5
1900.997
River Rch & RM=TmmyCrk,Main      ,26396.1
2267.950
River Rch & RM=TmmyCrk,Main      ,24842.4
2303.981
River Rch & RM=TmmyCrk,Main      ,22118.7
2536.437
River Rch & RM=TmmyCrk,Main      ,21765.2
2884.038
River Rch & RM=TmmyCrk,Main      ,14938.9
3052.838
River Rch & RM=TmmyCrk,Main      ,6831.1
3390.219
River Rch & RM=TmmyCrk,Main      ,6334.2
3882.676
River Rch & RM=TmmyCrk,Main      ,6198.6
5809.559
River Rch & RM=TmmyCrk,Main      ,242.7
5893.809
Boundary for River Rch & Prof#=TmmyCrk,Main      ,1
Up Type=0
Dn Type=3
Dn Slope=0.01023

--- TmmyCrk.g01 (geometry) ---

Geom Title=USGS 3m DEM
Program Version=4.10

River Reach=TmmyCrk         ,Main
Reach XY= 30
     1914286.082      216379.942     1911311.899      215984.231
     1910788.636      216490.646     1909958.894      216330.453
     1909444.606      216942.632     1907432.324      215270.642
      1905489.39      216107.991     1903903.725      214847.296
     1901083.889      214229.296     1899142.294      214666.108
     1896396.843      216981.423     1895221.844      217026.628
     1893382.211      216236.858     1892425.005      216325.821
     1891823.238      216816.911     1889358.781      216818.308
      1888552.55      218313.685     1886429.377      218509.153
     1886177.878      219993.965     1885464.172      221126.351
     1884375.314      220536.025     1883678.459      220911.192
     1881903.237      220566.886     1881324.753      221500.047
     1880311.362      221545.679     1878184.231      220429.475
     1877654.052      219591.951     1876918.121      219959.305
     1876289.142      219432.439     1875074.879      219646.089

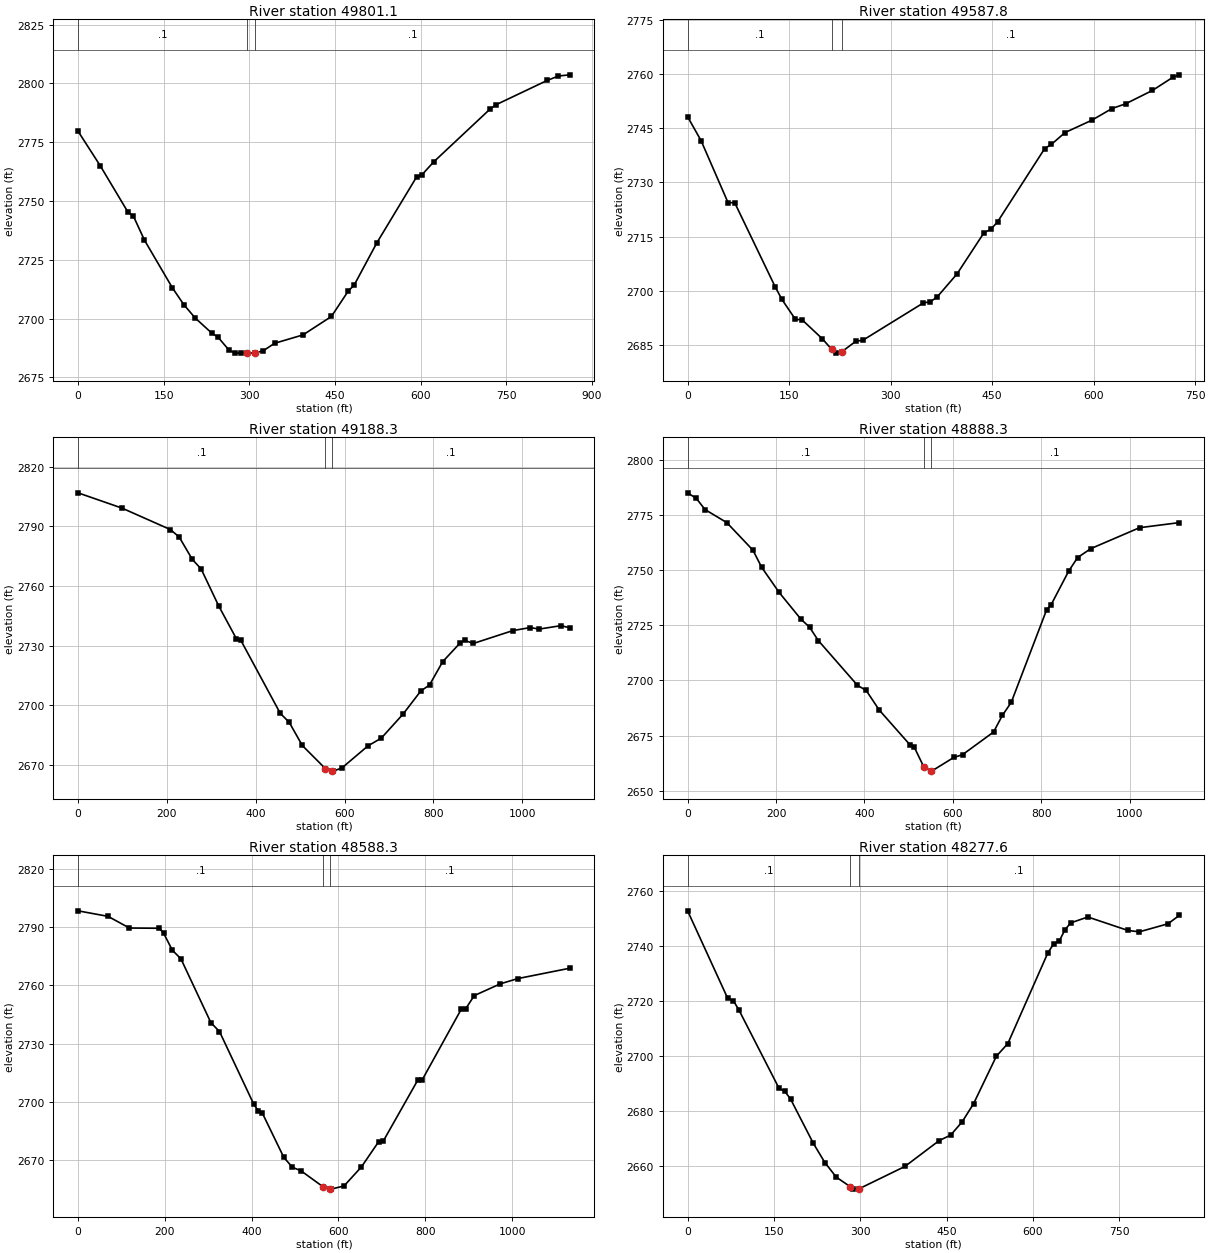
Type RM Length L Ch R = 1 ,49801.1 ,198.3,213.3,227.9
XS GIS Cut Line= 3
     1914078.768      216155.557     1914170.342      216268.678
     1914644.907       216804.64
#Sta/Elev= 30
       0 2779.68    38.8 2765.04    87.3 2745.33      97 2743.58   116.4 2733.34
   165.4 2713.04   185.3 2705.93   205.2 2700.26     235 2693.65     245 2692.16
   264.8 2686.49   274.8 2685.36   284.7  2685.3   295.8  2685.3   310.8 2685.41
   324.5 2686.32   344.4 2689.49   394.1 2693.05   443.8 2700.88   473.6 2711.78
   483.6 2714.18   523.4 2732.18     593 2760.19   602.9 2761.25   622.8 2766.57
   722.2 2789.18   732.2 2790.92   821.6 2801.23   841.5 2803.14   861.4 2803.64
#Mann= 3 , 0 , 0
       0      .1       0   295.8    .045       0   310.8      .1       0
Bank Sta=295.8,310.8
XS Rating Curve= 0 ,0
Exp/Cntr=0.3,0.1

Type RM Length L Ch R = 1 ,49587.8 ,390.2,399.4,412.5
XS GIS Cut Line= 2
     1914098.968      216253.865     1914152.087       216978.75
#Sta/Elev= 30
       0 2748.17    19.9 2741.56    59.7 2724.43    69.7 2724.35   129.4 2701.12
   139.4 2697.61   159.3 2692.11   169.3 2691.97   199.1 2686.73   212.7 2683.86
     219 2682.76   227.7 2683.12   248.9 2686.08   258.9 2686.31   348.5 2696.66
   358.4 2696.96   368.4 2698.21   398.3 2704.71   438.1  2716.1     448 2716.99
     458 2719.06   527.7 2739.36   537.6 2740.52   557.6 2743.77   597.4 2747.21
   627.3 2750.45   647.2 2751.74     687 2755.45   716.9 2759.06   726.8 2759.77
#Mann= 3 , 0 , 0
       0      .1       0   212.7    .045       0   227.7      .1       0
Bank Sta=212.7,227.7
XS Rating Curve= 0 ,0
Exp/Cntr=0.3,0.1

Type RM Length L Ch R = 1 ,49188.3 ,292,300,297.7
XS GIS Cut Line= 3
     1913910.627      215875.942     1913726.757      216409.549
     1913465.783      216885.474
#Sta/Elev= 30
       0 2806.86      99 2799.17   207.9 2788.38   227.7 2784.65   257.4 2773.35
   277.2 2768.55   316.8 2749.93   356.5 2733.46   366.4 2732.72   455.5 2695.83
   475.3 2691.46     505 2679.71   556.9 2668.09   571.9 2666.93   574.3 2666.81
     594 2668.38   653.2 2679.58   682.8  2683.4   732.2 2695.61   771.6 2707.09
   791.4 2710.16     821 2721.87   860.5 2731.35   870.3 2732.62   890.1 2731.06
   978.9 2737.52  1018.4 2739.07  1038.1 2738.28  1087.4 2740.02  1107.2 2738.93
#Mann= 3 , 0 , 0
       0      .1       0   556.9    .045       0   571.9      .1       0
Bank Sta=556.9,571.9
XS Rating Curve= 0 ,0
Exp/Cntr=0.3,0.1

Type RM Length L Ch R = 1 ,48888.3 ,314.1,300,293.4
XS GIS Cut Line= 3
     1913823.287      215824.807     1913479.468      216243.752
     1913249.502      216765.843
#Sta/Elev= 30
       0 2785.06    19.7 2782.55    39.4 2777.48    88.7 2771.56   147.8 2759.06
   167.5 2751.32   206.9 2739.96   256.2 2727.82   275.9 2724.14   295.6 2718.11
   384.3 2697.79     404 2695.47   433.6 2686.57   502.6 2670.93   512.4  2669.9
   534.5 2660.75   549.5 2658.92     552  2658.9     602 2665.08     622 2666.37
   692.1 2676.61   712.1 2684.18   732.1 2690.06   812.2 2732.05   822.2 2734.28
   862.2 2749.62   882.3 2755.72   912.3 2759.78  1022.4 2769.25  1112.5 2771.56
#Mann= 3 , 0 , 0
       0      .1       0   534.5    .045       0   549.5      .1       0
Bank Sta=534.5,549.5
XS Rating Curve= 0 ,0
Exp/Cntr=0.3,0.1

Type RM Length L Ch R = 1 ,48588.3 ,309.8,310.7,310.4
XS GIS Cut Line= 3
     1913233.719      215611.291     1913217.088      216183.846
     1913172.665      216742.035
#Sta/Elev= 30
       0 2798.45    69.1  2795.6   118.5 2789.58   187.6 2789.45   197.5 2786.79
   217.3 2778.12     237 2773.73   306.2 2740.72   325.9 2736.19   404.9 2698.68
   414.8 2695.41   424.7 2694.08     474 2671.31   493.8 2666.17   513.5 2664.39
   565.3 2655.98   580.3 2654.97   582.8 2654.91   612.8 2656.55   652.8 2666.36
   692.8 2679.46   702.8 2679.54   782.8  2711.2   792.8 2711.25   882.8  2747.7
   892.8 2747.88   912.8 2754.73   972.8 2760.79  1012.8 2763.49  1132.8 2768.85
#Mann= 3 , 0 , 0
       0      .1       0   565.3    .045       0   580.3      .1       0
Bank Sta=565.3,580.3
XS Rating Curve= 0 ,0
Exp/Cntr=0.3,0.1

Type RM Length L Ch R = 1 ,48277.6 ,260.1,257.5,255
XS GIS Cut Line= 2
     1912961.027      215851.433     1912910.909      216704.228
#Sta/Elev= 30
       0 2752.68    69.5 2720.95    79.5 2720.03    89.4 2716.54   158.9 2688.16
   168.9 2687.06   178.8  2684.3   218.5 2668.16   238.4 2661.22   258.3  2655.9
   282.2 2652.49   288.1 2651.55   297.2 2651.61   377.5 2659.79   437.1  2669.2
   456.9 2671.17   476.8 2675.96   496.7 2682.57   536.4 2699.86   556.3 2704.45
   625.8  2737.4   635.7 2740.58   645.7 2741.74   655.6 2745.82   665.5  2748.3
   695.3 2750.44   764.9 2745.55   784.7 2745.05   834.4 2747.96   854.3 2751.04
#Mann= 3 , 0 , 0
       0      .1       0   282.2    .045       0   297.2      .1       0
Bank Sta=282.2,297.2
XS Rating Curve= 0 ,0
Exp/Cntr=0.3,0.1

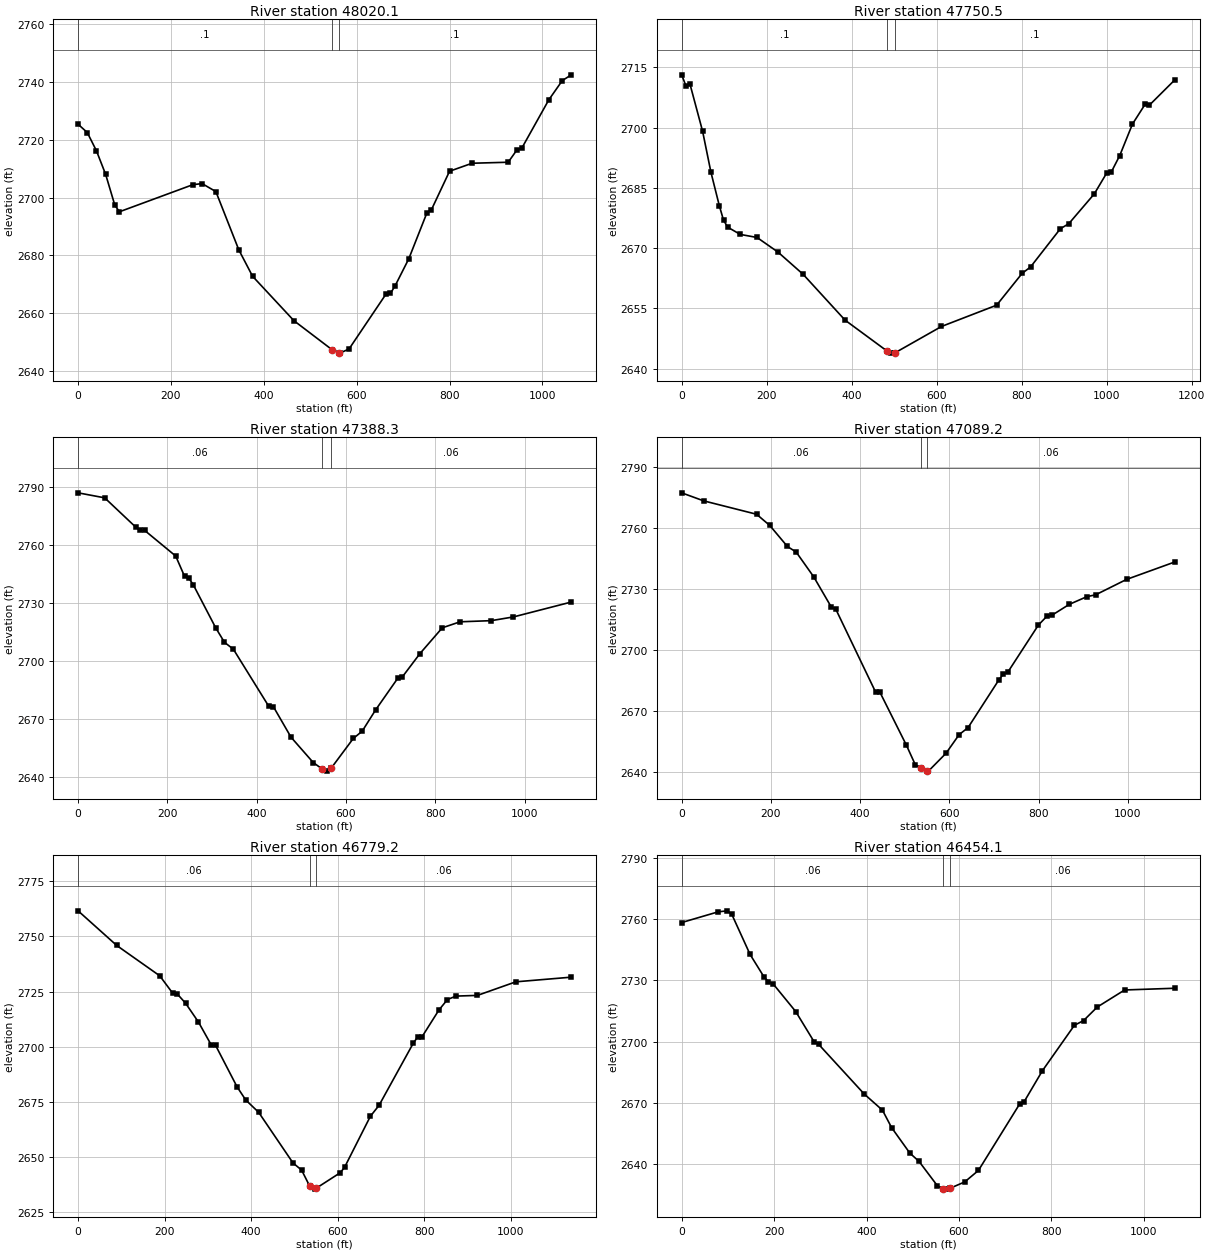
Type RM Length L Ch R = 1 ,48020.1 ,260.9,269.4,277.9
XS GIS Cut Line= 3
     1912690.565      215629.311     1912691.692      216361.374
     1912695.283      216691.759
#Sta/Elev= 30
       0 2725.43    19.8 2722.56    39.6 2716.21    59.4 2708.05    79.1 2697.42
      89 2695.11   247.3  2704.5   267.1 2704.87   296.8  2702.1   346.2 2681.92
   375.9 2672.77     465 2657.38   546.9 2647.36   561.9 2646.21   563.9 2646.16
   583.7 2647.61   662.8 2666.51   672.7 2666.83   682.6 2669.39   712.3 2678.83
   751.5  2694.8   761.2 2695.86   800.1 2709.15   848.7 2711.92   926.4 2712.27
   945.8 2716.67   955.6 2717.11  1013.9 2733.88    1043 2740.56  1062.5 2742.54
#Mann= 3 , 0 , 0
       0      .1       0   546.9    .045       0   561.9      .1       0
Bank Sta=546.9,561.9
XS Rating Curve= 0 ,0
Exp/Cntr=0.3,0.1

Type RM Length L Ch R = 1 ,47750.5 ,365,362.3,358.3
XS GIS Cut Line= 3
     1912603.142      215714.916     1912377.635       216283.02
     1912275.251      216822.678
#Sta/Elev= 30
       0 2713.16     9.9 2710.47    19.7 2710.82    49.3 2699.12      69 2688.88
    88.7 2680.56    98.6 2676.96   108.4 2675.23     138 2673.43   177.4 2672.67
   226.7 2669.03   285.9 2663.49   384.5 2652.09   483.1 2644.41   492.9 2643.88
   502.8 2644.01   611.2 2650.51   741.1 2655.82     801 2663.73     821 2665.35
   890.9 2674.84   910.8  2676.1   970.8 2683.52  1000.7 2688.84  1010.7 2688.94
  1030.7 2693.07  1060.6  2700.9  1090.6 2705.87  1100.6 2705.63  1160.5 2711.93
#Mann= 3 , 0 , 0
       0      .1       0   483.1    .045       0   502.8      .1       0
Bank Sta=483.1,502.8
XS Rating Curve= 0 ,0
Exp/Cntr=0.3,0.1

Type RM Length L Ch R = 1 ,47388.3 ,308,298.8,290.4
XS GIS Cut Line= 3
     1912249.704       215489.97     1912111.424      216018.578
     1912002.465      216565.901
#Sta/Elev= 30
       0 2786.76    59.6 2784.17   129.2 2769.03   139.1 2767.39     149 2767.37
   218.6 2754.12   238.4 2743.65   248.4 2742.59   258.3 2739.13     308 2717.13
   327.8 2709.58   347.7 2706.02   427.2 2676.46   437.1 2676.43   476.8  2660.6
   526.5 2647.53   546.4 2644.22   556.4 2643.09   566.3  2644.5   616.2 2659.95
   636.1  2663.7     666 2674.63   715.8 2691.04   725.8 2691.66   765.6 2703.81
   815.5 2717.08   855.3 2720.18   925.1 2720.77   974.9  2722.7  1104.5 2730.39
#Mann= 3 , 0 , 0
       0     .06       0   546.4    .045       0   566.3     .06       0
Bank Sta=546.4,566.3
XS Rating Curve= 0 ,0
Exp/Cntr=0.3,0.1

Type RM Length L Ch R = 1 ,47089.2 ,304,309.9,315.8
XS GIS Cut Line= 3
     1911744.192      215472.701     1911822.584      216010.144
     1911916.634      216564.484
#Sta/Elev= 30
       0 2777.29    49.4 2773.34   167.9 2766.76   197.5 2761.25     237 2750.92
   256.8 2748.14   296.2 2735.92   335.8 2720.97   345.6 2720.03   434.5  2679.4
   444.4 2679.23   503.6 2653.26   523.4 2643.71   535.6 2642.02   550.6 2640.51
     553 2640.47   592.4 2649.24     622 2658.45   641.8 2661.85   710.8 2685.29
   720.7 2688.14   730.6 2689.01   799.6 2712.33   819.3  2716.8   829.2 2717.03
   868.6 2722.45   908.1 2726.24   927.8 2727.16   996.9 2734.71  1105.4 2743.32
#Mann= 3 , 0 , 0
       0     .06       0   535.6    .045       0   550.6     .06       0
Bank Sta=535.6,550.6
XS Rating Curve= 0 ,0
Exp/Cntr=0.3,0.1

Type RM Length L Ch R = 1 ,46779.2 ,342.4,325.1,305.4
XS GIS Cut Line= 3
      1911595.48      215496.411     1911517.391      216217.729
     1911635.959      216615.284
#Sta/Elev= 30
       0 2761.56    89.4 2745.86   188.8 2732.12   218.6 2724.28   228.6 2724.05
   248.5 2719.71   278.3 2711.17   308.1 2700.72     318 2700.57   367.7 2681.77
   387.6 2675.87   417.4  2670.3   496.9 2647.34   516.8  2644.1   535.3  2636.9
   546.6 2635.49   550.3 2635.87   606.3 2642.95   616.2 2645.42   675.8 2668.51
   695.7 2673.42   774.9 2701.58   784.8 2704.37   794.7 2704.36   834.2 2716.63
   853.9 2721.37   873.7 2722.94   923.1 2723.24    1012  2729.4  1140.4 2731.51
#Mann= 3 , 0 , 0
       0     .06       0   535.3    .045       0   550.3     .06       0
Bank Sta=535.3,550.3
XS Rating Curve= 0 ,0
Exp/Cntr=0.3,0.1

Type RM Length L Ch R = 1 ,46454.1 ,223.6,223.2,221.6
XS GIS Cut Line= 3
     1911000.893      215533.681     1911184.313       215927.52
     1911541.182      216450.031
#Sta/Elev= 30
       0 2758.33      79 2763.58    98.7 2764.08   108.6 2762.32   148.1 2742.68
   177.7 2731.86   187.6 2729.28   197.5 2728.38   246.8  2714.7   286.4 2699.95
   296.2 2698.66     395 2674.26   434.5 2666.32   454.2  2657.8   493.8 2645.26
   513.6 2641.22   553.1 2629.33   565.7 2627.66   572.9 2627.62   580.7 2628.04
   612.4 2631.15   642.1 2636.78   731.1  2669.3   740.9 2670.45   780.5 2685.67
   849.7 2707.95   869.5 2710.25   899.1 2716.89   958.4 2725.27  1067.2 2726.12
#Mann= 3 , 0 , 0
       0     .06       0   565.7    .045       0   580.7     .06       0
Bank Sta=565.7,580.7
XS Rating Curve= 0 ,0
Exp/Cntr=0.3,0.1

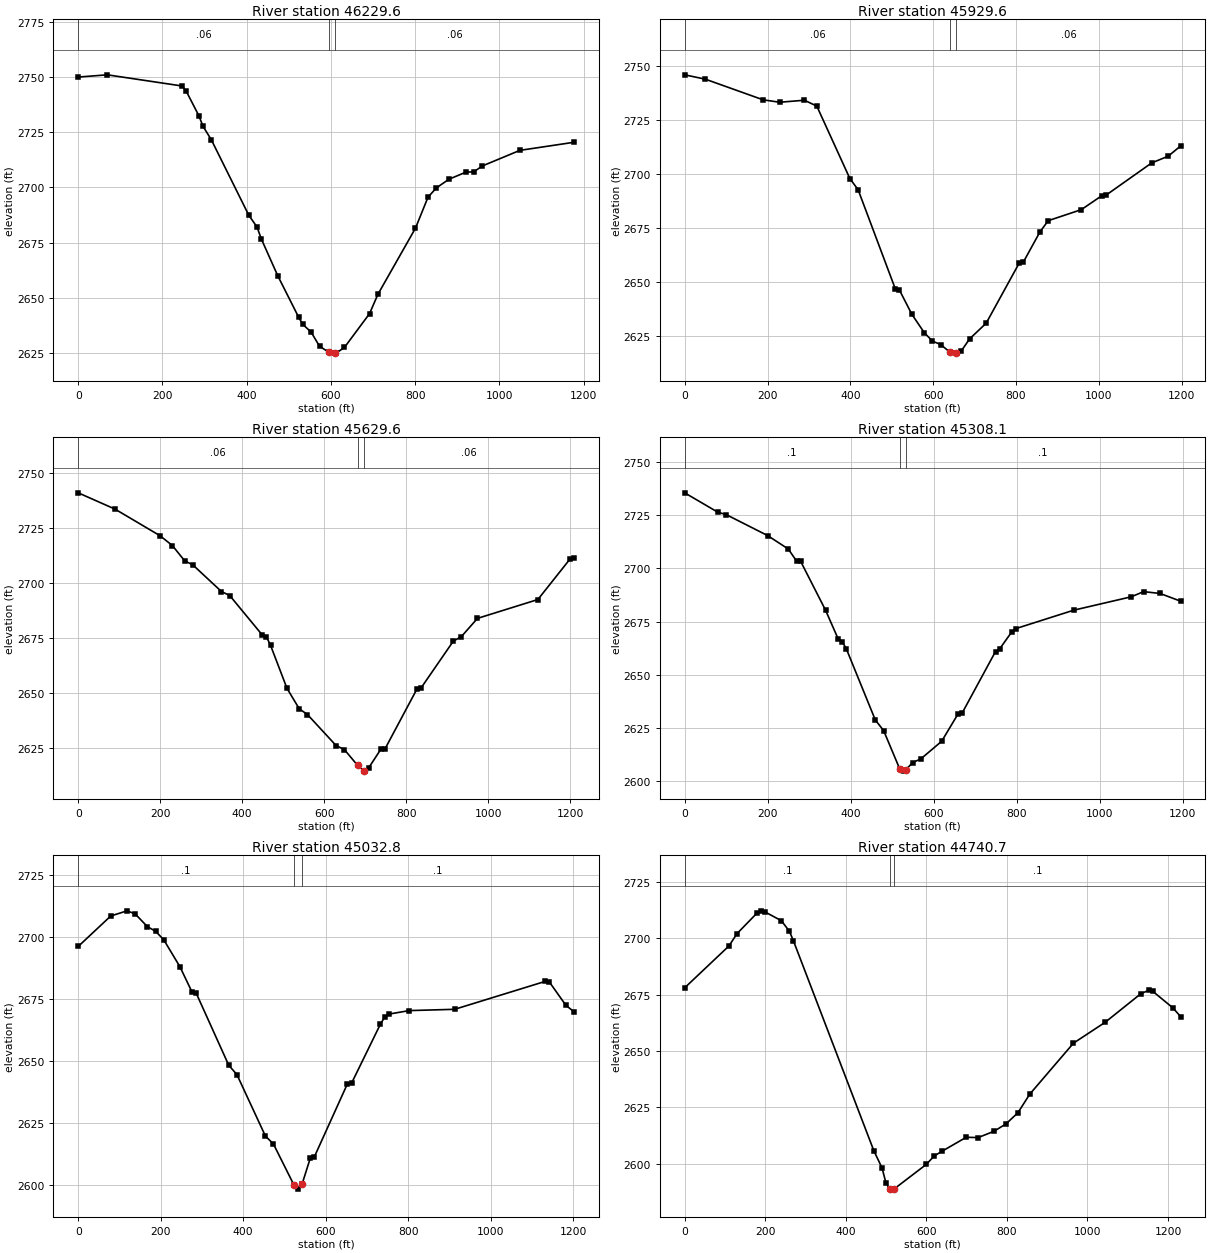
Type RM Length L Ch R = 1 ,46229.6 ,294.3,300.5,308.9
XS GIS Cut Line= 3
     1910768.841      215747.613     1911138.871      216222.936
     1911510.549      216661.614
#Sta/Elev= 30
       0 2749.96    69.1 2750.97   246.9 2745.91   256.8 2743.43   286.4 2732.47
   296.2  2727.7     316 2721.58   404.9 2687.45   424.6 2682.07   434.5 2676.78
     474 2659.93   523.4 2641.24   533.2 2638.04     553 2634.53   572.8 2628.16
   594.9 2625.45   609.9 2625.05   612.3 2625.04   632.1 2627.64   691.6 2642.92
   711.4 2651.63   800.6 2681.58   830.4 2695.61   850.2 2699.81   879.9  2703.7
   919.6 2706.88   939.4 2707.12   959.2 2709.72  1048.5 2716.79  1177.3 2720.46
#Mann= 3 , 0 , 0
       0     .06       0   594.9    .045       0   609.9     .06       0
Bank Sta=594.9,609.9
XS Rating Curve= 0 ,0
Exp/Cntr=0.3,0.1

Type RM Length L Ch R = 1 ,45929.6 ,293.3,299.9,307.8
XS GIS Cut Line= 3
     1910706.087       215787.96     1910939.018      216392.686
     1911112.573      216913.833
#Sta/Elev= 30
       0 2746.13    49.8 2744.12   189.4 2734.54   229.3 2733.42   289.1 2734.35
     319 2731.63   398.8 2698.03   418.7 2692.86   508.5 2646.88   518.4 2646.37
   548.3 2635.15   578.2 2626.64   598.2 2622.65   618.1 2621.09   640.5 2617.51
   655.5 2617.11     658  2617.1     668 2618.17     688 2623.73   727.9 2630.99
   807.8 2658.91   817.8 2659.37   857.8 2673.34   877.7 2678.51   957.6 2683.63
  1007.6 2690.16  1017.6 2690.39  1127.4 2705.28  1167.4 2708.42  1197.3 2713.15
#Mann= 3 , 0 , 0
       0     .06       0   640.5    .045       0   655.5     .06       0
Bank Sta=640.5,655.5
XS Rating Curve= 0 ,0
Exp/Cntr=0.3,0.1

Type RM Length L Ch R = 1 ,45629.6 ,315.1,321.3,325.1
XS GIS Cut Line= 3
     1910630.605      215807.235     1910675.097      216494.808
     1910651.991      217015.058
#Sta/Elev= 30
       0 2740.84    89.9 2733.43   199.7 2721.34   229.7 2716.89   259.6 2709.97
   279.6  2708.1   349.5 2695.99   369.5  2694.2   449.4 2676.17   459.3 2675.38
   469.3  2671.5   509.3 2652.02   539.2 2642.73   559.2 2640.13   629.1 2626.02
   649.1 2624.24   681.5 2617.05   696.5 2614.59   698.8 2614.42   708.7 2615.95
   738.1 2624.31     748 2624.38   826.6 2651.82   836.4 2652.22     915 2673.46
   934.6 2675.52     974 2683.81  1121.3 2692.37    1200 2710.84  1209.8 2711.13
#Mann= 3 , 0 , 0
       0     .06       0   681.5    .045       0   696.5     .06       0
Bank Sta=681.5,696.5
XS Rating Curve= 0 ,0
Exp/Cntr=0.3,0.1

Type RM Length L Ch R = 1 ,45308.1 ,284.8,275.3,266.2
XS GIS Cut Line= 3
     1910569.358      215799.905     1910402.838      216540.616
     1910382.793      216976.343
#Sta/Elev= 30
       0 2735.55    79.9 2726.44    99.9 2725.34   199.8 2715.48   249.7 2709.16
   269.7 2703.48   279.7  2703.3   339.6 2680.38   369.6 2667.07   379.6 2665.66
   389.6 2662.28   459.5 2628.81   479.5 2623.86     518 2605.98   529.4 2604.79
     533 2605.44   549.4 2608.78   569.4 2610.57   619.4  2618.8   659.3  2631.8
   669.3 2632.26   749.2 2660.98   759.2 2662.22   788.9 2670.34   798.8 2671.79
   937.6  2680.4  1076.4  2686.7  1106.2 2689.12  1145.8 2688.27  1195.4 2684.64
#Mann= 3 , 0 , 0
       0      .1       0     518    .045       0     533      .1       0
Bank Sta=518,533
XS Rating Curve= 0 ,0
Exp/Cntr=0.3,0.1

Type RM Length L Ch R = 1 ,45032.8 ,304.8,292,278.8
XS GIS Cut Line= 3
     1910090.174      215791.514     1910188.341      216305.085
     1910302.951      216975.017
#Sta/Elev= 30
       0 2696.25    78.9 2708.56   118.4 2710.65   138.1 2709.41   167.7 2704.26
   187.4 2702.41   207.2    2699   246.6 2688.06   276.2 2677.73   286.1 2677.36
     365 2648.22   384.8 2644.45   453.8 2619.64   473.5 2616.35   522.9 2599.88
   532.9 2598.15   542.9 2600.24   562.8 2610.73   572.8 2611.28   652.8 2640.74
   662.8 2640.97   732.8 2664.86   742.8 2667.59   752.8 2668.89   802.7 2670.32
   912.7 2670.84  1132.6 2682.14  1142.6 2681.84  1182.5 2672.45  1202.5  2669.8
#Mann= 3 , 0 , 0
       0      .1       0   522.9    .045       0   542.9      .1       0
Bank Sta=522.9,542.9
XS Rating Curve= 0 ,0
Exp/Cntr=0.3,0.1

Type RM Length L Ch R = 1 ,44740.7 ,301.7,308,308
XS GIS Cut Line= 3
     1909558.328      215982.183     1909991.551      216453.042
       1910226.8      216995.625
#Sta/Elev= 30
       0 2678.07     110 2696.67     130 2702.14     180 2711.34     190 2712.25
     200  2711.7   239.9 2707.88   259.9  2703.2   269.9 2698.97   469.9  2605.6
   489.9 2598.14   499.9 2591.31   509.9  2588.7   519.9 2588.77   599.8 2599.68
   619.8 2603.47   639.8 2605.61     699 2611.72   728.5 2611.58     768 2614.39
   797.5 2617.64   827.1 2622.56   856.7 2630.86   965.1 2653.49    1044 2662.78
  1132.7 2675.49  1152.4 2676.97  1162.2  2676.5  1211.5 2669.24  1231.2 2665.32
#Mann= 3 , 0 , 0
       0      .1       0   509.9    .045       0   519.9      .1       0
Bank Sta=509.9,519.9
XS Rating Curve= 0 ,0
Exp/Cntr=0.3,0.1

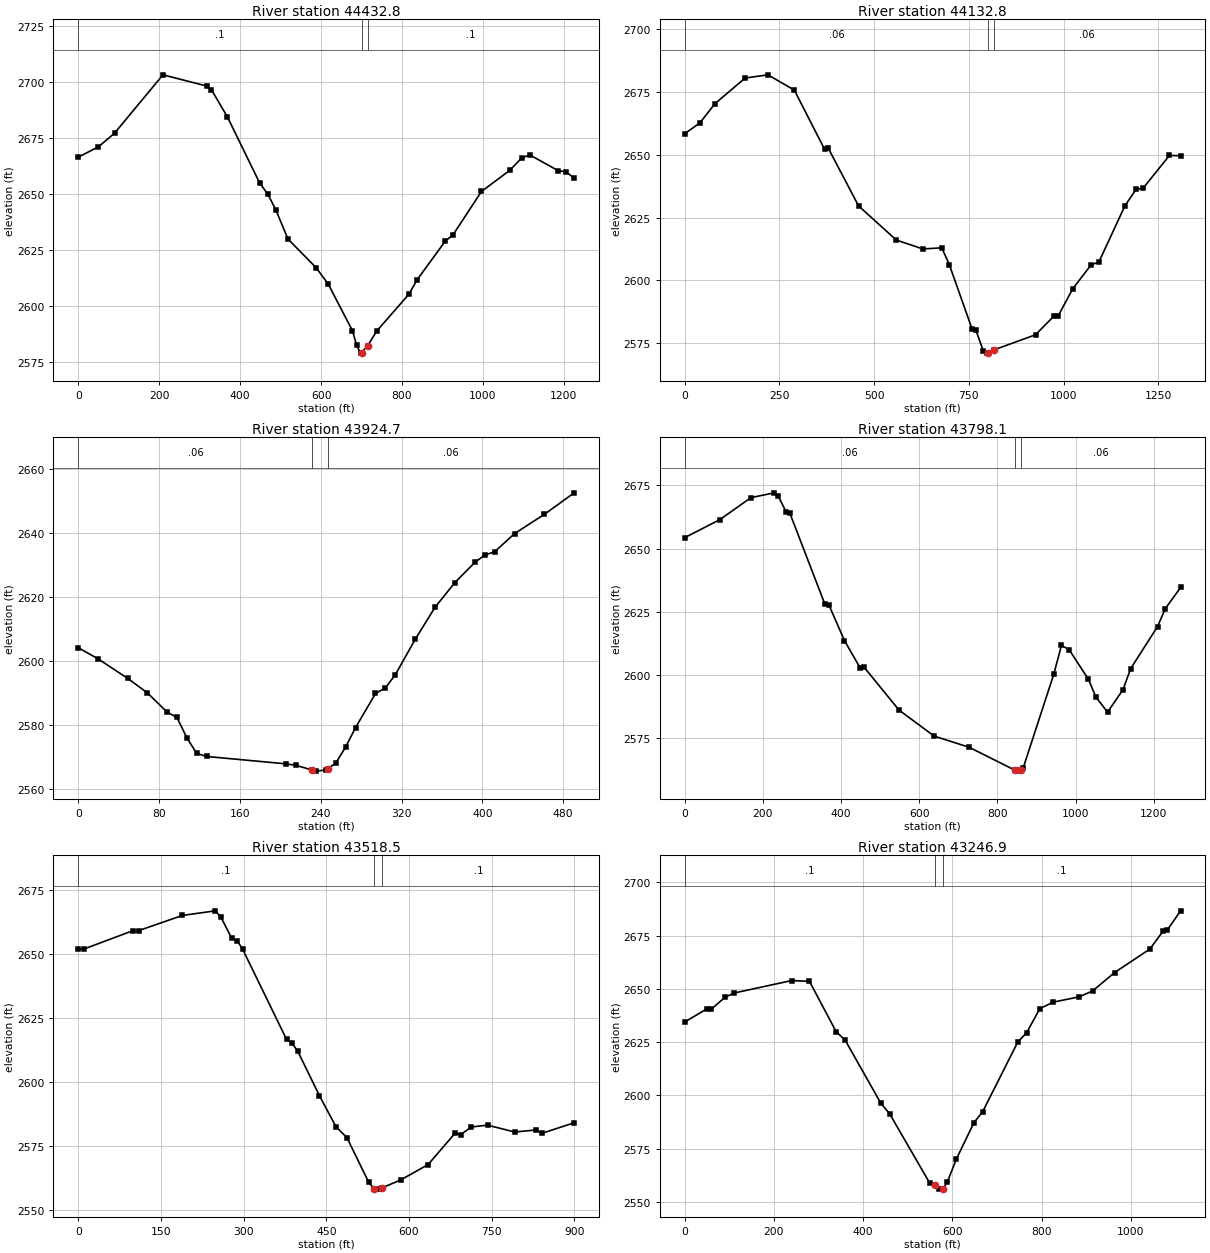
Type RM Length L Ch R = 1 ,44432.8 ,293.6,299.7,304.5
XS GIS Cut Line= 3
      1909501.79       216021.06     1909820.332      216652.791
     1910169.387      217035.122
#Sta/Elev= 30
       0 2666.55    49.8 2671.15    89.7 2677.24   209.3 2703.29   318.9 2698.23
   328.8 2696.72   368.7 2684.48   448.4 2654.97   468.3  2650.1   488.3 2643.03
   518.2 2630.04   587.9 2617.23   617.8 2609.89   677.6  2589.1   687.6 2582.75
   697.5 2579.14     700 2579.42     715 2582.41   737.4 2588.97     817 2605.43
   836.9 2611.78   906.6 2629.04   926.5 2632.05   996.2 2651.25  1065.9 2660.65
  1095.8 2666.23  1115.7 2667.56  1185.4 2660.56  1205.3 2660.03  1225.2 2657.17
#Mann= 3 , 0 , 0
       0      .1       0     700    .045       0     715      .1       0
Bank Sta=700,715
XS Rating Curve= 0 ,0
Exp/Cntr=0.3,0.1

Type RM Length L Ch R = 1 ,44132.8 ,191.9,208.3,232.2
XS GIS Cut Line= 3
     1909439.679        216061.4     1909601.316      216853.115
     1909860.212      217281.627
#Sta/Elev= 30
       0 2658.42    39.9 2662.67    79.8 2670.36   159.6 2680.57   219.5 2681.85
   289.3 2675.78   369.1 2652.24   379.1  2652.6   458.9 2629.65   558.6 2616.07
   628.5 2612.54   678.4 2612.98   698.3  2606.3   758.2 2580.76   768.1 2580.36
   788.1 2571.85   798.1 2571.06   800.5 2571.17   815.5 2572.32   925.8 2578.37
   974.9 2585.89   984.8 2585.65    1024 2596.65  1073.1 2606.32  1092.7 2607.21
  1161.4 2629.62  1190.9  2636.2  1210.5 2636.86  1279.2 2649.74  1308.7 2649.66
#Mann= 3 , 0 , 0
       0     .06       0   800.5    .045       0   815.5     .06       0
Bank Sta=800.5,815.5
XS Rating Curve= 0 ,0
Exp/Cntr=0.3,0.1

Type RM Length L Ch R = 1 ,43924.7 ,111.6,126.6,141.5
XS GIS Cut Line= 3
     1909550.795      216732.833     1909479.421      216837.873
      1909297.62      217152.995
#Sta/Elev= 30
       0  2604.2    19.5 2600.74    48.8 2594.65    68.4  2590.1    87.9  2584.1
    97.7 2582.43   107.5 2576.07   117.2  2571.2     127 2570.23   205.7 2567.92
   215.5 2567.45   231.8 2565.97   235.2 2565.65     245 2565.99   246.8 2566.38
   254.8 2568.11   264.6 2573.17   274.5 2579.26   294.2 2589.89     304 2591.63
   313.8 2595.74   333.5  2606.8   353.1  2616.8   372.8 2624.54   392.5 2630.82
   402.3 2633.12   412.1 2634.14   431.8 2639.82   461.3 2645.82   490.8 2652.55
#Mann= 3 , 0 , 0
       0     .06       0   231.8    .045       0   246.8     .06       0
Bank Sta=231.8,246.8
XS Rating Curve= 0 ,0
Exp/Cntr=0.3,0.1

Type RM Length L Ch R = 1 ,43798.1 ,295.7,279.6,263.4
XS GIS Cut Line= 3
     1909379.443      216067.845     1909464.608       216790.74
     1908962.298      216991.394
#Sta/Elev= 30
       0 2654.31    89.7 2661.43   169.5 2670.17   229.3 2672.08   239.3  2670.8
   259.2 2664.61   269.2 2663.96     359 2627.82   368.9 2627.66   408.8 2613.49
   448.7 2602.73   458.7 2603.01   548.4 2585.94   638.2 2575.65   727.9  2571.2
     845 2562.11   855.7 2561.75     860 2562.21   865.6 2562.81   944.3 2600.17
   963.9 2611.59   983.6 2609.89  1032.8 2598.19  1052.4 2591.03  1081.9 2585.14
  1121.3 2594.02    1141 2602.38  1209.8 2619.08  1229.5 2626.15  1268.8 2634.56
#Mann= 3 , 0 , 0
       0     .06       0     845    .045       0     860     .06       0
Bank Sta=845,860
XS Rating Curve= 0 ,0
Exp/Cntr=0.3,0.1

Type RM Length L Ch R = 1 ,43518.5 ,274.3,271.6,272.2
XS GIS Cut Line= 3
     1909364.158      216043.607     1909320.513      216538.911
     1909137.366      216897.127
#Sta/Elev= 30
       0 2651.77     9.9 2651.78    99.4 2659.01   109.4    2659   188.9 2664.94
   248.6 2666.75   258.6 2664.36   278.4 2656.03   288.4 2654.99   298.3 2651.72
   377.9 2616.49   387.8 2614.98   397.8 2612.04   437.6 2594.48   467.4 2582.39
   487.3 2578.13   526.7 2560.74   536.7 2558.07   546.3 2557.98   551.7 2558.53
   585.5 2561.64   634.6 2567.58   683.7 2579.88   693.5 2579.28   713.1 2582.28
   742.5 2582.98   791.6  2580.3   830.8 2581.11   840.7 2579.76   899.5 2583.92
#Mann= 3 , 0 , 0
       0      .1       0   536.7    .045       0   551.7      .1       0
Bank Sta=536.7,551.7
XS Rating Curve= 0 ,0
Exp/Cntr=0.3,0.1

Type RM Length L Ch R = 1 ,43246.9 ,294.5,300,304.3
XS GIS Cut Line= 3
     1909231.933       215998.22     1909035.957      216532.504
     1908777.555      217009.279
#Sta/Elev= 30
       0 2634.46    49.9 2640.65    59.9 2640.54    89.9 2645.99   109.8 2648.03
   239.6 2653.92   279.6 2653.57   339.5  2629.9   359.4 2626.02   439.3 2596.41
   459.3 2591.37   549.1 2558.83   561.6 2557.85   569.1 2556.03     579 2555.97
   588.8  2559.4   608.5 2569.93     648 2587.12   667.7 2592.32   746.6 2625.09
   766.3 2629.44   795.9 2640.71   825.4 2643.76   884.6 2646.32   914.2 2649.05
   963.5 2657.71  1042.4 2668.72    1072 2677.09  1081.8 2677.78  1111.4 2686.68
#Mann= 3 , 0 , 0
       0      .1       0   561.6    .045       0     579      .1       0
Bank Sta=561.6,579
XS Rating Curve= 0 ,0
Exp/Cntr=0.3,0.1

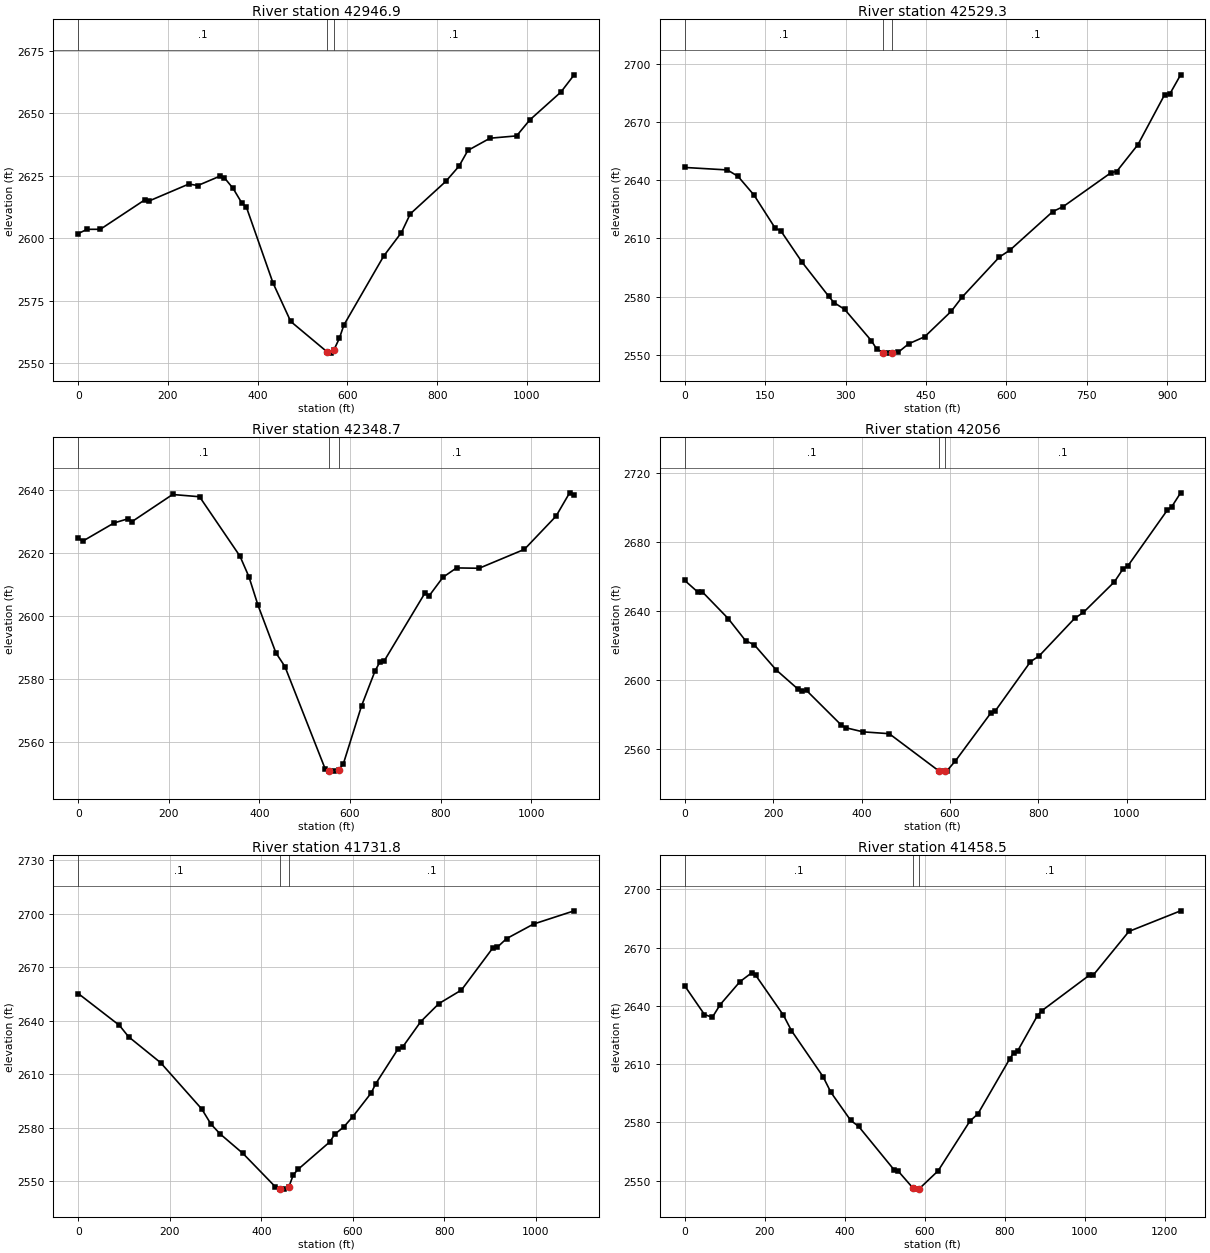
Type RM Length L Ch R = 1 ,42946.9 ,420.7,417.5,412.1
XS GIS Cut Line= 3
     1909090.859      215922.378     1908776.996       216388.99
     1908432.586      216808.654
#Sta/Elev= 30
       0 2601.93    19.7 2603.63    49.3 2603.65     148 2615.37   157.8 2614.96
   246.6 2621.75   266.4 2621.14   315.7 2624.89   325.6 2624.28   345.3 2619.96
     365 2614.04   374.9 2612.46   434.1 2582.18   473.6 2566.78   554.8  2554.6
   562.4 2554.12   569.8  2555.4   582.1  2560.1     592 2565.34   680.8 2592.94
   720.3 2602.35     740 2609.81     819 2622.78   848.6 2628.88   868.4 2635.19
   917.7 2640.07   976.9    2641  1006.5 2647.41  1075.6 2658.51  1105.2 2665.42
#Mann= 3 , 0 , 0
       0      .1       0   554.8    .045       0   569.8      .1       0
Bank Sta=554.8,569.8
XS Rating Curve= 0 ,0
Exp/Cntr=0.3,0.1

Type RM Length L Ch R = 1 ,42529.3 ,178,180.5,181.2
XS GIS Cut Line= 2
     1908641.639      215782.154     1908229.743       216610.18
#Sta/Elev= 30
       0 2646.59    79.6  2645.3    99.4 2642.01   129.3 2632.33     169 2615.17
     179    2614   218.8 2597.76   268.5 2580.13   278.4 2576.88   298.3 2573.37
     348 2557.25     358 2552.96   370.7 2550.97   377.9  2550.8   385.7  2550.8
   397.8 2551.16   417.7 2555.62   447.5 2559.24   497.2 2572.43   517.1 2579.62
   586.7 2600.34   606.6 2603.95   686.2 2623.78     706 2626.42   795.5 2643.98
   805.5 2644.49   845.3  2658.4     895 2684.13   904.9  2684.6   924.8 2694.37
#Mann= 3 , 0 , 0
       0      .1       0   370.7    .045       0   385.7      .1       0
Bank Sta=370.7,385.7
XS Rating Curve= 0 ,0
Exp/Cntr=0.3,0.1

Type RM Length L Ch R = 1 ,42348.7 ,297,292.8,290.4
XS GIS Cut Line= 3
      1908621.03      215562.973     1908323.409      216020.062
     1908062.134      216503.079
#Sta/Elev= 30
       0 2624.78     9.9 2623.71    79.3  2629.5   109.1 2630.77     119 2629.94
   208.3 2638.51   267.8  2637.8     357 2618.96   376.8 2612.42   396.7 2603.44
   436.4 2588.28   456.2 2583.96   545.4 2551.38   552.9 2550.96   565.4 2550.79
   575.4  2551.1   585.4  2553.2   625.3 2571.47   655.3 2582.61   665.3 2585.26
   675.2  2585.7   765.1 2607.22   775.1 2606.48     805 2612.26     835 2615.23
   884.9 2615.12   984.8 2621.12  1054.7 2631.66  1084.6 2639.04  1094.6 2638.31
#Mann= 3 , 0 , 0
       0      .1       0   552.9    .045       0   575.4      .1       0
Bank Sta=552.9,575.4
XS Rating Curve= 0 ,0
Exp/Cntr=0.3,0.1

Type RM Length L Ch R = 1 ,42056   ,308.7,324.1,339.5
XS GIS Cut Line= 3
     1908371.585      215440.824     1908095.946      215812.273
     1907845.745      216422.077
#Sta/Elev= 30
       0 2657.87    29.5 2651.14    39.4 2651.36    98.4 2635.72   137.8 2622.85
   157.5 2620.46   206.7 2605.96   255.9 2594.84   265.7 2593.43   275.6 2593.96
   354.3 2573.85   364.1 2572.34   403.5 2569.94   462.6 2568.88   574.2 2547.39
   589.2 2547.15   592.4 2547.14   612.4 2553.08   692.2  2580.8   702.2 2581.98
   782.1 2610.65   802.1 2614.12     882 2635.82     902 2639.32   971.9 2657.02
   991.9 2664.71  1001.8 2666.06  1091.7 2698.71  1101.7 2700.66  1121.7 2708.71
#Mann= 3 , 0 , 0
       0      .1       0   574.2    .045       0   589.2      .1       0
Bank Sta=574.2,589.2
XS Rating Curve= 0 ,0
Exp/Cntr=0.3,0.1

Type RM Length L Ch R = 1 ,41731.8 ,290.2,273.2,256.2
XS GIS Cut Line= 3
     1908246.614      215466.134     1907675.624      215776.768
     1907512.466      216178.403
#Sta/Elev= 30
       0  2655.4      90 2637.54     110 2631.15     180 2616.61     270 2590.59
     290 2582.16     310 2576.65     360 2565.68     430 2547.16     440  2545.8
     450 2545.69     460 2546.83     470 2553.73     480 2556.71     550 2572.26
     560 2576.38     580  2580.5     600 2586.38     640  2599.6     650 2604.79
   699.3 2624.53   709.1 2625.49   748.5 2639.67     788 2649.74   837.2 2657.34
   906.2 2681.08     916 2681.45   935.7 2686.16   994.9 2694.36  1083.5 2701.77
#Mann= 3 , 0 , 0
       0      .1       0     440    .045       0     460      .1       0
Bank Sta=440,460
XS Rating Curve= 0 ,0
Exp/Cntr=0.3,0.1

Type RM Length L Ch R = 1 ,41458.5 ,277.1,278.9,280.7
XS GIS Cut Line= 3
     1908051.415      215116.606     1907718.732      215329.501
     1907450.293      216129.865
#Sta/Elev= 30
       0 2650.34    49.4 2635.54    69.1  2634.1    88.9 2640.67   138.2 2652.46
   167.9 2657.06   177.7 2655.67   246.9 2635.14   266.6 2627.32   345.6 2603.63
   365.4  2595.5   414.8 2581.08   434.7 2577.96   524.1 2555.42     534 2554.87
   571.3 2546.05   583.7 2545.71   586.3 2545.94   633.3 2555.14   712.8 2580.74
   732.6  2584.4   812.1  2612.7     822 2615.87     832 2616.82   881.6 2635.03
   891.6 2637.37  1010.7 2655.69  1020.7 2655.76    1110 2678.29  1239.2 2688.89
#Mann= 3 , 0 , 0
       0      .1       0   571.3    .045       0   586.3      .1       0
Bank Sta=571.3,586.3
XS Rating Curve= 0 ,0
Exp/Cntr=0.3,0.1