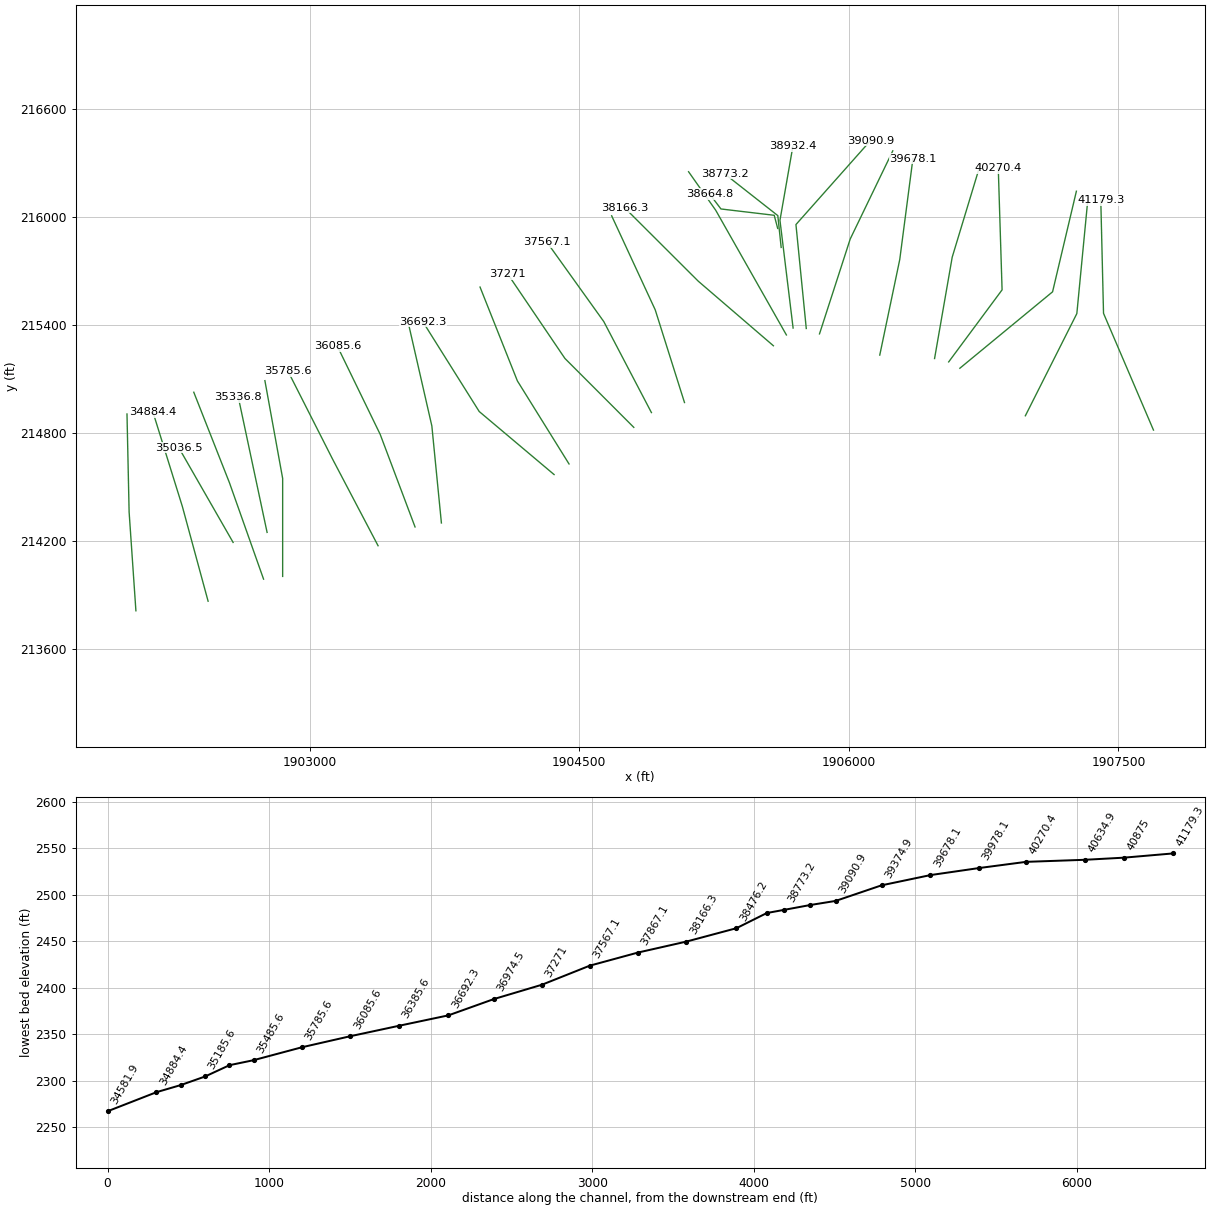
HEC-RAS study TmmyCrk.prj: TmmyCrk

--- TmmyCrk.g01 (geometry) --- (continued)

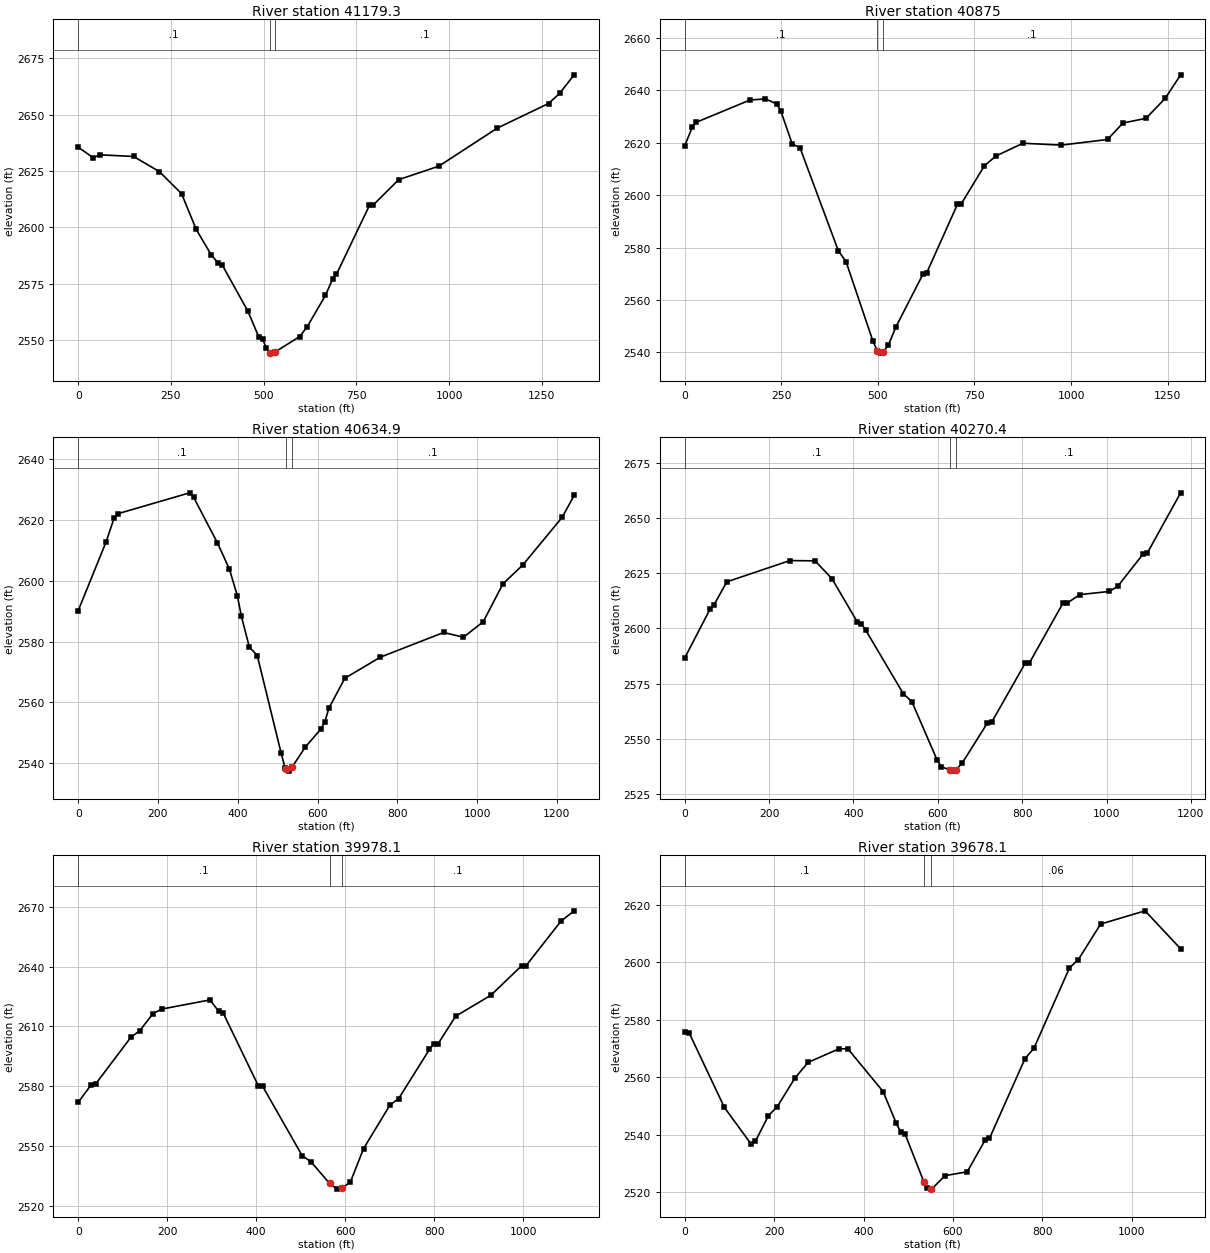
Type RM Length L Ch R = 1 ,41179.3 ,324.1,304.3,284.5
XS GIS Cut Line= 3
     1907694.949      214815.218     1907417.062      215464.339
     1907401.801      216094.982
#Sta/Elev= 30
       0  2635.6    39.8 2631.03    59.7 2632.22   149.2  2631.5   218.8 2624.78
   278.5 2615.03   318.2 2599.11     358    2588   377.9 2584.07   387.9 2583.45
   457.5 2562.84   487.3 2551.22   497.2 2550.51   507.2 2546.44   516.6 2544.37
   517.1 2544.26   531.6 2544.84   596.7 2551.59   616.6 2555.77   666.3 2569.83
   686.2 2577.25   696.2 2579.26     785 2609.76   794.8  2609.9   863.8  2621.2
   972.2  2627.2  1129.9  2644.1  1267.9 2654.99  1297.5 2659.43  1336.9 2667.71
#Mann= 3 , 0 , 0
       0      .1       0   516.6    .045       0   531.6      .1       0
Bank Sta=516.6,531.6
XS Rating Curve= 0 ,0
Exp/Cntr=0.3,0.1

Type RM Length L Ch R = 1 ,40875   ,249.5,240.1,230.8
XS GIS Cut Line= 3
     1906982.103      214894.762      1907268.56      215463.001
     1907330.685      216107.026
#Sta/Elev= 30
       0 2618.79    19.9 2626.04    29.8  2627.8     169 2636.31   208.8 2636.73
   238.6  2634.8   248.6 2632.17   278.4  2619.5   298.3 2618.13   397.7 2578.76
   417.6 2574.61   487.2 2544.27   498.6 2540.59   507.1 2539.71   513.6  2540.1
     527 2542.73   546.9 2549.78   616.5  2569.8   626.4 2570.38     706 2596.53
     716 2596.75   775.7 2611.22   805.6 2614.95   875.3 2619.81   974.8  2619.1
  1094.2 2621.24  1134.1 2627.52  1193.8 2629.32  1243.6 2636.95  1283.4 2645.92
#Mann= 3 , 0 , 0
       0      .1       0   498.6    .045       0   513.6      .1       0
Bank Sta=498.6,513.6
XS Rating Curve= 0 ,0
Exp/Cntr=0.3,0.1

Type RM Length L Ch R = 1 ,40634.9 ,343.3,363.7,384.2
XS GIS Cut Line= 3
     1906617.605      215159.154     1907133.508      215584.082
     1907266.049      216143.628
#Sta/Elev= 30
       0 2590.21    69.8 2612.74    89.8 2620.55    99.8 2622.06   279.3 2628.91
   289.3 2627.45   349.2 2612.43   379.1 2603.83     399 2595.07     409 2588.39
     429 2578.22   448.9 2575.44   508.8 2543.33   518.7 2538.44   521.5 2538.16
   528.7 2537.44   536.5  2538.8   568.6 2545.22   608.5 2551.31   618.5 2553.67
   628.5 2558.13   668.4 2567.96   757.6  2574.9   916.2 2583.01   965.8 2581.44
  1015.4 2586.53  1064.9    2599  1114.5 2605.17  1213.7 2620.92  1243.4 2628.07
#Mann= 3 , 0 , 0
       0      .1       0   521.5    .045       0   536.5      .1       0
Bank Sta=521.5,536.5
XS Rating Curve= 0 ,0
Exp/Cntr=0.3,0.1

Type RM Length L Ch R = 1 ,40270.4 ,296.4,292,284.7
XS GIS Cut Line= 3
     1906555.379      215194.287     1906852.538      215594.948
     1906831.322      216271.503
#Sta/Elev= 30
       0 2586.57    59.9  2608.7    69.8 2610.83    99.8 2621.18   249.4 2630.84
   309.3 2630.71   349.2 2622.59     409 2603.07     419 2602.12     429 2599.31
   518.7 2570.26   538.6 2566.79   598.4 2540.26   608.3 2537.28   628.2 2535.74
   638.2 2535.23   643.2 2535.73   658.1 2538.96   717.8 2557.13   727.8 2557.45
   807.4 2584.29   817.4 2584.42     897 2611.59     907 2611.58   936.8 2615.39
  1006.5 2616.81  1026.4 2619.11  1086.1 2633.65  1096.1 2634.05  1175.7  2661.6
#Mann= 3 , 0 , 0
       0      .1       0   628.2    .045       0   643.2      .1       0
Bank Sta=628.2,643.2
XS Rating Curve= 0 ,0
Exp/Cntr=0.3,0.1

Type RM Length L Ch R = 1 ,39978.1 ,300.7,300,303.9
XS GIS Cut Line= 3
     1906476.824      215213.086     1906575.042      215777.067
     1906732.482      216296.078
#Sta/Elev= 30
       0 2572.02    29.6 2580.91    39.5 2581.29   118.4 2604.59   138.2 2607.82
   167.8 2616.35   187.5  2618.7   296.1 2623.29   315.8  2617.6   325.7 2616.81
   404.7 2580.36   414.6 2580.02   503.4 2545.31   523.1  2542.3     565 2531.41
   582.3 2528.55   592.2 2528.96   611.9 2532.11   641.5 2548.89   700.7 2570.63
   720.4 2573.92   789.4 2598.47   799.3  2601.4   809.1 2601.41   848.6 2615.18
   927.5  2625.6   996.5 2640.35  1006.4 2640.37  1085.2 2662.73  1114.8  2667.9
#Mann= 3 , 0 , 0
       0      .1       0     565    .045       0   592.2      .1       0
Bank Sta=565,592.2
XS Rating Curve= 0 ,0
Exp/Cntr=0.3,0.1

Type RM Length L Ch R = 1 ,39678.1 ,308.5,303.1,296.1
XS GIS Cut Line= 3
     1906171.844      215232.258     1906282.968      215763.107
     1906356.406      216324.982
#Sta/Elev= 30
       0  2575.8     9.9 2575.41    88.8 2549.43   147.9 2536.82   157.8 2537.58
   187.4 2546.58   207.1 2549.72   246.5 2559.66   276.1 2565.13   345.1 2569.84
   364.9 2569.84   443.8 2554.95   473.3 2543.85   483.2 2540.92     493 2540.11
   534.9  2523.5   542.4 2521.33   549.9 2521.08   552.3    2521   582.1 2525.69
   631.8 2527.03   671.6 2538.02   681.5 2538.65   761.1 2566.44     781 2570.04
   860.5 2598.02   880.4 2600.92   930.1 2613.26  1029.5 2617.87    1109 2604.65
#Mann= 3 , 0 , 0
       0      .1       0   534.9    .045       0   549.9     .06       0
Bank Sta=534.9,549.9
XS Rating Curve= 0 ,0
Exp/Cntr=0.3,0.1

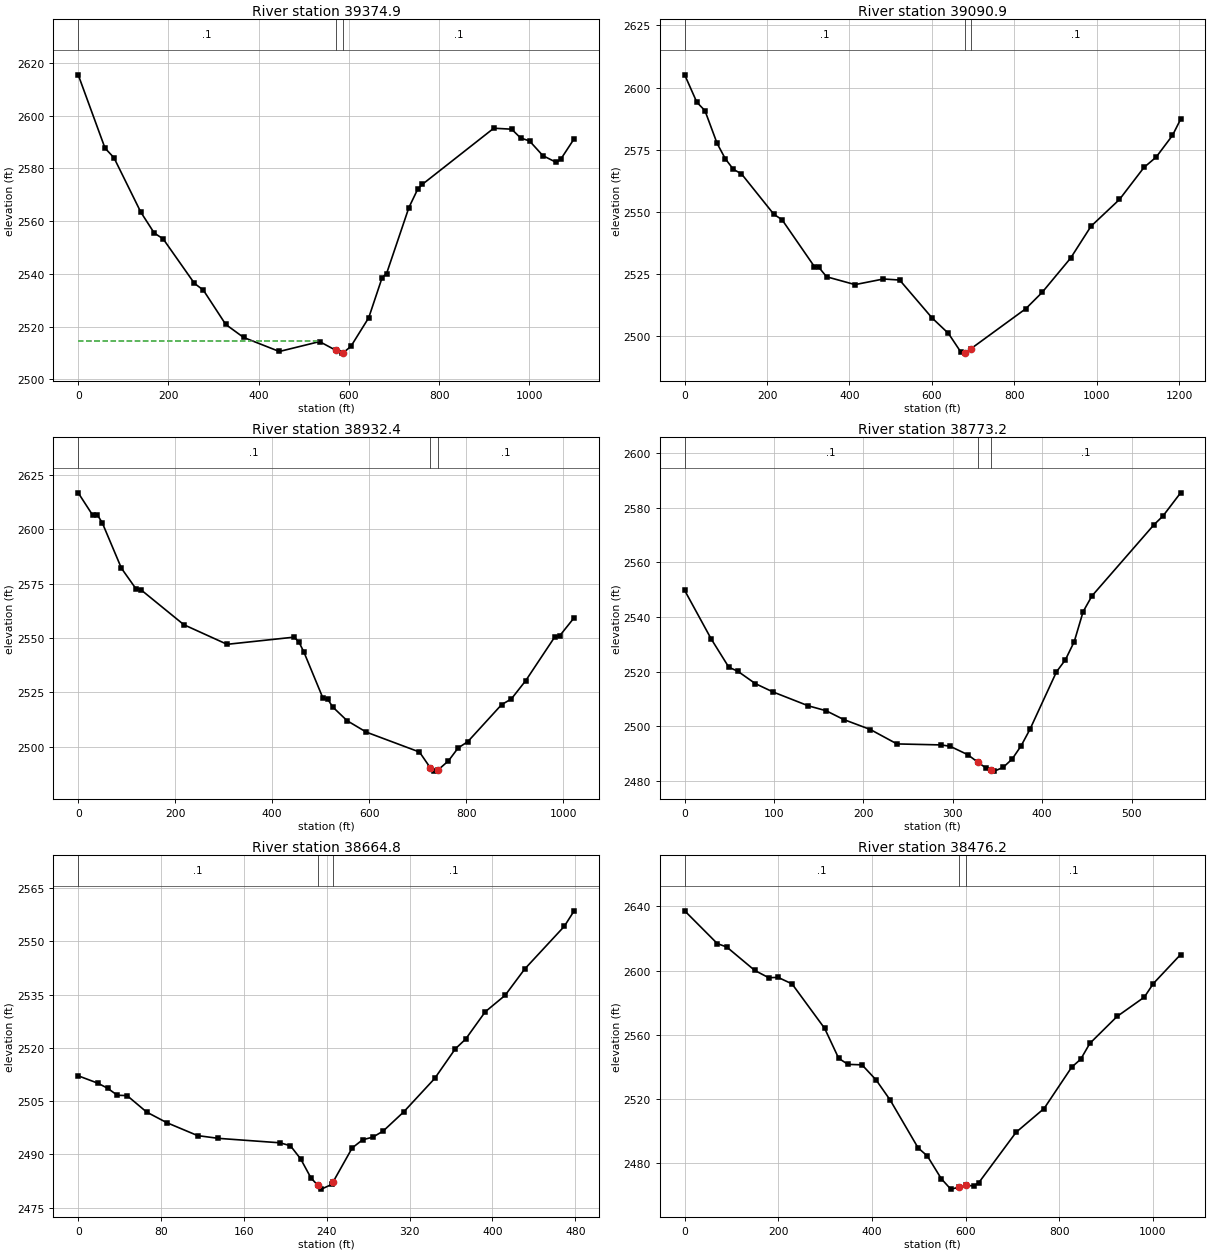
Type RM Length L Ch R = 1 ,39374.9 ,290.5,283.9,277.4
XS GIS Cut Line= 3
     1905836.445      215350.183     1906007.417      215877.849
     1906244.285      216368.095
#Sta/Elev= 30
       0 2615.47    59.4 2587.68    79.2 2584.05   138.7 2563.42   168.4 2555.51
   188.2 2553.28   257.5 2536.42   277.3 2533.86   326.9 2520.85   366.5 2515.92
   445.7 2510.59   534.9 2514.34   571.8 2510.97   584.4 2509.97   586.8 2510.06
   604.2 2512.49   643.8 2523.38   673.5 2538.57   683.4 2540.14   732.9 2565.17
   752.7 2572.23   762.6 2573.94     921 2595.23   960.6 2594.86   980.4 2591.54
  1000.2  2590.4  1029.8 2584.83  1059.5 2582.28  1069.4 2583.47  1099.1 2591.23
#Mann= 3 , 0 , 0
       0      .1       0   571.8    .045       0   586.8      .1       0
#XS Ineff= 2 , 0
          533.48  2514.4
Permanent Ineff=
       F       F
Bank Sta=571.8,586.8
XS Rating Curve= 0 ,0
Exp/Cntr=0.3,0.1

Type RM Length L Ch R = 1 ,39090.9 ,146,158.5,171
XS GIS Cut Line= 3
     1905762.818      215380.084     1905705.374      215958.191
      1906119.22      216423.871
#Sta/Elev= 30
       0 2605.13    29.5 2594.11    49.2 2590.73    78.8 2577.53    98.5 2571.41
   118.2 2567.12   137.8 2565.32   216.6 2549.03   236.3 2546.88   315.1 2527.97
   324.9 2527.86   344.6 2523.92   413.6 2520.77   482.5 2523.03   521.9 2522.61
   600.7 2507.35   640.3 2501.15     670 2493.76   679.8 2493.22   680.7 2493.31
   695.7 2495.08   828.2 2511.09   867.7 2517.62     937 2531.44   986.4 2544.23
  1055.6 2555.02    1115 2567.88  1144.6 2572.04  1184.2 2580.76    1204 2587.26
#Mann= 3 , 0 , 0
       0      .1       0   680.7    .045       0   695.7      .1       0
Bank Sta=680.7,695.7
XS Rating Curve= 0 ,0
Exp/Cntr=0.3,0.1

Type RM Length L Ch R = 1 ,38932.4 ,131.8,158.9,184.8
XS GIS Cut Line= 3
     1905689.561      215382.609     1905616.451      215981.985
     1905688.495      216394.266
#Sta/Elev= 30
       0 2616.83    29.7 2606.58    39.6 2606.63    49.5 2603.08    89.1 2582.12
   118.8 2572.75   128.7 2572.33   217.8 2556.14   306.9 2547.12   445.4 2550.43
   455.3 2548.04   465.2 2543.59   504.8  2522.2   514.7 2521.77   524.6 2518.31
   554.3 2511.98   593.9 2506.72   703.5 2497.56   725.8 2490.32   733.4 2488.77
   740.8 2489.12   763.3  2493.5   783.2 2499.44   803.1 2502.32   872.9 2519.38
   892.8 2521.96   922.7 2530.45   982.5 2550.54   992.4 2550.99  1022.4 2559.36
#Mann= 3 , 0 , 0
       0      .1       0   725.8    .045       0   740.8      .1       0
Bank Sta=725.8,740.8
XS Rating Curve= 0 ,0
Exp/Cntr=0.3,0.1

Type RM Length L Ch R = 1 ,38773.2 ,98.2,108.5,119.9
XS GIS Cut Line= 3
     1905623.101      215830.901     1905604.473      216007.865
      1905307.98      216240.713
#Sta/Elev= 30
       0 2549.73    29.7 2531.96    49.4 2521.64    59.3  2520.2    79.1 2515.64
    98.9 2512.59   138.4 2507.52   158.2 2505.74   177.9 2502.52   207.7 2498.87
   237.5  2493.6   287.1 2493.23     297 2492.73   316.8 2489.65   327.8 2486.97
   336.7 2484.88   342.8 2484.12   346.6 2483.65   356.5 2485.06   366.4 2488.06
   376.4 2492.88   386.3 2498.92     416 2519.96     426 2524.37   435.9 2531.02
   445.8 2541.95   455.7 2547.71   525.2 2573.79   535.1 2576.91   554.9 2585.41
#Mann= 3 , 0 , 0
       0      .1       0   327.8    .045       0   342.8      .1       0
Bank Sta=327.8,342.8
XS Rating Curve= 0 ,0
Exp/Cntr=0.3,0.1

Type RM Length L Ch R = 1 ,38664.8 ,210.3,188.5,166.8
XS GIS Cut Line= 4
      1905603.82      215936.686     1905584.468      216009.697
     1905288.025      216044.883      1905224.69       216128.45
#Sta/Elev= 30
       0 2512.14    18.9 2510.06    28.3 2508.65    37.8 2506.66    47.2 2506.56
    66.1 2501.92    85.5 2498.94   115.3 2495.29   135.2 2494.52   194.9 2493.26
   204.9 2492.43   214.8 2488.73   224.8 2483.34   231.3 2481.31   234.8 2480.21
   244.7 2481.52   246.3 2482.33   264.6 2491.83   274.6 2494.11   284.5 2494.86
   294.4 2496.55   314.4 2501.99   344.2 2511.38   364.1 2519.72   374.1 2522.47
   393.1 2530.19   412.2  2534.8   431.2 2542.24   469.4 2554.26   478.9 2558.62
#Mann= 3 , 0 , 0
       0      .1       0   231.3    .045       0   246.3      .1       0
Bank Sta=231.3,246.3
XS Rating Curve= 0 ,0
Exp/Cntr=0.3,0.1

Type RM Length L Ch R = 1 ,38476.2 ,301.5,309.6,316
XS GIS Cut Line= 3
     1905652.152      215344.296     1905258.663      216038.058
     1905107.821      216251.938
#Sta/Elev= 30
       0 2637.27    69.8 2616.83    89.7 2614.76   149.6 2600.15   179.5 2595.59
   199.4 2595.81   229.3 2591.75   299.1 2563.97     329 2545.34   348.9  2541.6
   378.8 2541.31   408.8 2531.92   438.7 2519.47   498.5 2489.61   518.4 2484.48
   548.3 2470.27   568.3 2463.87   586.1    2465   601.1 2466.14   618.1  2465.9
   628.1 2467.84   707.9  2499.3   767.7  2514.1   826.7 2539.87     846 2544.85
   865.4 2554.68   923.6 2571.46   981.8  2583.5  1001.1 2591.97  1059.3 2610.05
#Mann= 3 , 0 , 0
       0      .1       0   586.1    .045       0   601.1      .1       0
Bank Sta=586.1,601.1
XS Rating Curve= 0 ,0
Exp/Cntr=0.3,0.1

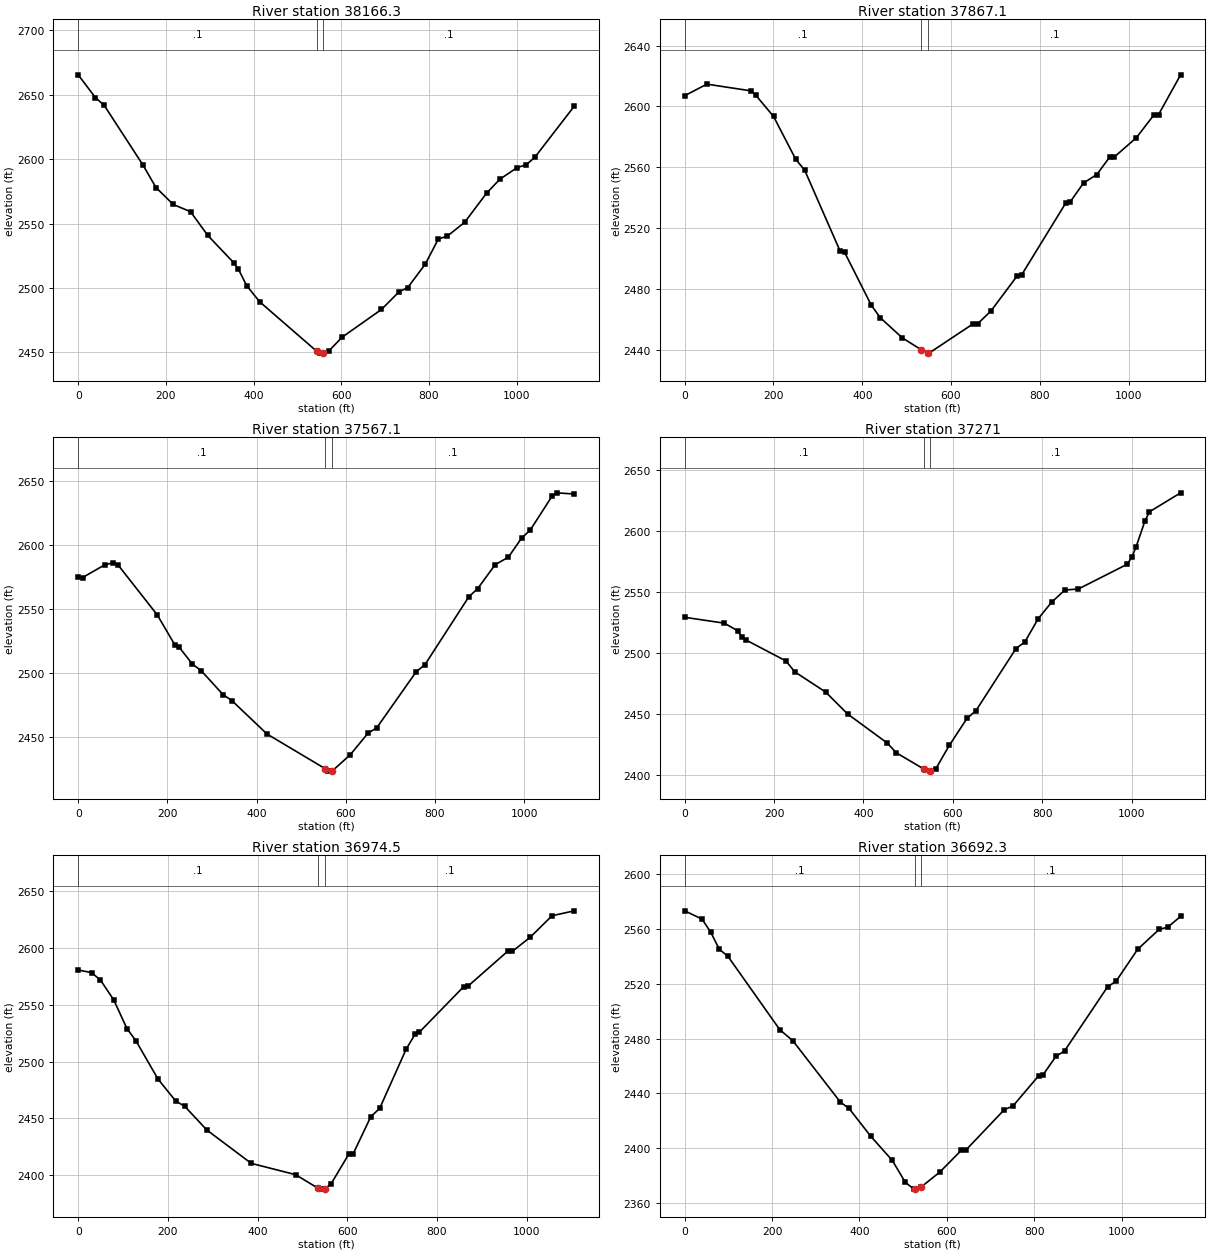
Type RM Length L Ch R = 1 ,38166.3 ,311.8,299.1,291.1
XS GIS Cut Line= 3
     1905579.927      215284.093     1905161.235      215643.714
      1904750.84      216052.847
#Sta/Elev= 30
       0 2665.42    39.4 2647.64    59.1 2641.83   147.8 2595.39   177.4 2577.99
   216.8 2564.82   256.2 2559.24   295.7 2540.76   354.8 2519.61   364.7 2515.11
   384.4  2501.8     414 2489.31   544.4 2450.84   551.9 2449.48   559.4 2449.61
   571.9 2451.19   601.9  2461.8   691.8 2483.36   731.8    2497   751.8 2500.36
   791.7 2518.52   821.7 2538.07   841.7 2540.17   881.6    2551   931.6 2573.57
   961.6 2584.33  1001.5  2593.5  1021.5 2595.52  1041.5 2601.35  1131.4 2640.99
#Mann= 3 , 0 , 0
       0      .1       0   544.4    .045       0   559.4      .1       0
Bank Sta=544.4,559.4
XS Rating Curve= 0 ,0
Exp/Cntr=0.3,0.1

Type RM Length L Ch R = 1 ,37867.1 ,295.5,299.4,302.4
XS GIS Cut Line= 3
     1905085.127      214968.335     1904922.328      215483.699
     1904679.815      216006.844
#Sta/Elev= 30
       0 2607.03      50 2614.63   150.1 2610.19   160.1 2607.37   200.2 2593.38
   250.2 2565.18   270.2 2558.11   350.3  2504.7   360.3 2503.96   420.4 2469.23
   440.4 2461.06   490.4 2447.72     533 2439.92     548 2437.84   550.4 2437.72
   649.8 2457.01   659.8 2457.01   689.6 2465.33   749.2 2488.61   759.2 2489.28
   858.6 2536.55   868.5 2537.21   898.4 2549.63   928.2 2555.15     958  2566.9
     968 2566.78  1017.7 2579.48  1057.4 2594.55  1067.4 2594.61  1117.1 2620.76
#Mann= 3 , 0 , 0
       0      .1       0     533    .045       0     548      .1       0
Bank Sta=533,548
XS Rating Curve= 0 ,0
Exp/Cntr=0.3,0.1

Type RM Length L Ch R = 1 ,37567.1 ,289,295.9,296.6
XS GIS Cut Line= 3
     1904901.116      214912.494     1904636.092      215418.435
     1904320.829      215858.385
#Sta/Elev= 30
       0 2575.21     9.8 2574.72    59.1 2584.56    78.8 2586.32    88.6 2584.88
   177.2  2545.6   216.6 2522.21   226.5 2520.28     256 2507.19   275.7 2502.03
     325 2483.27   344.7 2478.64   423.4 2452.55   554.6 2425.34   561.3 2423.56
   569.6 2423.64   610.5 2436.45   649.9 2453.16   669.6 2457.39   758.1 2501.14
   777.8 2506.72   876.2 2559.71   895.9 2566.03   935.3  2584.8   964.8  2590.6
   994.3 2605.43    1014 2611.82  1063.2 2638.48    1073 2640.87  1112.4 2639.94
#Mann= 3 , 0 , 0
       0      .1       0   554.6    .045       0   569.6      .1       0
Bank Sta=554.6,569.6
XS Rating Curve= 0 ,0
Exp/Cntr=0.3,0.1

Type RM Length L Ch R = 1 ,37271   ,301.8,296.4,291.7
XS GIS Cut Line= 3
     1904803.021      214830.251     1904419.655      215213.643
      1904101.22      215683.558
#Sta/Elev= 30
       0 2529.28    88.7 2524.46   118.3 2518.32   128.2 2513.04     138  2510.5
   226.7 2493.44   246.4 2484.51   315.4 2467.96   364.7 2449.94   453.5 2426.06
   473.2 2418.22   534.7 2404.86   549.7 2403.26   552.1 2403.07   562.1 2405.07
     592  2424.1   631.8 2446.36   651.7 2452.62   741.4 2503.64   761.3  2509.1
   791.2 2528.17     821 2541.62   850.9 2551.68   880.8 2552.45   990.3  2572.8
  1000.3 2578.41  1010.2 2587.11  1030.2 2608.56  1040.1 2615.84  1109.8 2631.39
#Mann= 3 , 0 , 0
       0      .1       0   534.7    .045       0   549.7      .1       0
Bank Sta=534.7,549.7
XS Rating Curve= 0 ,0
Exp/Cntr=0.3,0.1

Type RM Length L Ch R = 1 ,36974.5 ,275,282.1,288.9
XS GIS Cut Line= 3
     1904442.583      214626.719     1904155.185      215088.646
     1903947.394      215610.498
#Sta/Elev= 30
       0 2580.79    29.7 2578.47    49.5 2571.95    79.1  2554.5   108.8 2529.07
   128.6 2518.47     178 2484.62   217.6 2465.24   237.4 2460.75   286.8 2439.79
   385.8 2410.43   484.7 2400.47   534.2 2388.61     544 2387.73   549.2 2387.92
   563.7 2392.33   603.2  2418.5     613 2418.87   652.4 2451.56   672.1 2458.87
   731.3 2511.17     751 2524.12   760.8 2526.08   859.4 2566.09   869.2  2566.6
   957.9 2597.42   967.8  2597.2  1007.2 2609.45  1056.5 2628.58  1105.7 2632.91
#Mann= 3 , 0 , 0
       0      .1       0   534.2    .045       0   549.2      .1       0
Bank Sta=534.2,549.2
XS Rating Curve= 0 ,0
Exp/Cntr=0.3,0.1

Type RM Length L Ch R = 1 ,36692.3 ,324.7,306.7,295.5
XS GIS Cut Line= 3
     1904359.442      214567.794     1903942.819      214918.315
     1903628.701      215418.414
#Sta/Elev= 30
       0 2573.21    39.6  2567.2    59.4 2557.73    79.2 2545.21      99    2540
   217.8 2486.45   247.5 2478.44   356.4 2433.63   376.2 2429.02   425.7 2408.79
   475.2  2391.1   504.9 2375.14   524.7 2370.17   526.1 2370.17   541.1 2371.72
   583.8 2382.59     633 2398.44   642.9 2398.44   731.5 2428.14   751.2 2430.76
   810.2 2452.92   820.1 2453.53   849.6 2467.02   869.3 2470.96   967.7  2517.7
   987.4 2521.88  1036.6 2545.12  1085.8 2559.65  1105.5 2561.29    1135 2569.14
#Mann= 3 , 0 , 0
       0      .1       0   526.1    .045       0   541.1      .1       0
Bank Sta=526.1,541.1
XS Rating Curve= 0 ,0
Exp/Cntr=0.3,0.1

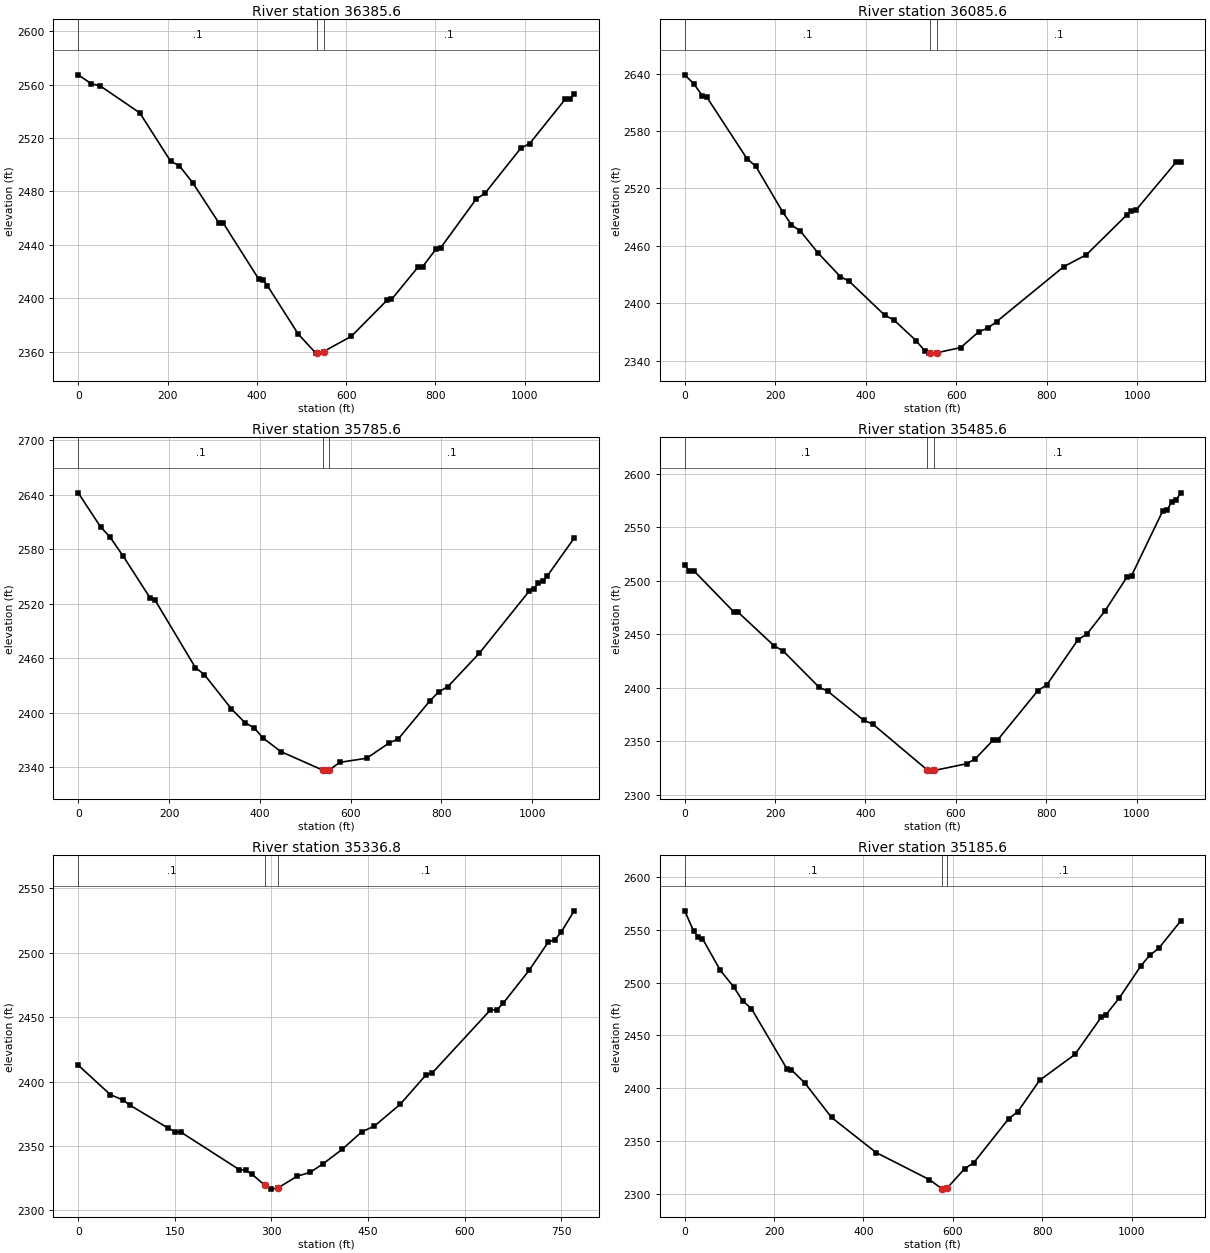
Type RM Length L Ch R = 1 ,36385.6 ,294.2,300.1,305.2
XS GIS Cut Line= 3
     1903732.337      214298.543      1903679.22      214837.847
       1903552.4      215392.352
#Sta/Elev= 30
       0 2567.29    29.6 2560.57    49.3    2559   137.9 2538.79   206.9 2502.62
   226.6 2499.12   256.2 2486.62   315.3 2456.31   325.2 2456.09     404  2414.5
   413.8 2413.83   423.7 2409.46   492.6 2373.28   532.1 2358.93   534.4 2358.93
   549.4  2360.1   611.8 2371.55   691.6 2398.51   701.6 2399.09   761.5 2423.54
   771.4 2423.68   801.4 2436.91   811.4 2437.59   891.2 2474.24   911.2  2478.7
     991 2512.26  1010.9 2515.77  1090.8 2549.06  1100.8 2548.89  1110.7 2552.89
#Mann= 3 , 0 , 0
       0      .1       0   534.4    .045       0   549.4      .1       0
Bank Sta=534.4,549.4
XS Rating Curve= 0 ,0
Exp/Cntr=0.3,0.1

Type RM Length L Ch R = 1 ,36085.6 ,296.9,299.7,300.2
XS GIS Cut Line= 3
     1903585.649      214276.398     1903391.577      214791.576
     1903153.039      215282.255
#Sta/Elev= 30
       0 2638.91    19.7 2629.82    39.3 2616.89    49.2 2615.34   137.6 2551.24
   157.3 2543.15   216.3 2495.67   235.9 2482.01   255.6 2475.45   294.9 2452.48
   344.1 2427.76   363.7 2422.88   442.4 2387.28     462 2382.63   511.2 2360.92
   530.9    2350   540.7 2347.75     543 2347.87     558 2348.26     610  2353.5
   649.7 2370.03   669.6 2373.83   689.4 2380.72   838.2 2438.34   887.8 2450.66
   977.1  2492.3     987 2496.36   996.9 2497.08  1086.2 2547.59  1096.1  2548.1
#Mann= 3 , 0 , 0
       0      .1       0     543    .045       0     558      .1       0
Bank Sta=543,558
XS Rating Curve= 0 ,0
Exp/Cntr=0.3,0.1

Type RM Length L Ch R = 1 ,35785.6 ,310.9,299.9,293.4
XS GIS Cut Line= 3
     1903379.866      214171.981     1903125.928      214655.194
     1902878.668      215142.345
#Sta/Elev= 30
       0 2642.35    49.6 2604.57    69.5 2593.98    99.2 2572.55   158.8 2526.17
   168.7 2524.61     258 2449.92   277.9 2442.11   337.4 2404.42   367.2 2389.21
   387.1 2383.74   406.9 2372.34   446.6 2357.28   538.4 2337.04   545.9 2335.87
   553.4 2337.17   575.7 2345.52   635.3 2350.07   684.9 2366.96   704.8 2371.26
   774.3 2413.14   794.2 2423.25   814.1  2428.9   883.6 2465.84   992.8 2533.86
  1002.8 2535.97  1012.7 2542.63  1022.6 2544.82  1032.6 2550.48  1092.2 2592.45
#Mann= 3 , 0 , 0
       0      .1       0   538.4    .045       0   553.4      .1       0
Bank Sta=538.4,553.4
XS Rating Curve= 0 ,0
Exp/Cntr=0.3,0.1

Type RM Length L Ch R = 1 ,35485.6 ,144.1,148.8,149.5
XS GIS Cut Line= 3
     1902848.923      214001.343     1902848.943      214546.148
      1902750.12      215090.015
#Sta/Elev= 30
       0 2514.72     9.9 2509.37    19.8 2509.37     109 2470.59   118.9 2470.18
   198.1 2438.96   217.9 2434.24   297.2 2400.46     317  2396.5   396.2 2369.37
     416    2366   537.3 2322.88   544.8 2321.94   552.3 2322.55   623.8 2328.82
   643.5 2333.55     683 2351.09   692.9  2351.2   781.7 2397.18   801.4 2402.55
   870.6 2444.74   890.3 2450.05   929.8 2471.38   979.1 2503.47     989 2504.55
  1058.1 2565.14    1068 2566.03  1077.8 2573.68  1087.7 2575.08  1097.6 2581.98
#Mann= 3 , 0 , 0
       0      .1       0   537.3    .045       0   552.3      .1       0
Bank Sta=537.3,552.3
XS Rating Curve= 0 ,0
Exp/Cntr=0.3,0.1

Type RM Length L Ch R = 1 ,35336.8 ,148.1,151.1,154.8
XS GIS Cut Line= 2
     1902762.282      214246.182     1902601.873      214999.263
#Sta/Elev= 30
       0 2412.81      50 2389.87      70 2385.68      80 2381.84     140 2363.85
     150 2361.22     160 2360.65     250 2331.72     260 2331.14     270 2328.06
     290 2319.47     300 2316.58     310 2317.45     340 2326.62     360 2329.58
     380 2336.17     410 2347.54     440 2360.96     460 2365.58     500  2382.5
     540 2405.26     550 2406.95     640  2455.7     650 2455.73     660 2461.02
     700  2486.4     730 2508.54     740 2510.05     750 2516.25     770 2532.65
#Mann= 3 , 0 , 0
       0      .1       0     290    .045       0     310      .1       0
Bank Sta=290,310
XS Rating Curve= 0 ,0
Exp/Cntr=0.3,0.1

Type RM Length L Ch R = 1 ,35185.6 ,144.8,148.9,152.3
XS GIS Cut Line= 3
     1902742.651      213986.174     1902553.157       214521.36
      1902354.33      215025.705
#Sta/Elev= 30
       0 2568.06    19.9 2549.04    29.9 2543.27    39.8 2541.67    79.7 2511.72
   109.6 2496.12   129.5 2482.83   149.4 2475.43   229.1 2418.18     239 2417.34
   268.9 2404.96   328.7 2372.31   428.3  2339.1   547.8 2313.39   575.2 2304.89
   577.6 2304.42   587.5 2305.48   626.9 2323.96   646.6 2329.21   725.4 2371.32
   745.2 2377.61   794.4 2407.52   873.3    2432   932.4 2467.38   942.3 2469.38
   971.9 2485.04  1021.2 2516.05  1040.9 2526.04  1060.6 2532.38  1109.9 2558.38
#Mann= 3 , 0 , 0
       0      .1       0   575.2    .045       0   587.5      .1       0
Bank Sta=575.2,587.5
XS Rating Curve= 0 ,0
Exp/Cntr=0.3,0.1

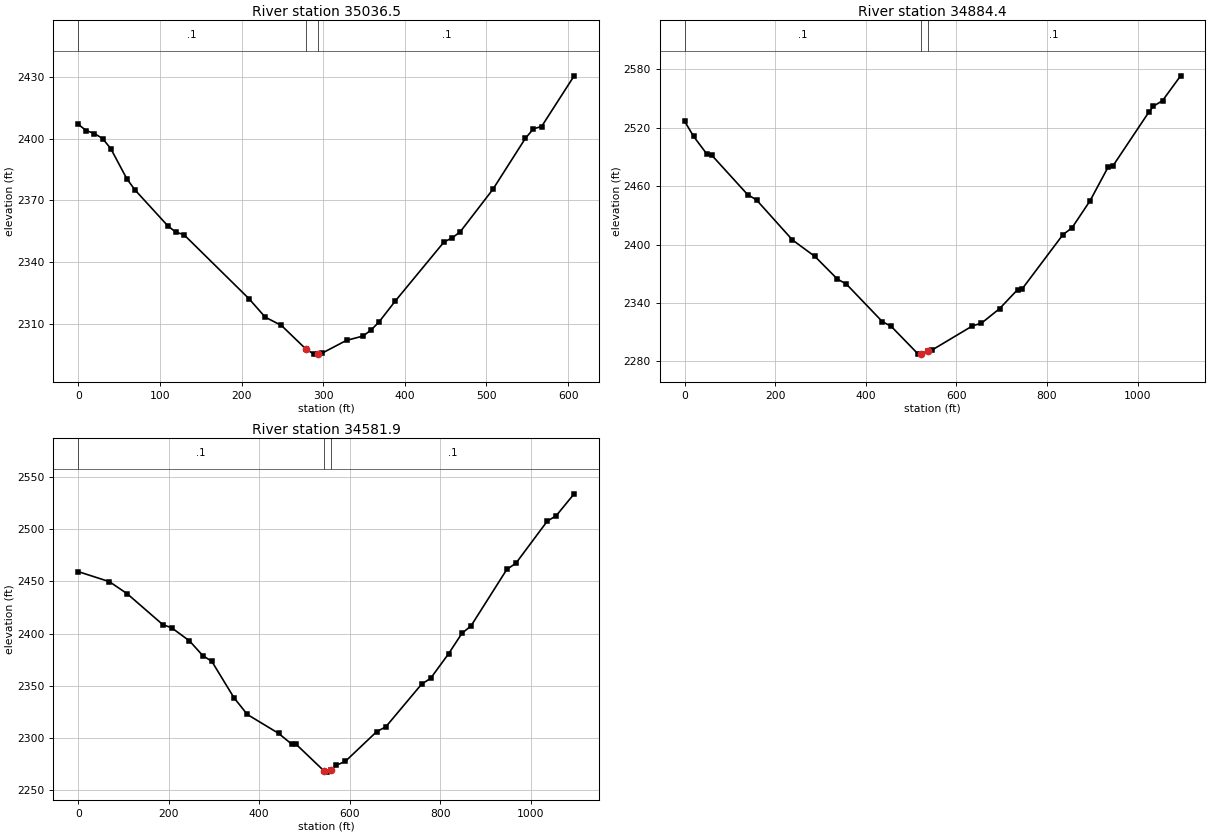
Type RM Length L Ch R = 1 ,35036.5 ,157.8,152,146.3
XS GIS Cut Line= 2
     1902573.168       214190.46     1902270.922       214717.28
#Sta/Elev= 30
       0 2407.02      10 2403.95    19.9 2402.56    29.9  2400.1    39.8 2395.27
    59.7 2380.44    69.7 2375.05   109.5 2357.76   119.5 2354.58   129.4 2353.41
   209.1 2322.25     229 2313.27   248.9 2309.22   279.2 2297.62   288.8 2295.28
   294.2 2295.54   298.7 2295.76   328.6 2301.98   348.5 2304.03   358.4 2306.88
   368.4 2310.92   388.3 2321.09   448.1 2349.87     458 2351.78     468 2354.84
   507.8 2375.38   547.6 2400.18   557.6 2404.87   567.5 2405.95   607.4 2430.62
#Mann= 3 , 0 , 0
       0      .1       0   279.2    .045       0   294.2      .1       0
Bank Sta=279.2,294.2
XS Rating Curve= 0 ,0
Exp/Cntr=0.3,0.1

Type RM Length L Ch R = 1 ,34884.4 ,306.9,302.4,296.7
XS GIS Cut Line= 3
     1902434.058      213863.403     1902290.936      214389.665
     1902127.399      214914.393
#Sta/Elev= 30
       0 2526.52    19.8 2511.01    49.6 2492.58    59.5 2491.93   138.8  2451.4
   158.6 2445.84     238 2404.74   287.6  2387.8   337.1 2364.62     357 2359.45
   436.3 2320.95   456.1 2315.99   515.6 2287.54   521.4 2287.66   536.4 2291.02
   545.4 2291.53   635.3  2316.5   655.3 2319.35   695.3 2334.24   735.2 2353.82
   745.2 2354.55   835.2 2410.21   855.2  2417.2   895.1    2445   935.1 2479.73
   945.1 2480.46    1025 2536.11    1035 2542.11    1055 2547.75    1095 2573.26
#Mann= 3 , 0 , 0
       0      .1       0   521.4    .045       0   536.4      .1       0
Bank Sta=521.4,536.4
XS Rating Curve= 0 ,0
Exp/Cntr=0.3,0.1

Type RM Length L Ch R = 1 ,34581.9 ,291.4,300,303.8
XS GIS Cut Line= 3
     1902032.272      213810.114     1901994.486      214359.588
     1901982.653      214904.617
#Sta/Elev= 30
       0 2459.43    68.8  2449.8   108.2 2438.21   186.9 2408.56   206.5 2405.52
   245.9 2392.95   275.4 2378.78   295.1 2373.39   344.2 2338.42   373.7 2322.37
   442.6 2304.28   472.1  2293.8   481.9  2293.6   543.3 2268.18   550.8 2267.05
   558.3 2268.89   570.6 2273.68   590.4 2277.43   659.8 2305.99   679.6 2310.45
   758.9 2351.49   778.8 2357.05   818.4 2380.64   848.1 2400.32     868 2407.33
   947.2  2461.6   967.1  2467.4  1036.5 2507.85  1056.3 2513.08  1095.9 2534.06
#Mann= 3 , 0 , 0
       0      .1       0   543.3    .045       0   558.3      .1       0
Bank Sta=543.3,558.3
XS Rating Curve= 0 ,0
Exp/Cntr=0.3,0.1