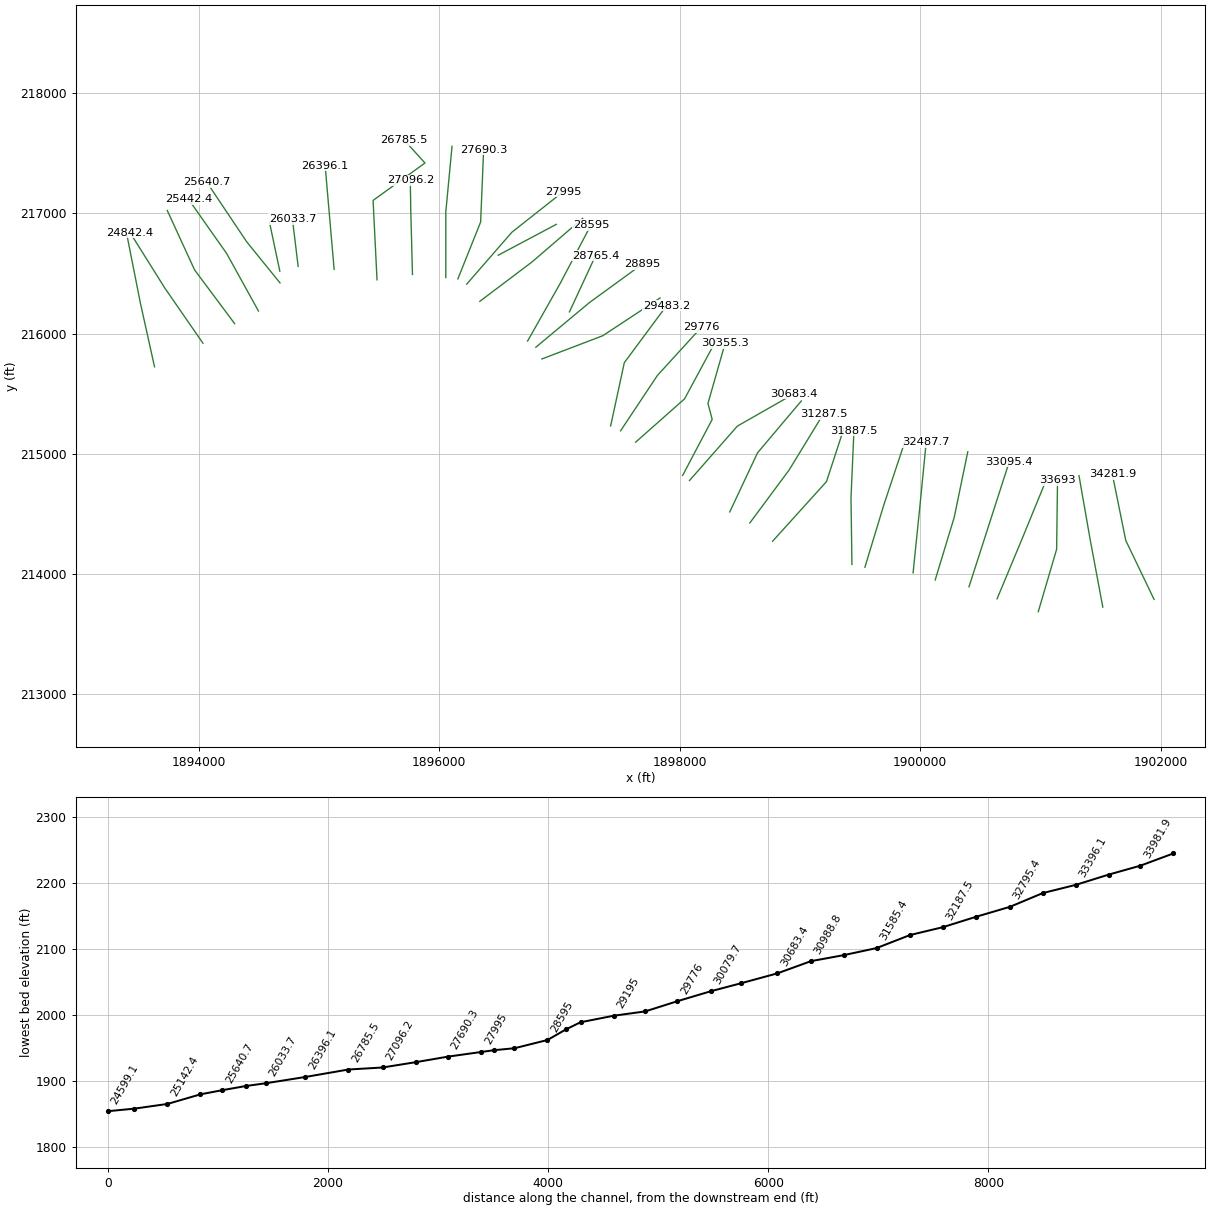
HEC-RAS study TmmyCrk.prj: TmmyCrk

--- TmmyCrk.g01 (geometry) --- (continued)

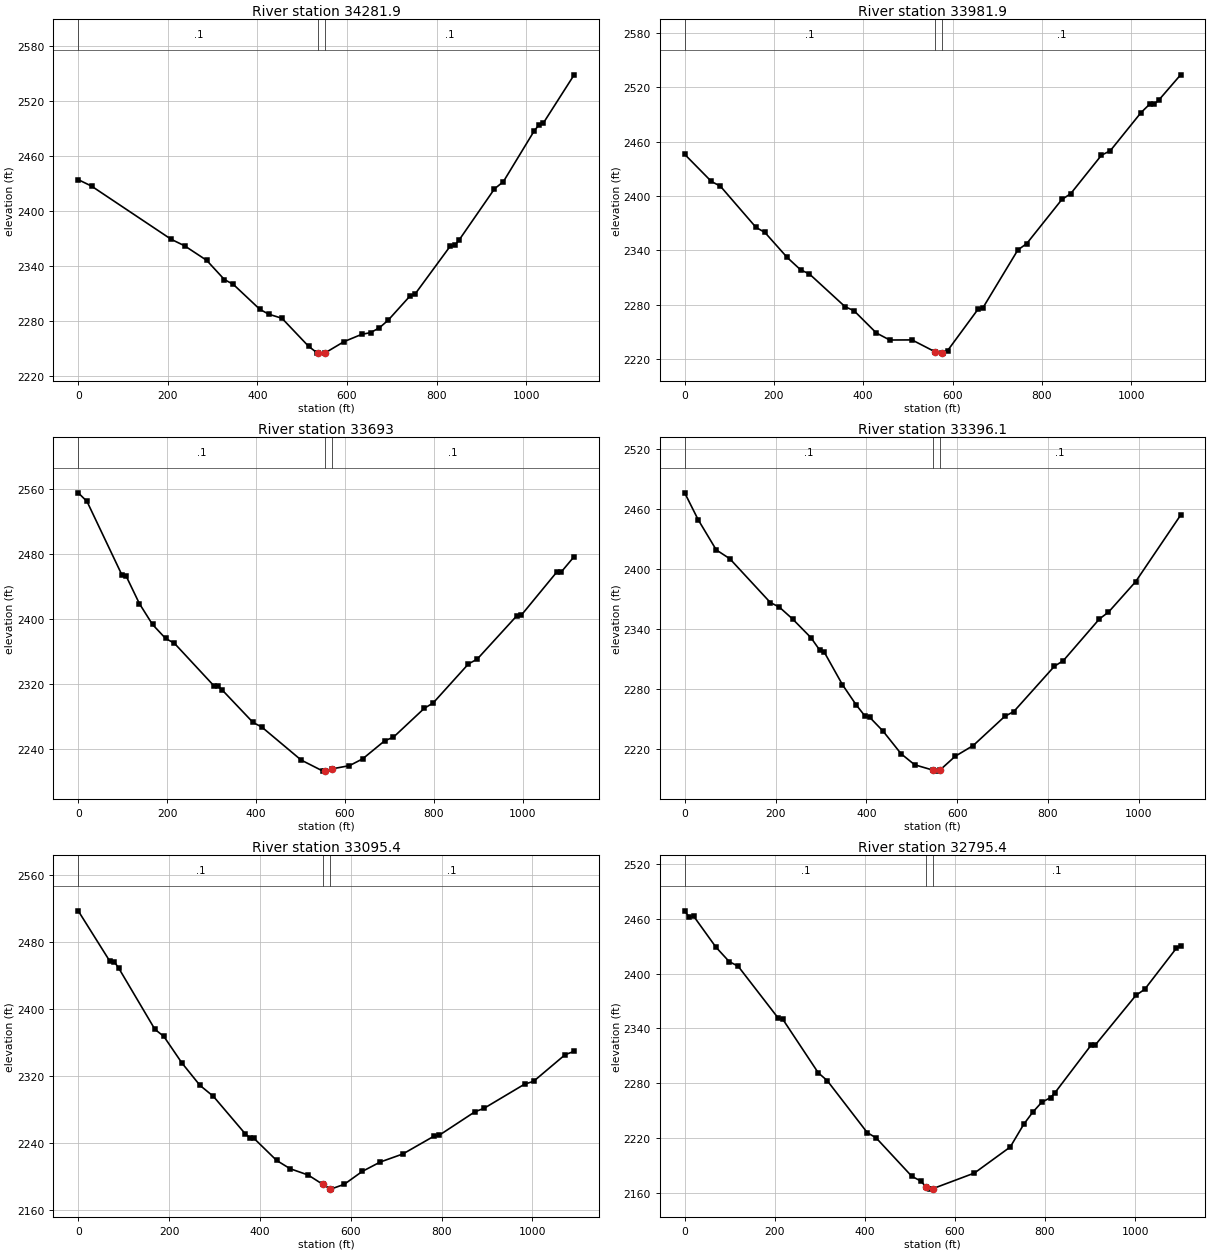
Type RM Length L Ch R = 1 ,34281.9 ,306,300,299.4
XS GIS Cut Line= 3
     1901945.772       213789.71     1901710.537      214280.039
      1901598.54      214832.004
#Sta/Elev= 30
       0 2434.11    29.7 2427.05   207.6 2369.01   237.3 2361.99   286.8 2346.07
   326.3 2325.12   346.1 2319.91   405.4 2292.68   425.2 2287.37   454.8  2282.9
   514.2 2252.35     534  2244.9   536.3 2244.95   551.3 2245.22   593.2 2257.41
   632.8 2265.39   652.5 2267.23   672.3 2272.52     692 2280.88   741.5  2307.7
   751.3 2308.92   830.4 2361.58   840.3 2362.36   850.2 2368.25   929.2 2424.06
     949 2431.89  1018.1 2487.46    1028 2493.45  1037.9 2495.54    1107  2548.4
#Mann= 3 , 0 , 0
       0      .1       0   536.3    .045       0   551.3      .1       0
Bank Sta=536.3,551.3
XS Rating Curve= 0 ,0
Exp/Cntr=0.3,0.1

Type RM Length L Ch R = 1 ,33981.9 ,293.5,288.7,284.5
XS GIS Cut Line= 3
      1901519.49      213725.736     1901414.771      214285.106
     1901321.373      214818.922
#Sta/Elev= 30
       0 2446.08    59.9 2416.04    79.9  2410.9   159.7 2365.36   179.7 2359.73
   229.6  2332.1   259.6 2318.44   279.6 2313.74   359.4 2277.61   379.4 2273.19
   429.3 2248.63   459.3 2240.83   509.2 2240.94   561.6 2227.62   576.6  2226.5
   578.9 2226.33   588.8 2228.99   657.8  2275.3   667.6 2275.99   746.4 2340.38
   766.2 2347.39     845 2396.17   864.7 2402.55   933.7 2445.09   953.4 2450.02
  1022.3 2492.21    1042 2501.68  1051.9 2501.66  1061.8 2505.83    1111 2533.95
#Mann= 3 , 0 , 0
       0      .1       0   561.6    .045       0   576.6      .1       0
Bank Sta=561.6,576.6
XS Rating Curve= 0 ,0
Exp/Cntr=0.3,0.1

Type RM Length L Ch R = 1 ,33693   ,304.9,296.7,288.2
XS GIS Cut Line= 3
     1900982.704      213687.755     1901135.341      214206.655
     1901142.831      214781.601
#Sta/Elev= 30
       0 2555.12    19.7  2544.6    98.3 2454.14   108.2 2452.31   137.7 2418.79
   167.2 2393.15   196.7 2375.92   216.4 2370.05   304.9 2317.94   314.7 2317.03
   324.5 2312.28   393.4  2272.6     413 2267.02   501.6  2226.4   550.8 2212.76
     556 2213.42     571 2215.53   610.3 2219.51     640 2227.84   689.6 2250.09
   709.4 2254.55   778.8 2290.08   798.6 2296.58     878 2344.62   897.8 2350.55
     987 2403.95   996.9 2404.54  1076.2 2457.25  1086.1 2457.28  1115.9 2476.68
#Mann= 3 , 0 , 0
       0      .1       0     556    .045       0     571      .1       0
Bank Sta=556,571
XS Rating Curve= 0 ,0
Exp/Cntr=0.3,0.1

Type RM Length L Ch R = 1 ,33396.1 ,298.8,300.6,302.4
XS GIS Cut Line= 3
     1900640.201       213794.91      1900850.34      214298.849
     1901057.266      214804.147
#Sta/Elev= 30
       0  2476.3    29.8 2449.27    69.5 2419.11    99.3 2410.26   188.6 2366.32
   208.5 2361.71   238.2 2349.57     278 2331.12   297.8 2318.32   307.7 2316.29
   347.4 2283.96   377.2 2264.01   397.1 2252.45     407 2251.46   436.8 2237.42
   476.5 2214.72   506.3  2203.7   546.1 2198.39   555.9 2197.32   561.1 2197.96
   595.6 2212.18   635.4    2223   704.8 2252.21   724.7 2257.04     814  2302.4
   833.9 2308.14   913.3 2349.93   933.2  2356.7   992.8 2387.13    1092 2453.93
#Mann= 3 , 0 , 0
       0      .1       0   546.1    .045       0   561.1      .1       0
Bank Sta=546.1,561.1
XS Rating Curve= 0 ,0
Exp/Cntr=0.3,0.1

Type RM Length L Ch R = 1 ,33095.4 ,299.5,300,302.5
XS GIS Cut Line= 3
     1900406.565      213894.666     1900573.949      214414.376
     1900741.334      214934.086
#Sta/Elev= 30
       0 2517.01    69.5 2456.97    79.4 2456.17    89.4 2448.41   168.8  2375.6
   188.6 2367.07   228.3 2335.43     268 2308.72   297.8 2295.47   367.3 2251.16
   377.2 2246.45   387.2 2245.34   436.8 2219.11   466.6  2209.2   506.3 2201.67
   538.5 2190.55   553.5 2185.36   555.9 2184.83   585.7 2190.55   625.4 2205.95
   665.1  2217.2   714.8 2226.78   784.2 2248.31   794.2 2248.91   873.6 2277.19
   893.4 2281.23   982.8  2310.1  1002.6 2313.48  1072.2 2345.32    1092 2349.29
#Mann= 3 , 0 , 0
       0      .1       0   538.5    .045       0   553.5      .1       0
Bank Sta=538.5,553.5
XS Rating Curve= 0 ,0
Exp/Cntr=0.3,0.1

Type RM Length L Ch R = 1 ,32795.4 ,303.1,307.4,309.8
XS GIS Cut Line= 3
     1900125.526      213951.285     1900283.365      214471.612
     1900396.458      215017.531
#Sta/Elev= 30
       0 2468.84     9.9 2461.94    19.8 2463.06    69.2 2429.15    98.9 2413.18
   118.6  2408.2   207.6 2351.35   217.5 2350.28   296.6 2291.37   316.4 2282.88
   405.3  2225.9   425.1 2220.06   504.2 2178.04     524 2172.84   536.2 2166.26
   543.7 2163.93   551.2 2164.49   643.3 2181.54   722.9  2210.1   752.8 2234.92
   772.7 2248.11   792.6    2259   812.5 2264.25   822.5 2269.76   902.1 2321.49
   912.1 2322.04  1001.7 2376.12  1021.6 2382.94  1091.3  2427.6  1101.2 2430.42
#Mann= 3 , 0 , 0
       0      .1       0   536.2    .045       0   551.2      .1       0
Bank Sta=536.2,551.2
XS Rating Curve= 0 ,0
Exp/Cntr=0.3,0.1

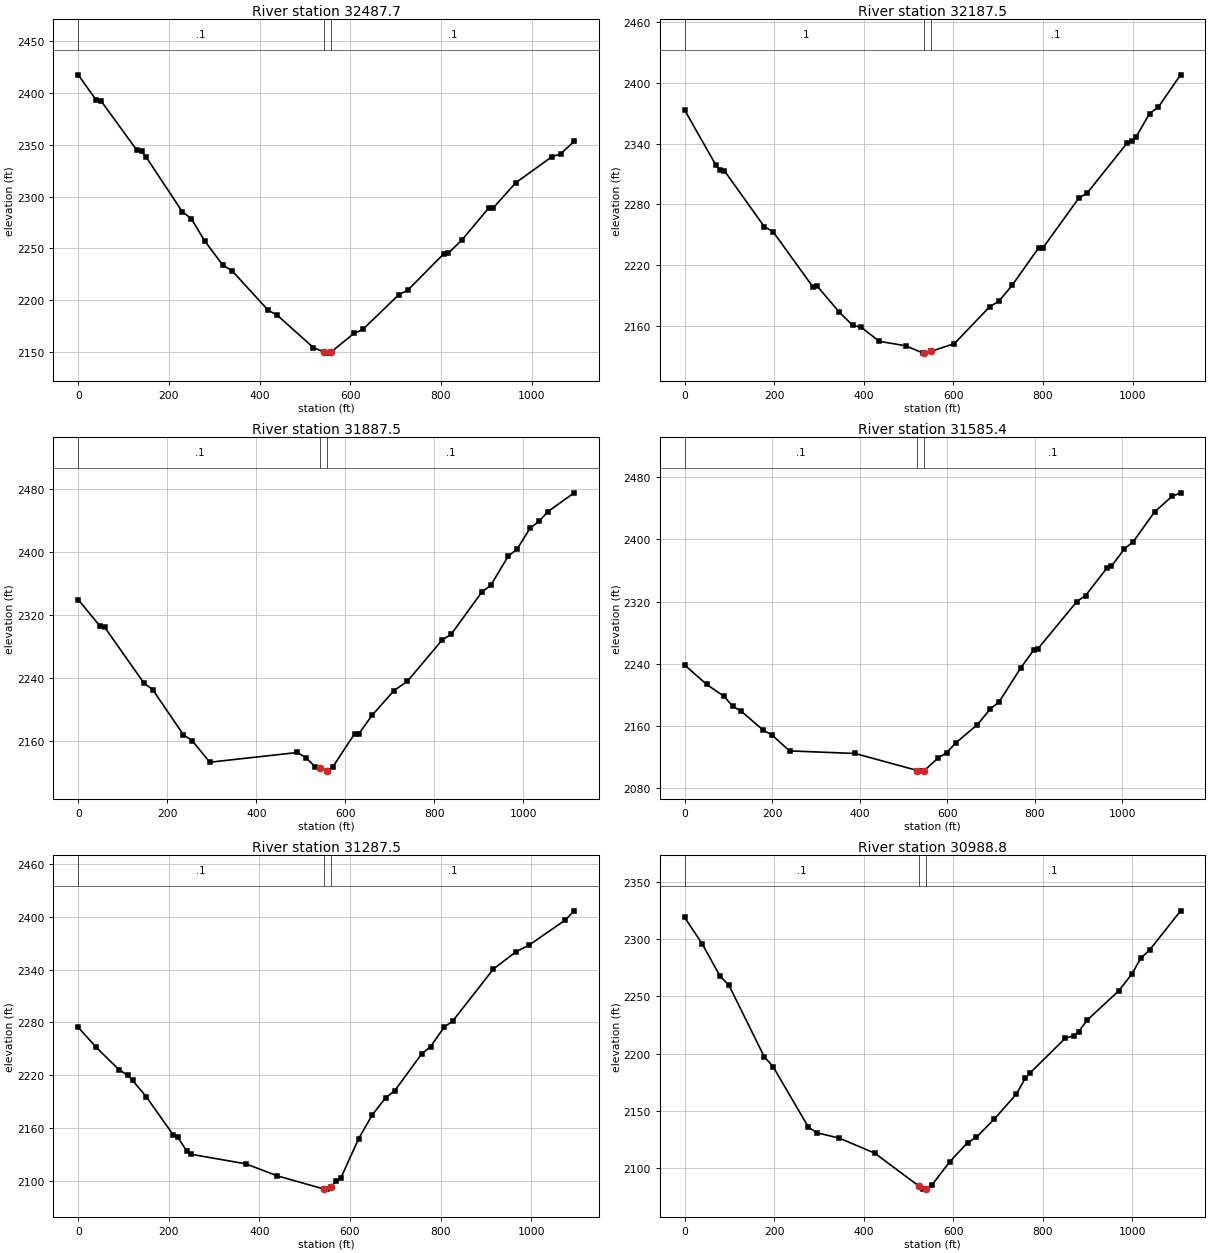
Type RM Length L Ch R = 1 ,32487.7 ,304.4,300.2,295.3
XS GIS Cut Line= 3
      1899941.69      214011.101     1899997.407      214556.675
     1900050.853      215099.324
#Sta/Elev= 30
       0 2417.53    39.9 2392.99    49.9 2392.63   129.6 2344.61   139.6 2343.76
   149.6  2338.3   229.3 2285.49   249.3  2278.7   279.2 2257.01   319.1 2233.67
     339 2228.51   418.8  2190.3   438.7 2185.56   518.5 2154.25     542 2149.84
   548.4 2148.87     557 2149.75   607.9 2167.83   627.7 2171.74     707 2205.26
   726.9 2209.71   806.2  2244.8   816.1 2245.36   845.8 2257.94   905.3 2288.95
   915.2 2288.98   964.8 2313.29  1044.1 2338.31  1063.9 2341.28  1093.7 2353.24
#Mann= 3 , 0 , 0
       0      .1       0     542    .045       0     557      .1       0
Bank Sta=542,557
XS Rating Curve= 0 ,0
Exp/Cntr=0.3,0.1

Type RM Length L Ch R = 1 ,32187.5 ,293.1,300,305.9
XS GIS Cut Line= 3
     1899541.006      214057.535      1899698.53      214576.823
     1899876.832      215112.482
#Sta/Elev= 30
       0 2373.11    69.1 2319.26    78.9 2313.83    88.8 2313.15   177.6 2258.12
   197.3  2253.1   286.1 2198.63     296 2199.17   345.3 2173.64   374.9 2160.74
   394.7  2158.5   434.1  2144.9   493.3 2140.42   532.8 2133.18   535.2 2133.35
   550.2 2135.02   602.1 2142.55   681.3 2179.16   701.1 2184.29   730.8 2199.96
   790.3 2237.17   800.2 2237.34   879.4  2285.9   899.2  2291.6   988.4 2340.96
   998.3 2342.53  1008.2 2347.02  1037.9 2369.68  1057.7 2376.28  1107.2 2407.95
#Mann= 3 , 0 , 0
       0      .1       0   535.2    .045       0   550.2      .1       0
Bank Sta=535.2,550.2
XS Rating Curve= 0 ,0
Exp/Cntr=0.3,0.1

Type RM Length L Ch R = 1 ,31887.5 ,319.1,302.1,286.7
XS GIS Cut Line= 3
     1899433.033      214080.798     1899425.209      214632.314
     1899449.714      215194.095
#Sta/Elev= 30
       0 2339.53    49.2 2305.62    59.1 2304.62   147.7 2233.25   167.4 2224.88
   236.4 2167.44   256.1  2159.9   295.5 2132.52   492.5 2144.93   512.2 2137.94
   531.9 2126.84   544.1 2125.22   559.1 2121.26   561.4 2121.19   571.3 2126.12
   620.6 2168.67   630.5 2169.03   660.1 2192.31   709.4 2223.81     739 2235.43
   817.9  2288.4   837.7  2295.4   906.7 2349.31   926.4 2357.64   965.9 2394.83
   985.6 2403.85  1015.2 2430.77    1035 2439.16  1054.7 2451.52  1113.9 2475.52
#Mann= 3 , 0 , 0
       0      .1       0   544.1    .045       0   559.1      .1       0
Bank Sta=544.1,559.1
XS Rating Curve= 0 ,0
Exp/Cntr=0.3,0.1

Type RM Length L Ch R = 1 ,31585.4 ,295.7,297.9,302.2
XS GIS Cut Line= 3
     1898773.085      214273.534     1899221.447      214769.624
      1899365.66      215210.826
#Sta/Elev= 30
       0 2238.21    49.9 2213.36    89.8 2197.86   109.8 2185.12   129.7 2178.44
   179.6  2154.2   199.6 2148.02   239.5 2127.59   389.2 2124.24   531.7  2102.3
   538.9 2101.52   546.7 2101.94   578.9 2118.52   598.8 2125.46   618.8 2137.72
   668.7 2161.51   698.3 2181.74   718.1 2190.64   767.4 2234.31   797.1  2257.5
     807 2259.28   895.8 2319.99   915.6 2327.74     965 2363.48   974.8 2365.46
  1004.5 2387.96  1024.2 2396.91  1073.6 2435.62  1113.1  2455.5  1132.8 2460.08
#Mann= 3 , 0 , 0
       0      .1       0   531.7    .045       0   546.7      .1       0
Bank Sta=531.7,546.7
XS Rating Curve= 0 ,0
Exp/Cntr=0.3,0.1

Type RM Length L Ch R = 1 ,31287.5 ,294.2,298.7,298.4
XS GIS Cut Line= 3
      1898583.51      214425.346     1898911.227         214867.
     1899195.367      215332.216
#Sta/Elev= 30
       0 2274.46      40 2251.56      90 2226.39     110 2219.79     120 2214.12
     150 2195.87     210 2152.23     220 2149.57     240 2133.72     250 2130.29
     370 2119.52     440 2105.82   542.3 2090.97     550 2090.81   557.3 2092.88
   569.8 2100.21   579.7 2103.14   619.3 2148.21   649.1  2174.8   678.8  2194.6
   698.6 2202.26   758.1 2244.08   777.9 2252.53   807.7 2274.32   827.5 2281.93
   916.7 2340.54   966.2 2359.96     996 2367.88  1075.3  2396.1  1095.1 2406.65
#Mann= 3 , 0 , 0
       0      .1       0   542.3    .045       0   557.3      .1       0
Bank Sta=542.3,557.3
XS Rating Curve= 0 ,0
Exp/Cntr=0.3,0.1

Type RM Length L Ch R = 1 ,30988.8 ,309.7,305.4,294
XS GIS Cut Line= 3
     1898417.018      214517.485     1898647.737      215008.648
     1899012.084      215440.433
#Sta/Elev= 30
       0 2318.83    39.5 2295.52    78.9 2267.62    98.7 2259.72   177.6 2197.35
   197.3 2188.67   276.3  2135.8     296  2130.8   345.3  2126.2   424.3 2113.12
   523.1 2084.34   532.8 2081.68   538.1 2081.75   552.6 2085.47   592.2 2105.71
   631.9 2122.32   651.7 2127.08   691.3 2142.73   740.9 2164.68   760.7 2178.45
   770.6 2182.78   849.9 2213.36   869.7 2215.73   879.6 2219.14   899.5 2229.42
   968.9 2254.59   998.6 2269.33  1018.4 2283.19  1038.2 2290.37  1107.6 2324.63
#Mann= 3 , 0 , 0
       0      .1       0   523.1    .045       0   538.1      .1       0
Bank Sta=523.1,538.1
XS Rating Curve= 0 ,0
Exp/Cntr=0.3,0.1

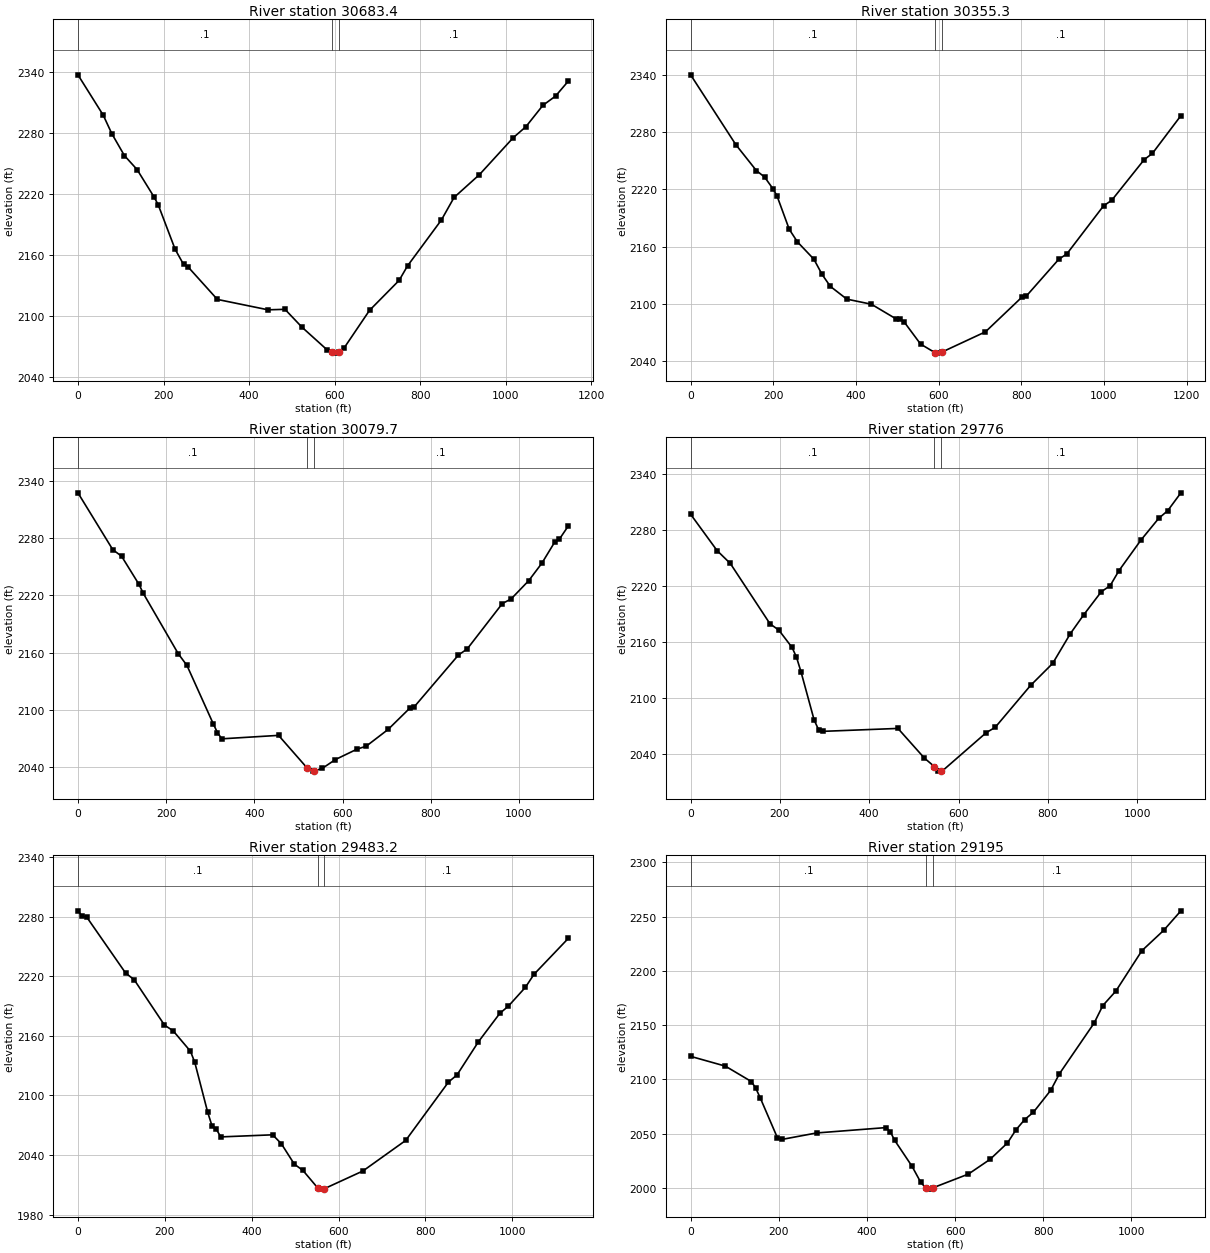
Type RM Length L Ch R = 1 ,30683.4 ,307.4,328.1,358.5
XS GIS Cut Line= 3
     1898082.242      214778.662     1898479.919      215230.982
     1898951.904      215500.196
#Sta/Elev= 30
       0 2337.32    59.2 2297.52      79  2279.5   108.6 2257.78   138.2 2244.01
   177.7  2217.1   187.6  2209.3   227.1 2165.49   246.8 2150.57   256.7  2148.4
   325.8 2116.08   444.3 2105.84   483.8 2106.33   523.3 2088.81   582.5  2066.3
   594.8 2063.91   602.3 2063.18   609.8 2063.98     622 2068.29   681.3 2105.28
   750.5 2134.82   770.2 2149.16   849.3 2194.35   878.9 2216.53   938.2 2239.02
  1017.2 2275.41  1046.8 2286.25  1086.4 2307.24    1116 2316.39  1145.6    2331
#Mann= 3 , 0 , 0
       0      .1       0   594.8    .045       0   609.8      .1       0
Bank Sta=594.8,609.8
XS Rating Curve= 0 ,0
Exp/Cntr=0.3,0.1

Type RM Length L Ch R = 1 ,30355.3 ,300.3,275.2,254
XS GIS Cut Line= 4
     1898025.128      214820.917     1898270.743      215287.063
     1898235.557      215419.597     1898378.923      215921.614
#Sta/Elev= 30
       0    2340   109.4 2266.76   159.1 2239.62     179 2232.81   198.8 2220.79
   208.8  2213.3   238.6 2178.06   258.5 2164.82   298.2 2146.72   318.1 2130.71
     338 2118.24   377.8 2104.89   437.4 2099.52   497.1 2084.15     507 2083.94
     517 2080.71   556.3 2057.77   592.1 2048.55   595.5 2048.28   607.1  2049.2
   713.3 2070.61   801.9 2107.14   811.8 2107.93   890.6 2146.63   910.3 2152.36
   998.9 2202.64  1018.6 2208.42  1097.4 2251.16  1117.2 2257.65  1186.1  2297.2
#Mann= 3 , 0 , 0
       0      .1       0   592.1    .045       0   607.1      .1       0
Bank Sta=592.1,607.1
XS Rating Curve= 0 ,0
Exp/Cntr=0.3,0.1

Type RM Length L Ch R = 1 ,30079.7 ,297.7,303.7,302.3
XS GIS Cut Line= 3
     1897633.827      215097.311     1898041.112      215457.787
     1898310.509      215957.649
#Sta/Elev= 30
       0 2327.42    79.1 2267.87    98.9 2261.12   138.4 2231.62   148.3 2222.12
   227.4 2159.09   247.2 2146.74   306.6 2085.92   316.4 2076.42   326.3 2069.95
   454.9 2073.56   520.5    2039     534 2036.14   535.5 2036.32   553.9 2038.97
   583.8 2048.24   633.6 2059.31   653.5 2062.17   703.3 2079.76   753.1 2102.32
   763.1 2103.72   862.7 2157.62   882.6 2163.99   962.3 2211.52   982.2 2216.34
  1022.1 2235.44    1052 2253.77  1081.8 2276.39  1091.8    2279  1111.7 2292.58
#Mann= 3 , 0 , 0
       0      .1       0   520.5    .045       0   535.5      .1       0
Bank Sta=520.5,535.5
XS Rating Curve= 0 ,0
Exp/Cntr=0.3,0.1

Type RM Length L Ch R = 1 ,29776   ,293.4,292.8,295
XS GIS Cut Line= 3
     1897508.792      215191.664     1897815.031       215652.44
     1898182.271      216054.737
#Sta/Elev= 30
       0 2296.82    59.3 2257.81    88.9    2244   177.8  2179.2   197.6 2172.45
   227.2 2153.82   237.1 2143.35     247 2128.03   276.6    2076   286.5  2065.6
   296.4 2063.79   464.3 2066.92   523.6 2035.03   545.8 2026.02   553.3 2021.58
   560.8  2021.2   563.2 2021.08   662.2 2062.45     682 2068.02   761.2 2113.01
   810.8  2136.7   850.4 2168.64   880.1 2188.74   919.7 2213.67   939.5  2220.1
   959.3 2236.31  1008.8  2269.3  1048.4  2292.5  1068.3 2300.58    1098 2319.84
#Mann= 3 , 0 , 0
       0      .1       0   545.8    .045       0   560.8      .1       0
Bank Sta=545.8,560.8
XS Rating Curve= 0 ,0
Exp/Cntr=0.3,0.1

Type RM Length L Ch R = 1 ,29483.2 ,301.6,288,280
XS GIS Cut Line= 3
     1897426.387      215232.869     1897539.936      215758.846
     1897891.985      216233.301
#Sta/Elev= 30
       0 2285.83      10 2280.13    19.9 2279.74   109.6 2223.28   129.5 2216.46
   199.3 2170.73   219.2 2165.02   259.1 2144.41     269 2133.29   298.9 2082.79
   308.9 2069.07   318.9 2065.69   328.8 2058.15   448.4 2060.26   468.3 2051.32
   498.2 2030.76   518.2 2024.32   552.3 2006.68   557.8 2005.56   567.3 2005.97
   656.2 2023.83   754.7  2054.6   853.2 2113.38   872.9 2120.59   922.1 2153.92
   971.4 2182.57     991 2189.78  1030.4 2208.83  1050.1 2221.89  1128.9 2257.98
#Mann= 3 , 0 , 0
       0      .1       0   552.3    .045       0   567.3      .1       0
Bank Sta=552.3,567.3
XS Rating Curve= 0 ,0
Exp/Cntr=0.3,0.1

Type RM Length L Ch R = 1 ,29195   ,292.5,299.9,301.1
XS GIS Cut Line= 3
     1896854.397      215789.462     1897360.418      215982.649
     1897837.056      216296.489
#Sta/Elev= 30
       0 2121.24    78.8 2112.24   137.9 2098.03   147.7 2091.97   157.6 2083.32
     197 2046.19   206.8 2044.72   285.6 2050.69   443.2 2055.64     453 2051.83
   462.9 2043.92   502.2 2020.08     522  2005.3   534.1 1999.75   541.6 1998.98
   549.1 2000.09   630.2 2012.84   679.4 2026.42   718.8  2041.5   738.4 2053.74
   758.1 2063.09   777.8 2069.83   817.2 2090.13   836.8 2105.27   915.5 2151.94
   935.2 2168.03   964.7 2181.34  1023.8 2218.53    1073 2237.16  1112.3 2255.24
#Mann= 3 , 0 , 0
       0      .1       0   534.1    .045       0   549.1      .1       0
Bank Sta=534.1,549.1
XS Rating Curve= 0 ,0
Exp/Cntr=0.3,0.1

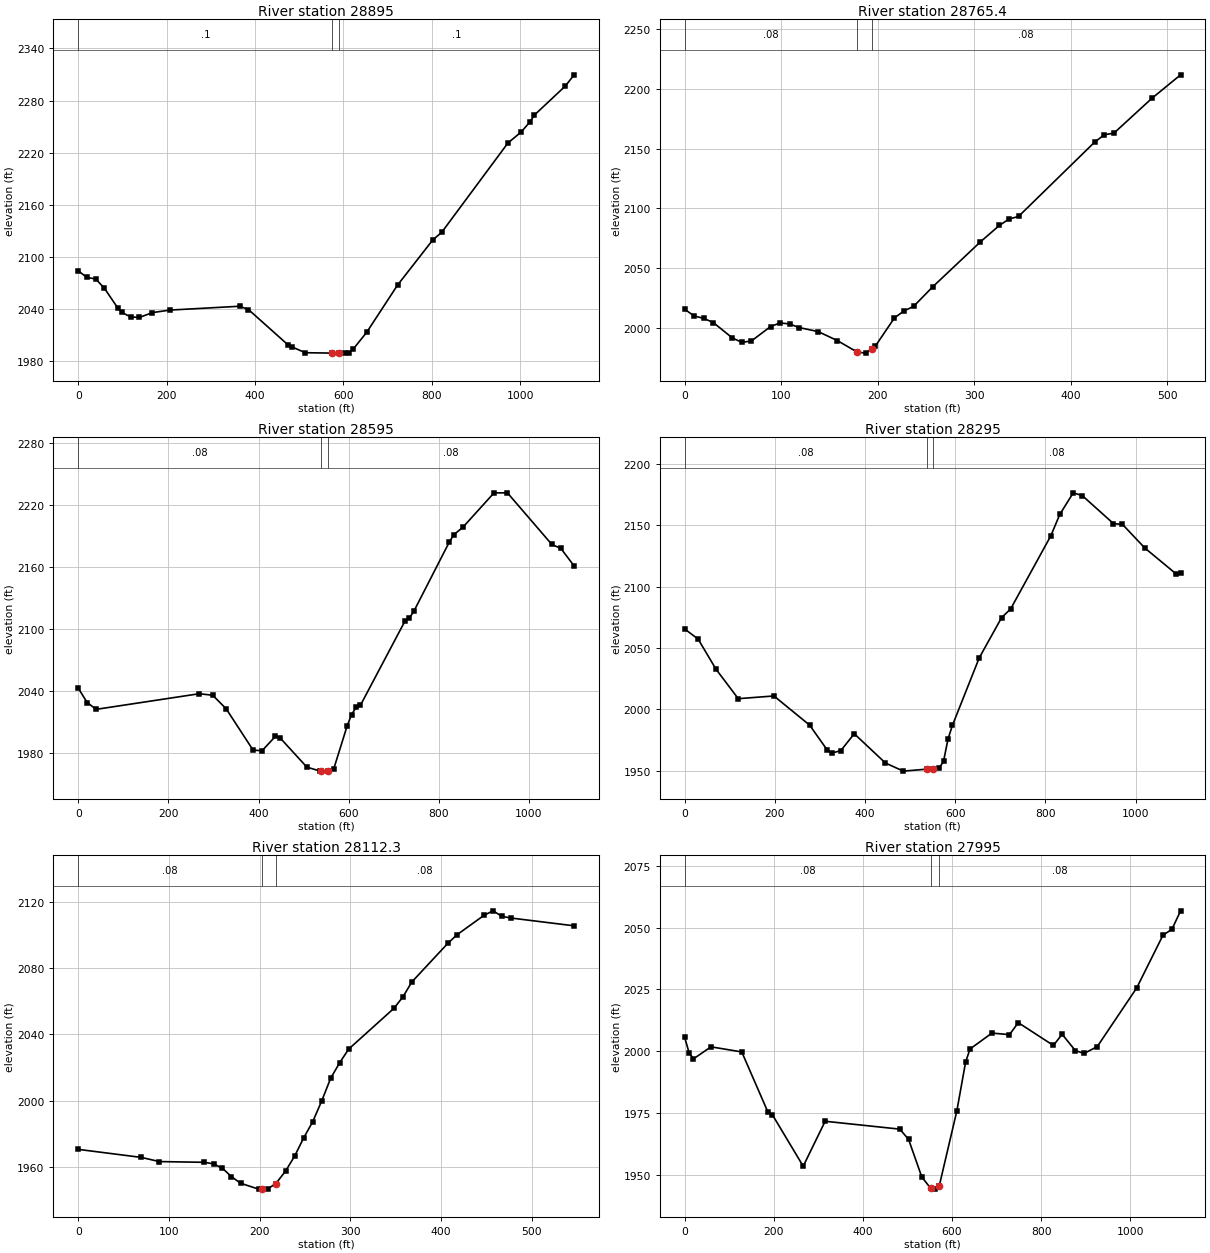
Type RM Length L Ch R = 1 ,28895   ,119.6,129.6,141.1
XS GIS Cut Line= 3
     1896804.181       215887.19     1897251.926      216260.084
     1897688.271      216577.402
#Sta/Elev= 30
       0 2083.89    19.8 2076.23    39.5 2074.56    59.3  2063.8    88.9 2041.54
    98.8 2036.02   118.5 2030.77   138.3 2030.18   167.9 2035.78   207.4 2038.67
   365.4  2043.1   385.2 2039.31     474 1998.94   483.9 1996.23   513.6 1989.57
   575.2  1989.1   590.2  1989.1   602.7 1989.09   612.7 1989.63   622.6 1993.97
   652.6 2012.95   722.6 2067.47   802.5  2119.6   822.5 2128.22   972.4 2231.18
  1002.3 2243.77  1022.3 2255.52  1032.3 2263.35  1102.2 2296.74  1122.2 2309.67
#Mann= 3 , 0 , 0
       0      .1       0   575.2    .045       0   590.2      .1       0
Bank Sta=575.2,590.2
XS Rating Curve= 0 ,0
Exp/Cntr=0.3,0.1

Type RM Length L Ch R = 1 ,28765.4 ,172.2,170.4,169.2
XS GIS Cut Line= 2
     1897083.775       216181.23     1897299.906      216647.263
#Sta/Elev= 30
       0 2015.25     9.9 2009.72    19.8 2007.63    29.6 2004.22    49.4 1991.28
    59.3 1987.56    69.2  1988.8    88.9  2000.8    98.8  2003.9   108.7 2002.99
   118.6 1999.98   138.3 1996.62   158.1 1989.09   178.7 1979.46   187.7 1978.57
   193.7 1982.21   197.6 1984.58   217.3  2008.1   227.2 2013.94   237.1 2017.73
   256.9  2034.1   306.2 2071.71     326 2085.58   335.9 2090.92   345.8  2093.1
   424.8  2155.5   434.7 2161.56   444.6  2162.9   484.1  2192.2   513.7 2211.77
#Mann= 3 , 0 , 0
       0     .08       0   178.7    .045       0   193.7     .08       0
Bank Sta=178.7,193.7
XS Rating Curve= 0 ,0
Exp/Cntr=0.3,0.1

Type RM Length L Ch R = 1 ,28595   ,309.2,300,291.6
XS GIS Cut Line= 3
     1896735.477      215938.509     1897004.821       216414.67
     1897262.599      216904.124
#Sta/Elev= 30
       0 2042.59    19.9 2028.62    39.8 2022.02   268.6 2037.14   298.4 2035.66
   328.2 2022.58   387.9 1982.59   407.8 1981.94   437.6 1995.95   447.6 1994.51
   507.3 1966.09   537.1 1962.24   539.6 1962.26   554.6 1962.35   566.8 1964.32
   596.4 2005.73   606.3 2016.84   616.2 2023.85   626.1 2025.96   724.9 2107.45
   734.8 2110.42   744.6 2116.94   823.6 2184.23   833.5 2191.12   853.3 2198.19
   922.4 2231.48   952.1 2231.54  1050.8 2181.54  1070.6  2177.8  1100.2 2160.76
#Mann= 3 , 0 , 0
       0     .08       0   539.6    .045       0   554.6     .08       0
Bank Sta=539.6,554.6
XS Rating Curve= 0 ,0
Exp/Cntr=0.3,0.1

Type RM Length L Ch R = 1 ,28295   ,186.4,182.7,177.7
XS GIS Cut Line= 3
     1896338.111      216268.756     1896772.644      216596.538
     1897193.808      216958.982
#Sta/Elev= 30
       0 2065.49    29.7 2057.34    69.3 2032.86   118.8 2008.76   197.9 2010.97
   277.1 1987.23   316.7 1966.68   326.6 1964.42   346.4  1966.5   376.1  1980.2
   445.3 1956.36   484.9 1949.75   536.8 1951.35   551.8 1951.49   564.1    1952
   574.1 1957.66     584 1975.77   593.9 1987.08   653.4 2042.07     703 2074.82
   722.9  2081.8   812.2 2141.47     832 2158.82   861.8 2176.42   881.7 2174.21
   951.1 2151.34     971 2150.73  1020.6 2131.48    1090 2110.39    1100 2110.84
#Mann= 3 , 0 , 0
       0     .08       0   536.8    .045       0   551.8     .08       0
Bank Sta=536.8,551.8
XS Rating Curve= 0 ,0
Exp/Cntr=0.3,0.1

Type RM Length L Ch R = 1 ,28112.3 ,109,117.2,121.3
XS GIS Cut Line= 2
     1896491.103      216652.329     1896974.021      216908.984
#Sta/Elev= 30
       0  1970.8    69.6 1965.96    89.5 1963.45   139.2 1963.01   149.2 1962.09
   159.1 1959.38     169 1954.38     179 1950.42   198.9 1946.86     203 1946.91
   208.8 1946.97     218 1950.23   228.7 1957.78   238.6 1966.68   248.6 1977.69
   258.5 1987.35   268.5 1999.94   278.4 2013.63   288.4 2023.06   298.3 2031.21
     348 2055.65     358 2062.56   367.9  2071.6   407.7 2094.92   417.6 2099.98
   447.4  2111.7   457.4 2114.44   467.3 2111.12   477.3  2110.1   546.9 2105.41
#Mann= 3 , 0 , 0
       0     .08       0     203    .045       0     218     .08       0
Bank Sta=203,218
XS Rating Curve= 0 ,0
Exp/Cntr=0.3,0.1

Type RM Length L Ch R = 1 ,27995   ,289.3,304.6,324
XS GIS Cut Line= 3
     1896229.453      216412.079      1896604.42      216843.192
     1897029.385      217178.829
#Sta/Elev= 30
       0 2005.56     9.8 1999.41    19.7 1996.89    59.1 2001.75   128.1 1999.69
   187.2 1975.17     197  1974.2     266 1953.41   315.2 1971.62   482.7 1968.43
   502.4  1964.3     532  1949.1   551.7 1944.53   561.5 1944.14   571.4 1945.55
   610.8 1975.86   630.4 1995.58   640.3 2000.88   689.5 2007.32   728.9 2006.69
   748.6 2011.54   827.4 2002.31     847 2006.84   876.6 2000.25   896.3 1999.08
   925.8 2001.84  1014.4 2025.62  1073.5 2047.01  1093.2 2049.29  1112.9 2056.82
#Mann= 3 , 0 , 0
       0     .08       0   551.7    .045       0   571.4     .08       0
Bank Sta=551.7,571.4
XS Rating Curve= 0 ,0
Exp/Cntr=0.3,0.1

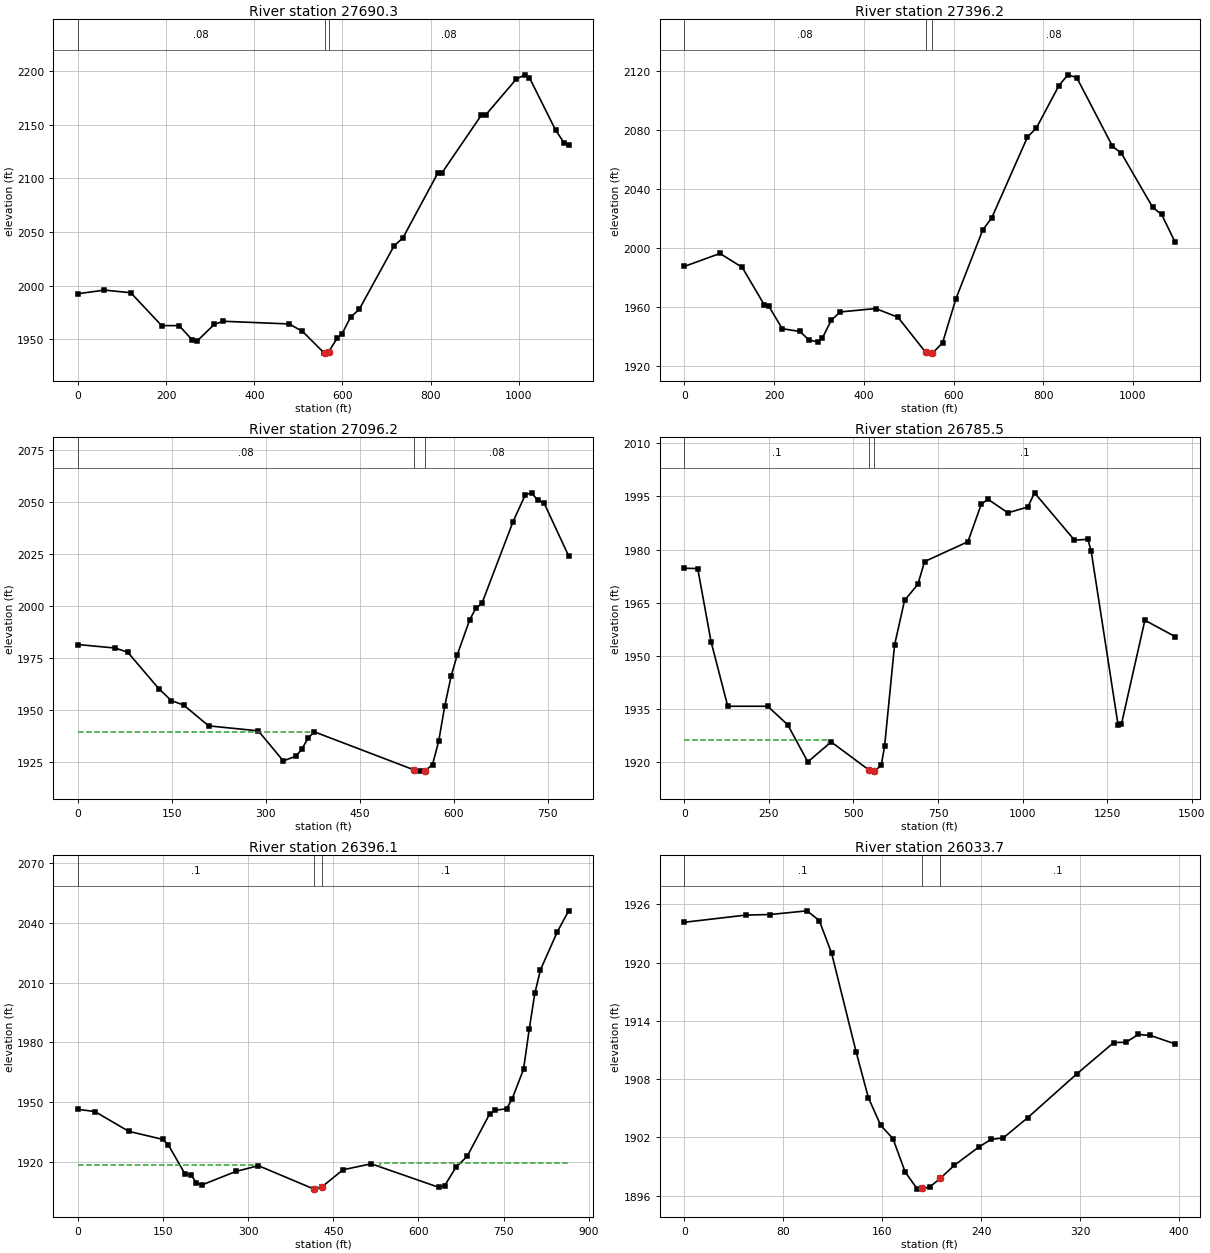
Type RM Length L Ch R = 1 ,27690.3 ,293.1,294,292.8
XS GIS Cut Line= 3
      1896155.72      216455.533     1896344.888       216928.39
     1896370.059      217531.607
#Sta/Elev= 30
       0 1992.38    59.9 1995.78   119.8 1993.31   189.7 1962.72   229.7 1962.62
   259.6 1949.08   269.6 1948.07   309.6 1963.98   329.5 1966.73   479.3 1964.22
   509.3 1957.26   558.8 1937.03   559.3 1937.09   568.7 1938.27   588.5 1951.41
   598.4 1954.52   618.2 1970.45     638 1977.84   717.1 2037.07   736.9 2044.32
   816.1 2104.75     826 2105.23   915.1 2158.92     925 2159.09   994.3  2192.5
  1014.1 2196.42    1024 2193.78  1083.3 2144.95  1103.1 2132.68    1113 2131.28
#Mann= 3 , 0 , 0
       0     .08       0   559.3    .045       0   568.7     .08       0
Bank Sta=559.3,568.7
XS Rating Curve= 0 ,0
Exp/Cntr=0.3,0.1

Type RM Length L Ch R = 1 ,27396.2 ,299.1,299.9,302.7
XS GIS Cut Line= 3
     1896055.239      216466.559     1896055.258      217012.143
     1896107.046      217558.052
#Sta/Elev= 30
       0 1987.38    79.4 1996.16     129 1986.74   178.6 1961.09   188.5 1960.27
   218.2 1945.16   257.9 1943.26   277.8 1937.42   297.6 1936.28   307.5 1938.76
   327.4 1950.83   347.2 1956.51   426.6 1958.81   476.2  1952.9   538.1 1929.04
   553.1 1928.59   575.5  1935.5   605.4 1965.45   665.2 2012.13   685.2 2020.31
   764.9 2075.11   784.9 2081.33   834.7 2109.82   854.7 2117.28   874.6 2115.44
   954.4 2068.86   974.3 2064.06  1044.1 2027.38    1064 2022.59  1093.9 2003.85
#Mann= 3 , 0 , 0
       0     .08       0   538.1    .045       0   553.1     .08       0
Bank Sta=538.1,553.1
XS Rating Curve= 0 ,0
Exp/Cntr=0.3,0.1

Type RM Length L Ch R = 1 ,27096.2 ,310.3,310.8,311.6
XS GIS Cut Line= 3
     1895777.974      216492.098      1895763.65      217038.204
     1895759.972      217275.394
#Sta/Elev= 30
       0 1981.53    59.6 1979.85    79.5 1977.82   129.1 1960.28     149 1954.55
   168.8 1952.41   208.6 1942.38     288 1939.98   327.8 1925.52   347.6 1927.74
   357.6 1931.14   367.5 1936.57   377.4 1939.51   536.4 1921.21   546.3 1920.59
   553.8 1920.68   566.1 1923.71     576 1935.04   585.8 1952.16   595.7 1966.18
   605.6 1976.55   625.4  1993.4   635.2 1998.93   645.1 2001.42   694.6 2040.64
   714.3 2053.65   724.2 2054.58   734.1 2051.02     744 2049.82   783.5 2024.18
#Mann= 3 , 0 , 0
       0     .08       0   536.4    .045       0   553.8     .08       0
#XS Ineff= 2 , 0
          374.24 1939.54
Permanent Ineff=
       F       F
Bank Sta=536.4,553.8
XS Rating Curve= 0 ,0
Exp/Cntr=0.3,0.1

Type RM Length L Ch R = 1 ,26785.5 ,388,388.9,389.5
XS GIS Cut Line= 4
     1895483.217      216448.015     1895450.356      217108.216
      1895882.05      217419.201     1895708.832      217610.338
#Sta/Elev= 30
       0 1974.71    39.5 1974.63    78.9 1954.02   128.3  1935.8   246.6  1935.8
   305.8 1930.55     365 1920.12   434.1 1925.74   546.4 1917.79   561.4 1917.52
   562.4 1917.51   582.1 1919.16     592 1924.48   621.6 1953.11   651.2 1965.67
   690.6  1970.2   710.3  1976.6   838.4 1982.19   877.8 1992.73   897.5 1994.19
   956.6 1990.34  1015.7 1991.99  1035.4 1995.98  1153.6 1982.63  1193.1 1982.88
    1203  1979.5  1282.4 1930.55  1292.3 1930.71  1361.7 1960.06    1451 1955.45
#Mann= 3 , 0 , 0
       0      .1       0   546.4    .045       0   561.4      .1       0
#XS Ineff= 2 , 0
          425.76 1926.23
Permanent Ineff=
       F       F
Bank Sta=546.4,561.4
XS Rating Curve= 0 ,0
Exp/Cntr=0.3,0.1

Type RM Length L Ch R = 1 ,26396.1 ,361.5,362.4,363.4
XS GIS Cut Line= 2
     1895126.462      216535.193     1895051.799      217396.803
#Sta/Elev= 30
       0 1946.31    29.8 1945.24    89.5 1935.28   149.1 1931.28     159 1928.63
   188.9 1913.74   198.8 1913.55   208.8 1909.46   218.7 1908.38   278.3 1915.14
   318.1 1918.03   415.6 1906.33   417.5 1906.26   430.6 1907.54   467.2    1916
   516.9 1918.97   636.2 1907.14   646.1 1907.89     666 1917.22   685.9 1922.73
   725.7 1944.08   735.6 1945.88   755.5 1946.63   765.4 1951.74   785.3 1966.47
   795.2 1986.44   805.2 2004.63   815.1 2016.41     845 2035.62   864.8 2046.04
#Mann= 3 , 0 , 0
       0      .1       0   415.6    .045       0   430.6      .1       0
#XS Ineff= 2 , 0
          310.32 1918.16  532.97         1919.39
Permanent Ineff=
       F       F
Bank Sta=415.6,430.6
XS Rating Curve= 0 ,0
Exp/Cntr=0.3,0.1

Type RM Length L Ch R = 1 ,26033.7 ,177.2,179.3,181.4
XS GIS Cut Line= 2
     1894827.148      216559.517       1894779.5      216953.528
#Sta/Elev= 26
       0 1924.16    49.6  1924.9    69.4 1924.96    99.2 1925.34   109.1 1924.34
   119.1 1920.97   138.9 1910.82   148.8  1906.1   158.8 1903.24   168.7 1901.88
   178.6 1898.43   188.5 1896.67   192.1 1896.75   198.4 1896.88   207.1 1897.79
   218.3 1899.12   238.1    1901     248 1901.79     258 1901.95   277.8 1904.04
   317.5 1908.55   347.3 1911.77   357.2  1911.8   367.1  1912.6     377  1912.5
   396.9 1911.63
#Mann= 3 , 0 , 0
       0      .1       0   192.1    .045       0   207.1      .1       0
Bank Sta=192.1,207.1
XS Rating Curve= 0 ,0
Exp/Cntr=0.3,0.1

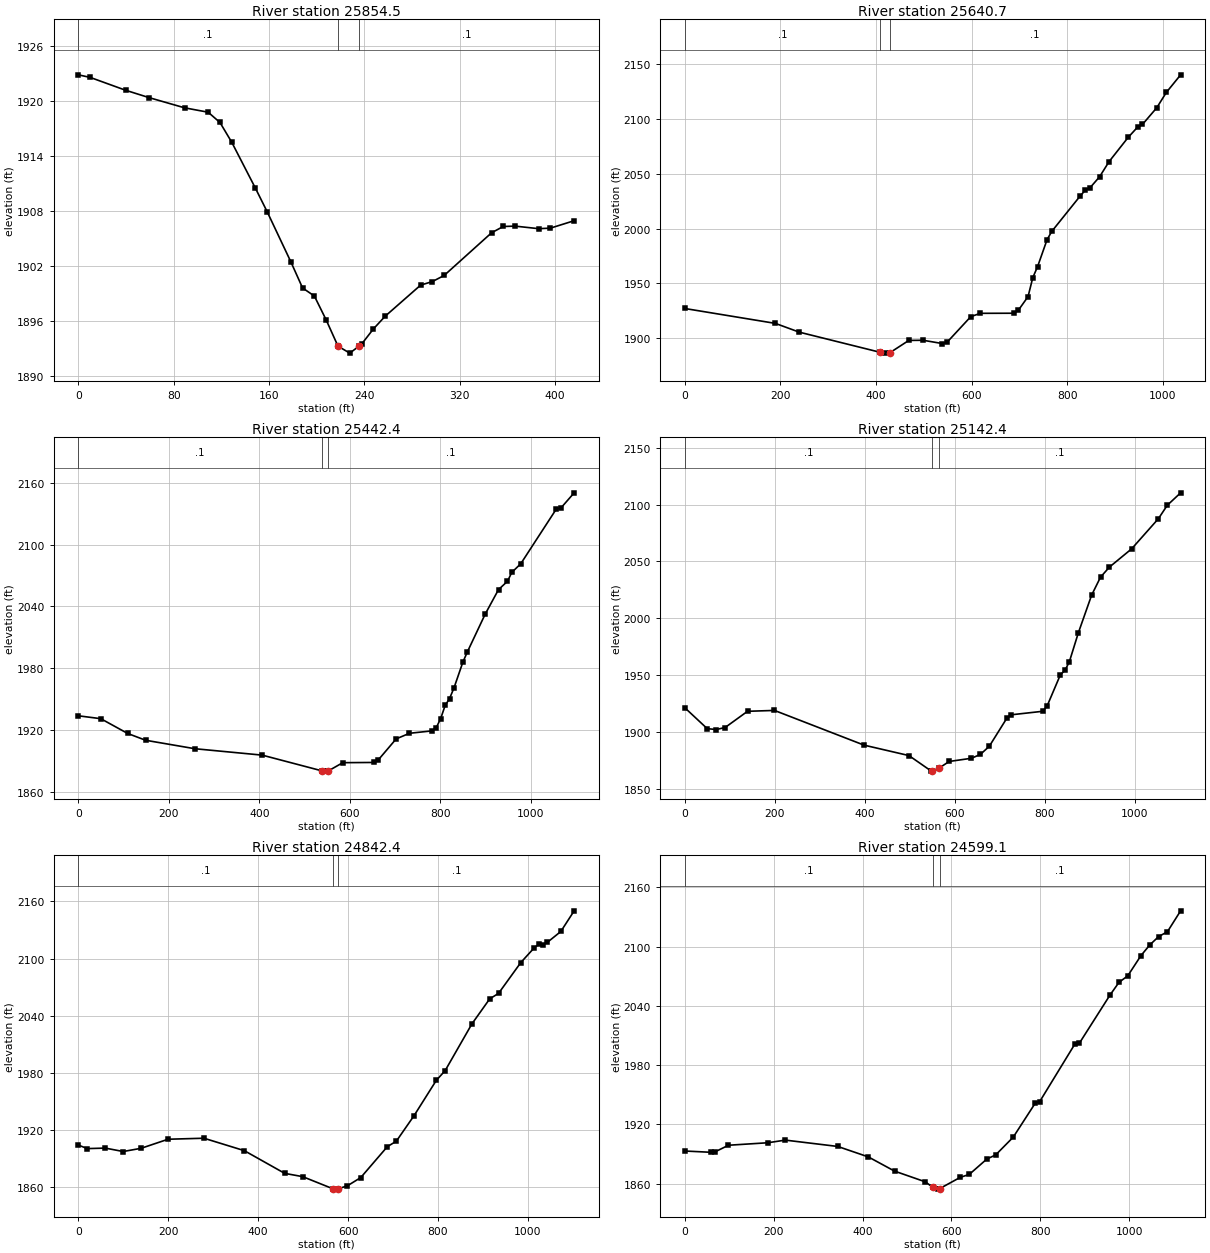
Type RM Length L Ch R = 1 ,25854.5 ,202.9,213.7,224.5
XS GIS Cut Line= 2
     1894675.041      216519.199     1894588.909      216926.038
#Sta/Elev= 29
       0  1922.9     9.9 1922.62    39.6 1921.22    59.4 1920.41    89.1  1919.3
   108.9 1918.82   118.8  1917.7   128.7 1915.54   148.5 1910.54   158.4 1907.96
   178.2 1902.51   188.1 1899.64     198 1898.76   207.9 1896.15   217.8 1893.29
   227.7 1892.53   235.2 1893.27   237.6 1893.51   247.5 1895.17   257.4 1896.56
   287.1 1899.95     297 1900.34   306.9 1901.01   346.6 1905.66   356.4 1906.35
   366.4 1906.39   386.2 1906.11     396 1906.17   415.9 1906.98
#Mann= 3 , 0 , 0
       0      .1       0   217.8    .045       0   235.2      .1       0
Bank Sta=217.8,235.2
XS Rating Curve= 0 ,0
Exp/Cntr=0.3,0.1

Type RM Length L Ch R = 1 ,25640.7 ,202.2,198.2,196.8
XS GIS Cut Line= 3
     1894676.145      216422.334     1894399.866      216763.255
     1894066.664      217260.807
#Sta/Elev= 30
       0 1927.01   189.5 1913.41   239.4 1905.41   409.5 1886.91   418.9 1886.23
   428.8  1886.5   468.8 1897.84   498.7 1897.98   538.6 1895.01   548.6 1896.06
   598.5 1919.58   618.5  1922.6   688.3 1922.69   698.3 1925.58   718.3 1937.88
   728.2 1955.18   738.2  1965.2   758.2 1990.02   768.2 1997.59     828 2030.14
     838 2035.06     848 2037.33     868 2047.38   887.9 2061.25   927.8 2083.36
   947.8 2092.88   957.8 2095.24   987.7 2110.47  1007.7 2124.45  1037.6 2140.53
#Mann= 3 , 0 , 0
       0      .1       0   409.5    .045       0   428.8      .1       0
Bank Sta=409.5,428.8
XS Rating Curve= 0 ,0
Exp/Cntr=0.3,0.1

Type RM Length L Ch R = 1 ,25442.4 ,296.9,299.9,295.8
XS GIS Cut Line= 3
     1894497.061      216188.274     1894233.404       216665.41
     1893916.513      217116.037
#Sta/Elev= 30
       0 1933.71    49.6 1930.92     109 1916.56   148.7 1909.94   257.7 1901.71
   406.4 1895.49   537.6 1880.31   545.1 1879.94   552.6 1880.16   584.5 1888.15
   653.4 1888.37   663.2 1890.93   702.5 1911.25     732 1916.72   781.2 1919.04
   791.1 1922.13   800.9 1930.96   810.8 1943.73   820.6 1950.51   830.4 1960.84
   850.1    1986   859.9 1995.78   899.3 2032.48   928.8 2056.38   948.5  2064.4
   958.3 2073.18     978 2081.49  1056.7 2134.78  1066.5 2135.58    1096 2150.42
#Mann= 3 , 0 , 0
       0      .1       0   537.6    .045       0   552.6      .1       0
Bank Sta=537.6,552.6
XS Rating Curve= 0 ,0
Exp/Cntr=0.3,0.1

Type RM Length L Ch R = 1 ,25142.4 ,300.9,300,302.8
XS GIS Cut Line= 3
     1894299.144      216083.255     1893965.706      216530.437
     1893738.638      217024.688
#Sta/Elev= 30
       0 1921.17    49.8 1902.78    69.7 1901.98    89.6 1903.77   139.4 1918.04
   199.2 1918.81   398.4 1888.24     498 1879.07   547.8 1865.37   550.3  1865.6
   565.3 1868.12   587.5 1873.88   636.9 1876.69   656.7 1880.07   676.5  1887.2
     716 1912.26   725.9 1914.99   795.2 1918.04     805 1922.68   834.7 1950.36
   844.6 1953.99   854.5 1961.71   874.3 1986.95   903.9 2020.26   923.7 2036.13
   943.5 2044.99   992.9 2061.08  1052.3  2087.6  1072.1 2099.43  1101.7 2110.37
#Mann= 3 , 0 , 0
       0      .1       0   550.3    .045       0   565.3      .1       0
Bank Sta=550.3,565.3
XS Rating Curve= 0 ,0
Exp/Cntr=0.3,0.1

Type RM Length L Ch R = 1 ,24842.4 ,252.8,243.4,235
XS GIS Cut Line= 3
     1894035.533      215920.454     1893717.793      216380.201
     1893428.758      216841.103
#Sta/Elev= 30
       0  1904.5      20 1900.78    59.9 1901.32    99.8 1897.73   139.7 1901.11
   199.6 1910.61   279.4 1911.67   369.2 1898.63   459.1  1874.8     499 1871.38
   566.4 1858.63   568.8 1858.28   578.6 1858.73   598.4 1861.75   628.1 1870.35
   687.4 1902.86   707.2 1908.47   746.8 1935.36   796.3 1972.38     816 1982.62
   875.4 2031.54     915 2057.82   934.7 2063.59   984.2  2095.9  1013.9  2111.3
  1023.8 2114.94  1033.6 2114.71  1043.5 2117.21  1073.2  2128.5  1102.9 2150.18
#Mann= 3 , 0 , 0
       0      .1       0   566.4    .045       0   578.6      .1       0
Bank Sta=566.4,578.6
XS Rating Curve= 0 ,0
Exp/Cntr=0.3,0.1

Type RM Length L Ch R = 1 ,24599.1 ,452.7,450.3,448
XS GIS Cut Line= 3
     1893632.814      215724.169     1893515.609      216252.207
     1893403.964      216816.105
#Sta/Elev= 30
       0 1892.95      59 1891.65    68.8 1892.26    98.3  1898.8   186.8 1901.32
   226.2    1904   344.2 1897.57     413 1886.98     472 1872.58   540.9 1861.77
   558.7 1856.02   570.6 1854.33   573.7 1854.89   620.2 1866.34     640 1869.19
   679.6  1884.8   699.5 1888.99   739.1 1907.02   788.7 1941.55   798.6 1943.02
   877.9 2001.47   887.8 2002.15   957.2 2051.27     977 2063.84   996.8  2070.5
  1026.5    2091  1046.4 2101.83  1066.2 2110.23    1086 2115.17  1115.7 2136.34
#Mann= 3 , 0 , 0
       0      .1       0   558.7    .045       0   573.7      .1       0
Bank Sta=558.7,573.7
XS Rating Curve= 0 ,0
Exp/Cntr=0.3,0.1