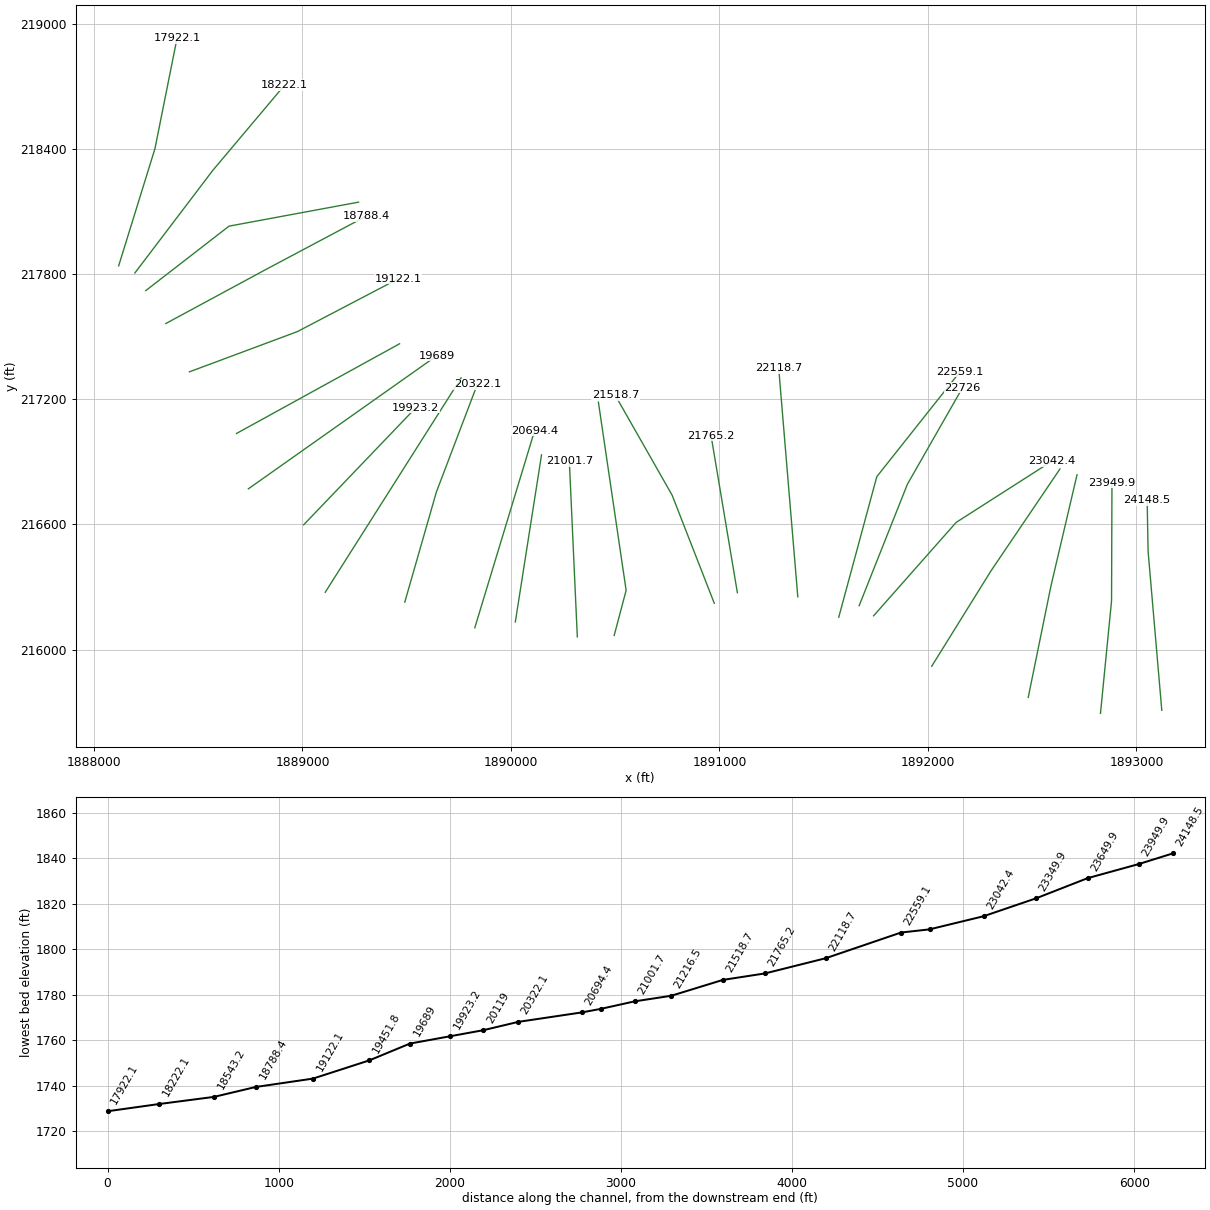
HEC-RAS study TmmyCrk.prj: TmmyCrk

--- TmmyCrk.g01 (geometry) --- (continued)

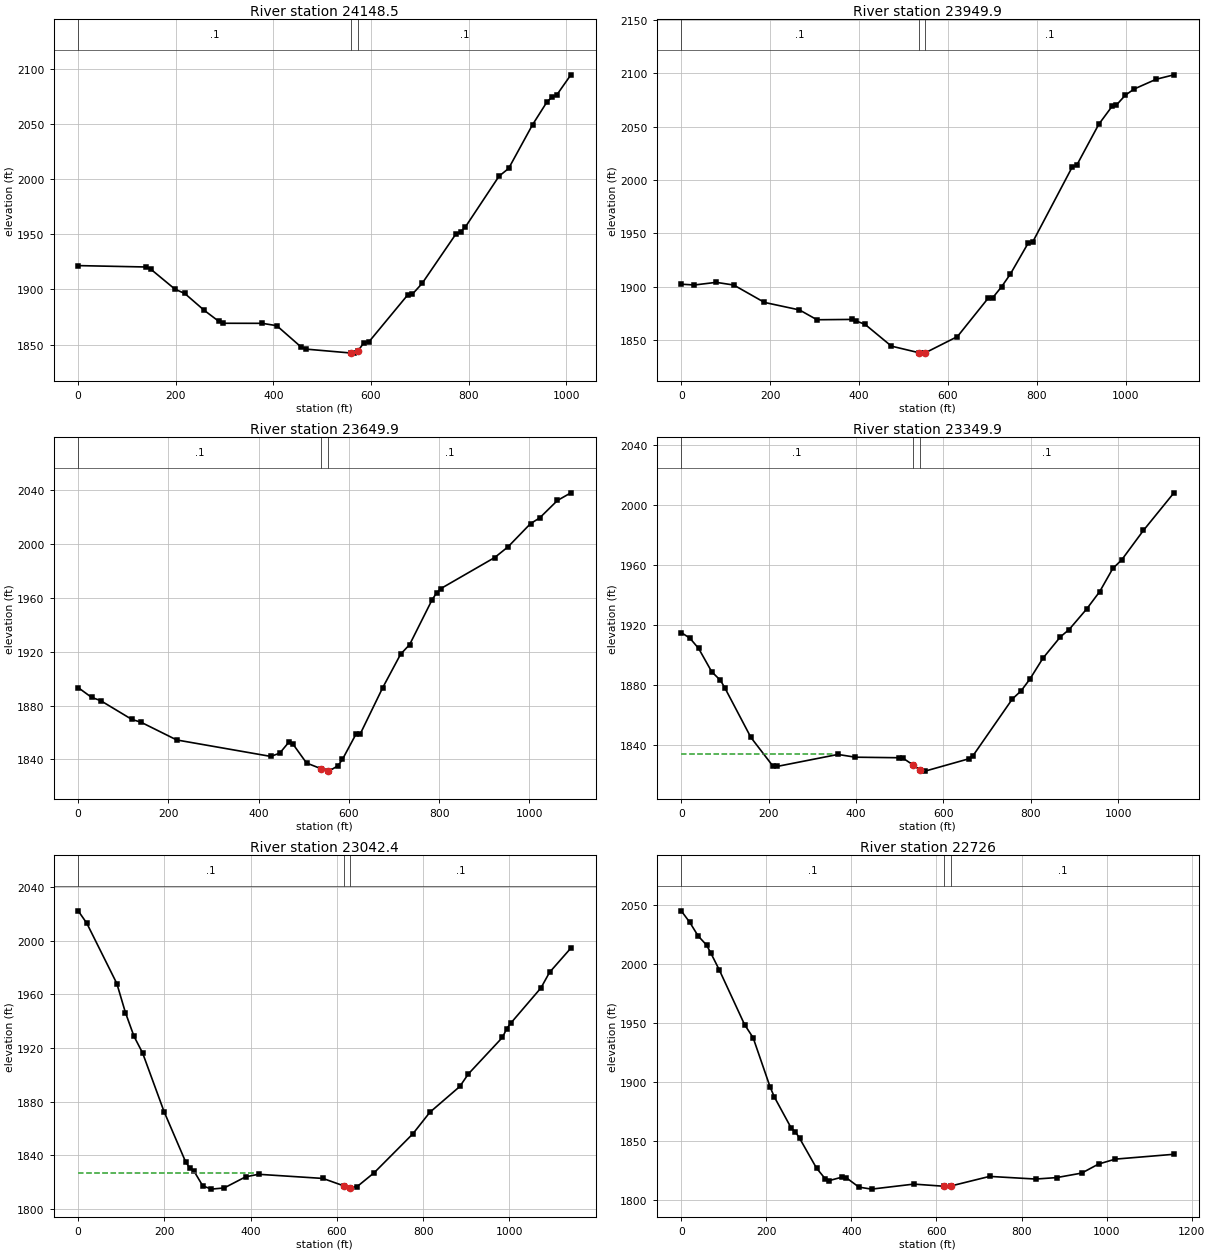
Type RM Length L Ch R = 1 ,24148.5 ,202.7,198.5,196.4
XS GIS Cut Line= 3
     1893121.452      215709.013     1893055.801      216470.578
     1893051.298      216715.977
#Sta/Elev= 30
       0 1921.52     139 1920.26   148.9 1918.25   198.5 1900.11   218.4 1896.28
   258.1 1881.07   287.9 1871.11   297.8 1869.27   377.2 1869.21     407 1867.08
   456.6 1847.86   466.6 1845.86   558.7 1842.32   565.8 1842.21   573.7  1844.3
   585.7 1851.74   595.6  1852.3     675 1894.76     685 1895.67   704.8 1905.32
   774.2  1950.2     784 1952.21   793.8 1956.69   862.6 2002.58   882.2 2009.56
   931.3 2049.25   960.7 2069.78   970.6 2074.01   980.4 2075.88  1009.8 2094.39
#Mann= 3 , 0 , 0
       0      .1       0   558.7    .045       0   573.7      .1       0
Bank Sta=558.7,573.7
XS Rating Curve= 0 ,0
Exp/Cntr=0.3,0.1

Type RM Length L Ch R = 1 ,23949.9 ,302.3,300,294.9
XS GIS Cut Line= 3
     1892827.385      215694.137     1892880.514      216233.568
      1892882.49      216800.421
#Sta/Elev= 30
       0  1902.2    29.6 1901.44    78.8 1903.91   118.3 1901.39   187.2  1885.1
   266.1 1878.05   305.5 1868.84   384.4 1869.15   394.2 1867.67   413.9 1864.46
     473 1844.11   534.5 1837.97     542 1837.54   549.5  1837.9   621.6 1853.06
   691.2 1889.27   701.2 1889.56     721 1899.78   740.9 1911.76   780.7  1940.6
   790.7 1941.49   880.2 2012.24   890.1  2013.7   939.8 2052.18   969.7    2069
   979.6 2070.26   999.5 2079.42  1019.4 2085.22  1069.1  2094.4  1108.9 2098.52
#Mann= 3 , 0 , 0
       0      .1       0   534.5    .045       0   549.5      .1       0
Bank Sta=534.5,549.5
XS Rating Curve= 0 ,0
Exp/Cntr=0.3,0.1

Type RM Length L Ch R = 1 ,23649.9 ,308.1,300,291.7
XS GIS Cut Line= 3
      1892480.89      215770.844     1892590.077      216305.764
     1892714.936      216837.587
#Sta/Elev= 30
       0 1893.33    29.8 1886.04    49.6 1883.69   119.1 1869.67     139 1867.67
   218.4 1854.46   426.8 1842.25   446.7 1844.63   466.5 1852.61   476.5 1851.21
   506.2 1837.35   538.4 1833.11   553.4 1831.49   555.9 1831.32   575.8 1835.31
   585.7 1839.98   615.5 1858.59   625.4 1859.03   675.1 1893.29   714.8 1918.14
   734.7 1925.22   784.3 1958.35   794.3 1963.56   804.2 1966.88   923.4 1989.89
   953.2 1997.91  1002.8 2015.08  1022.7 2019.18  1062.4 2032.23  1092.2  2037.9
#Mann= 3 , 0 , 0
       0      .1       0   538.4    .045       0   553.4      .1       0
Bank Sta=538.4,553.4
XS Rating Curve= 0 ,0
Exp/Cntr=0.3,0.1

Type RM Length L Ch R = 1 ,23349.9 ,317.1,307.4,298.6
XS GIS Cut Line= 3
     1892017.988      215920.012      1892302.19      216377.045
     1892632.894      216865.323
#Sta/Elev= 30
       0 1915.02    19.9 1911.25    39.9 1904.38    69.8 1888.85    89.7 1883.13
    99.7 1878.17   159.5 1844.99   209.3 1826.08   219.3 1825.62   358.8 1833.63
   398.7 1831.79   498.3 1831.43   508.3 1831.02   530.7 1826.63   545.7 1823.36
   558.2 1822.49   658.1  1830.7   668.1 1832.86   758.1 1870.69   778.1 1876.11
   798.1 1883.91   828.1 1897.92     868 1912.14     888 1917.05     928 1930.71
     958 1942.36     988 1957.82    1008 1963.43    1058 1983.19  1127.9 2008.31
#Mann= 3 , 0 , 0
       0      .1       0   530.7    .045       0   545.7      .1       0
#XS Ineff= 2 , 0
          346.31 1834.13
Permanent Ineff=
       F       F
Bank Sta=530.7,545.7
XS Rating Curve= 0 ,0
Exp/Cntr=0.3,0.1

Type RM Length L Ch R = 1 ,23042.4 ,302,316.3,327.5
XS GIS Cut Line= 3
     1891739.283      216161.816     1892135.066      216609.269
     1892594.271       216902.84
#Sta/Elev= 30
       0 2022.39    19.9 2013.16    89.6 1968.12   109.5 1946.47   129.4 1928.72
   149.3 1916.32   199.1  1872.5   248.9 1835.15   258.9 1830.21   268.8  1827.9
   288.7 1817.11   308.6  1814.6   338.5 1815.48   388.3 1823.79   418.2 1825.68
   567.5 1822.58   616.2    1817   631.2  1815.7   646.9 1816.51   686.6 1826.94
   775.8 1855.82   815.4 1871.97   884.8 1891.23   904.6 1900.58   983.8 1927.92
   993.8  1934.5  1003.7 1938.77    1073 1964.84  1092.8 1976.41  1142.4 1994.58
#Mann= 3 , 0 , 0
       0      .1       0   616.2    .045       0   631.2      .1       0
#XS Ineff= 2 , 0
          407.76 1826.84
Permanent Ineff=
       F       F
Bank Sta=616.2,631.2
XS Rating Curve= 0 ,0
Exp/Cntr=0.3,0.1

Type RM Length L Ch R = 1 ,22726   ,169.6,166.9,167.2
XS GIS Cut Line= 3
      1891669.94      216210.364     1891901.357      216792.365
     1892165.234      217254.109
#Sta/Elev= 30
       0 2045.46    19.9 2035.79    39.8 2024.06    59.6 2016.34    69.6 2009.54
    89.5 1995.21   149.1 1948.59     169 1937.58   208.8  1895.8   218.7  1887.3
   258.5  1860.8   268.4 1857.54   278.4 1851.96   318.1 1826.65     338 1817.83
     348  1816.1   377.8    1819   387.7  1818.6   417.6 1810.53   447.4 1808.82
   546.8 1813.09   618.8 1811.24   633.8 1811.49   724.8 1819.64   833.1 1817.39
   882.4 1818.62   941.5 1822.47   980.9 1830.14  1020.3 1834.33  1158.2 1838.45
#Mann= 3 , 0 , 0
       0      .1       0   618.8    .045       0   633.8      .1       0
Bank Sta=618.8,633.8
XS Rating Curve= 0 ,0
Exp/Cntr=0.3,0.1

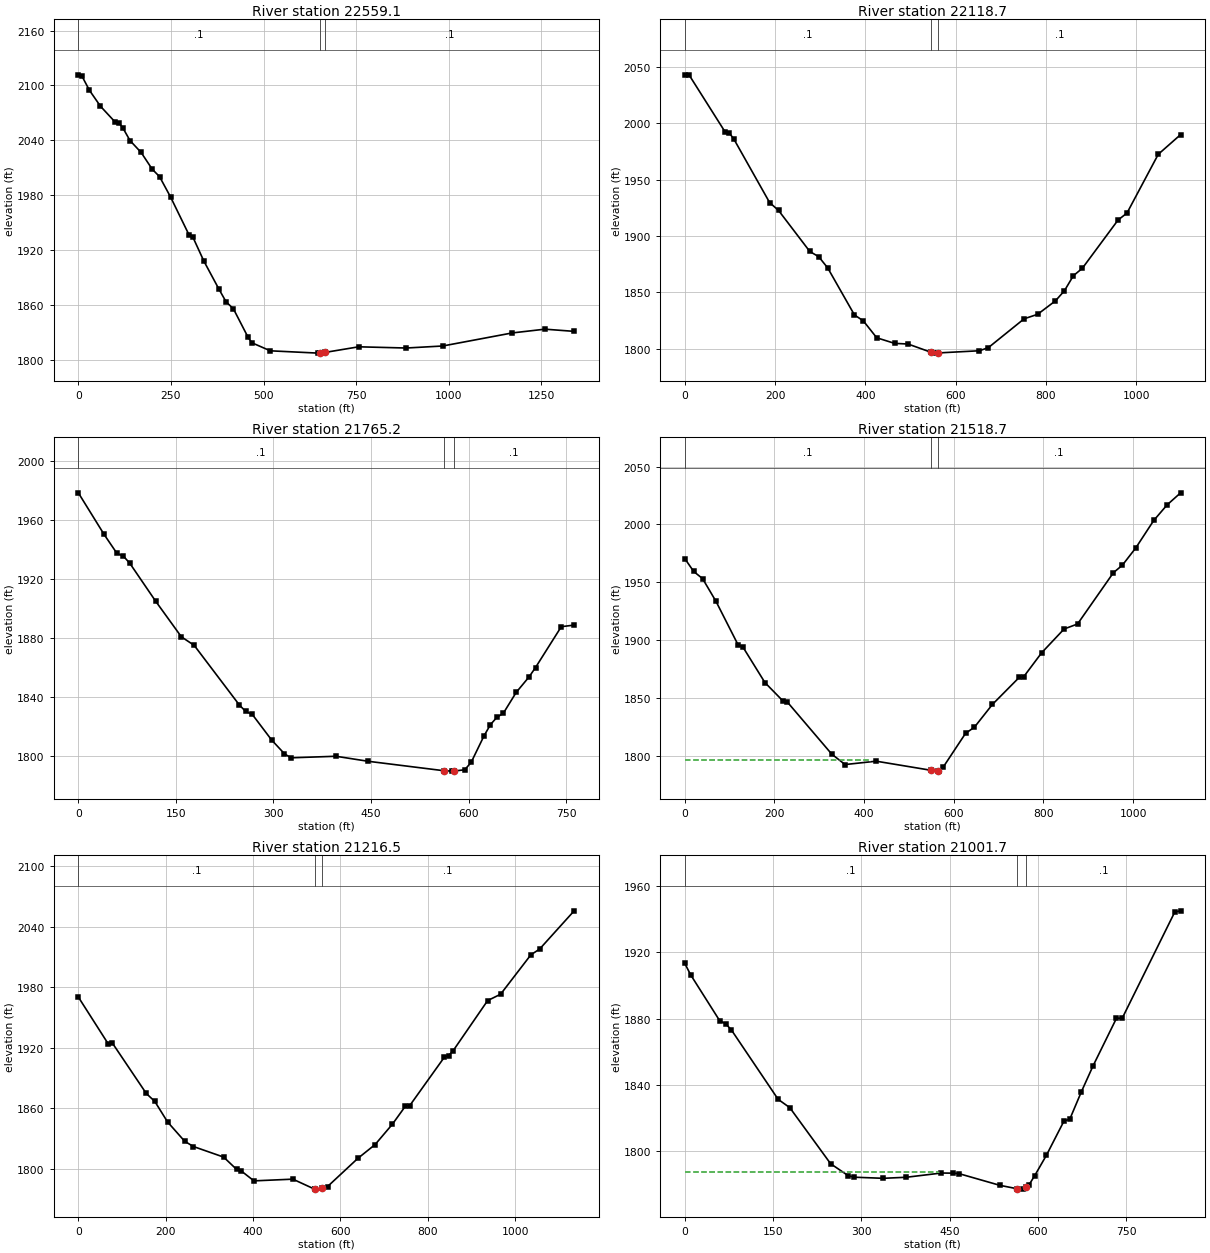
Type RM Length L Ch R = 1 ,22559.1 ,427.4,440.4,453.6
XS GIS Cut Line= 3
     1891572.097      216154.968     1891754.511      216828.545
     1892153.003      217330.599
#Sta/Elev= 30
       0 2111.57      10 2109.99    29.9 2094.71    59.8 2077.23    99.7 2059.82
   109.7 2058.82   119.6    2054   139.6 2039.69   169.5 2026.76   199.4 2008.48
   219.3  2000.3   249.2 1977.91   299.1 1936.46     309 1934.45     339 1907.97
   378.8 1877.98   398.8 1863.58   418.7 1855.86   458.6 1824.51   468.6 1818.73
   518.4 1809.95     648 1807.42   651.2 1807.48   666.2  1808.2     757 1814.33
   885.2    1813   983.8 1815.21  1171.2 1829.47  1259.9  1833.6  1338.8  1831.2
#Mann= 3 , 0 , 0
       0      .1       0   651.2    .045       0   666.2      .1       0
Bank Sta=651.2,666.2
XS Rating Curve= 0 ,0
Exp/Cntr=0.3,0.1

Type RM Length L Ch R = 1 ,22118.7 ,351.5,353.5,355.5
XS GIS Cut Line= 3
     1891375.649      216252.778     1891329.402      216804.651
     1891284.194      217347.393
#Sta/Elev= 30
       0 2043.04     9.9 2042.67      89 1992.56    98.9 1991.28   108.8 1985.96
   187.9 1929.71   207.7  1922.7   276.9 1886.32   296.7 1881.65   316.5 1871.78
   375.8 1830.02   395.6 1824.69   425.2 1809.73   464.8 1804.78   494.5  1804.2
   546.3 1796.77   553.8 1796.12   561.3 1796.29   652.8 1798.23   672.6 1801.03
   751.8  1826.6   781.6 1830.55   821.2 1842.55     841 1851.47   860.8  1864.8
   880.6 1871.36   959.8 1914.22   979.6 1920.42  1048.9 1972.55  1098.4    1990
#Mann= 3 , 0 , 0
       0      .1       0   546.3    .045       0   561.3      .1       0
Bank Sta=546.3,561.3
XS Rating Curve= 0 ,0
Exp/Cntr=0.3,0.1

Type RM Length L Ch R = 1 ,21765.2 ,242.1,246.5,254.2
XS GIS Cut Line= 2
     1891085.856      216272.458     1890959.779      217024.414
#Sta/Elev= 30
       0 1978.28    39.6 1950.06    59.4 1937.18    69.3 1935.35    79.2 1930.44
   118.8 1904.81   158.4  1880.6   178.2 1874.77   247.6 1834.33   257.4 1829.93
   267.4 1827.98   297.1 1810.65   316.9 1801.24   326.8 1798.49   396.1 1799.55
   445.6 1796.14     562 1789.74   574.3 1789.46     577 1789.49   594.1 1790.37
     604 1795.39   623.8 1813.39   633.7 1821.02   643.6 1825.98   653.5 1828.73
   673.3 1842.89   693.1 1853.42     703 1859.76   742.6 1887.46   762.4 1888.54
#Mann= 3 , 0 , 0
       0      .1       0     562    .045       0     577      .1       0
Bank Sta=562,577
XS Rating Curve= 0 ,0
Exp/Cntr=0.3,0.1

Type RM Length L Ch R = 1 ,21518.7 ,307.1,302.2,293.8
XS GIS Cut Line= 3
     1890975.092      216221.745     1890772.833      216739.943
     1890500.577      217217.797
#Sta/Elev= 30
       0 1970.45    19.9 1959.33    39.7 1953.12    69.5 1933.55   119.2 1895.61
   129.1 1894.31   178.8 1863.21   218.5  1847.5   228.5 1846.51   327.8 1801.34
   357.6  1792.3   427.1 1795.21   548.8 1787.37   563.8 1786.64   566.3 1786.61
   576.3 1789.95   626.3 1819.25   646.3 1824.68   686.3 1844.31   746.3 1867.77
   756.3 1868.37   796.3 1889.06   846.3  1909.6   876.2 1913.88   956.2 1958.27
   976.2 1964.75  1006.2 1979.74  1046.2 2003.46  1076.2 2017.01  1106.2 2027.37
#Mann= 3 , 0 , 0
       0      .1       0   548.8    .045       0   563.8      .1       0
#XS Ineff= 2 , 0
          414.27 1796.47
Permanent Ineff=
       F       F
Bank Sta=548.8,563.8
XS Rating Curve= 0 ,0
Exp/Cntr=0.3,0.1

Type RM Length L Ch R = 1 ,21216.5 ,217.1,214.8,212.4
XS GIS Cut Line= 3
     1890494.919      216067.472     1890552.282      216283.714
      1890419.28      217185.466
#Sta/Elev= 30
       0 1970.15    68.1 1923.93    77.8 1924.59   155.6  1874.5   175.1  1866.6
   204.3 1846.26   243.5 1827.09   263.4  1821.9   332.7  1811.4   362.4 1799.19
   372.3 1797.89   402.1 1787.82   491.2 1789.52   540.8 1779.63   542.4 1779.67
   557.4 1780.52   570.5 1782.15   639.8 1810.08   679.5 1823.84   719.1 1844.04
   748.8 1861.91   758.7 1862.44     838 1910.49   847.9 1912.15   857.8 1916.71
   937.1 1966.63   966.8 1972.95  1036.2 2012.08    1056 2017.68  1135.2 2055.66
#Mann= 3 , 0 , 0
       0      .1       0   542.4    .045       0   557.4      .1       0
Bank Sta=542.4,557.4
XS Rating Curve= 0 ,0
Exp/Cntr=0.3,0.1

Type RM Length L Ch R = 1 ,21001.7 ,200.1,195.4,190.7
XS GIS Cut Line= 2
      1890318.14      216060.829     1890279.867       216902.84
#Sta/Elev= 30
       0 1913.21     9.9 1906.37    59.5 1878.58    69.4  1876.9    79.3 1873.07
   158.7 1831.28   178.5 1826.27   247.9 1792.47   277.6 1785.32   287.6 1784.36
   337.2 1783.68   376.8 1784.32   436.3 1786.87   456.2 1786.78   466.1  1786.5
   535.5 1779.46   564.9 1777.39   575.1 1777.16   579.9 1778.38   585.1  1779.7
     595 1785.37   614.8 1797.61   644.6  1818.2   654.5 1819.35   674.3 1835.96
   694.1 1851.51   733.8 1880.13   743.7 1880.24     833 1944.25   842.9 1944.92
#Mann= 3 , 0 , 0
       0      .1       0   564.9    .045       0   579.9      .1       0
#XS Ineff= 2 , 0
          432.12 1787.61
Permanent Ineff=
       F       F
Bank Sta=564.9,579.9
XS Rating Curve= 0 ,0
Exp/Cntr=0.3,0.1

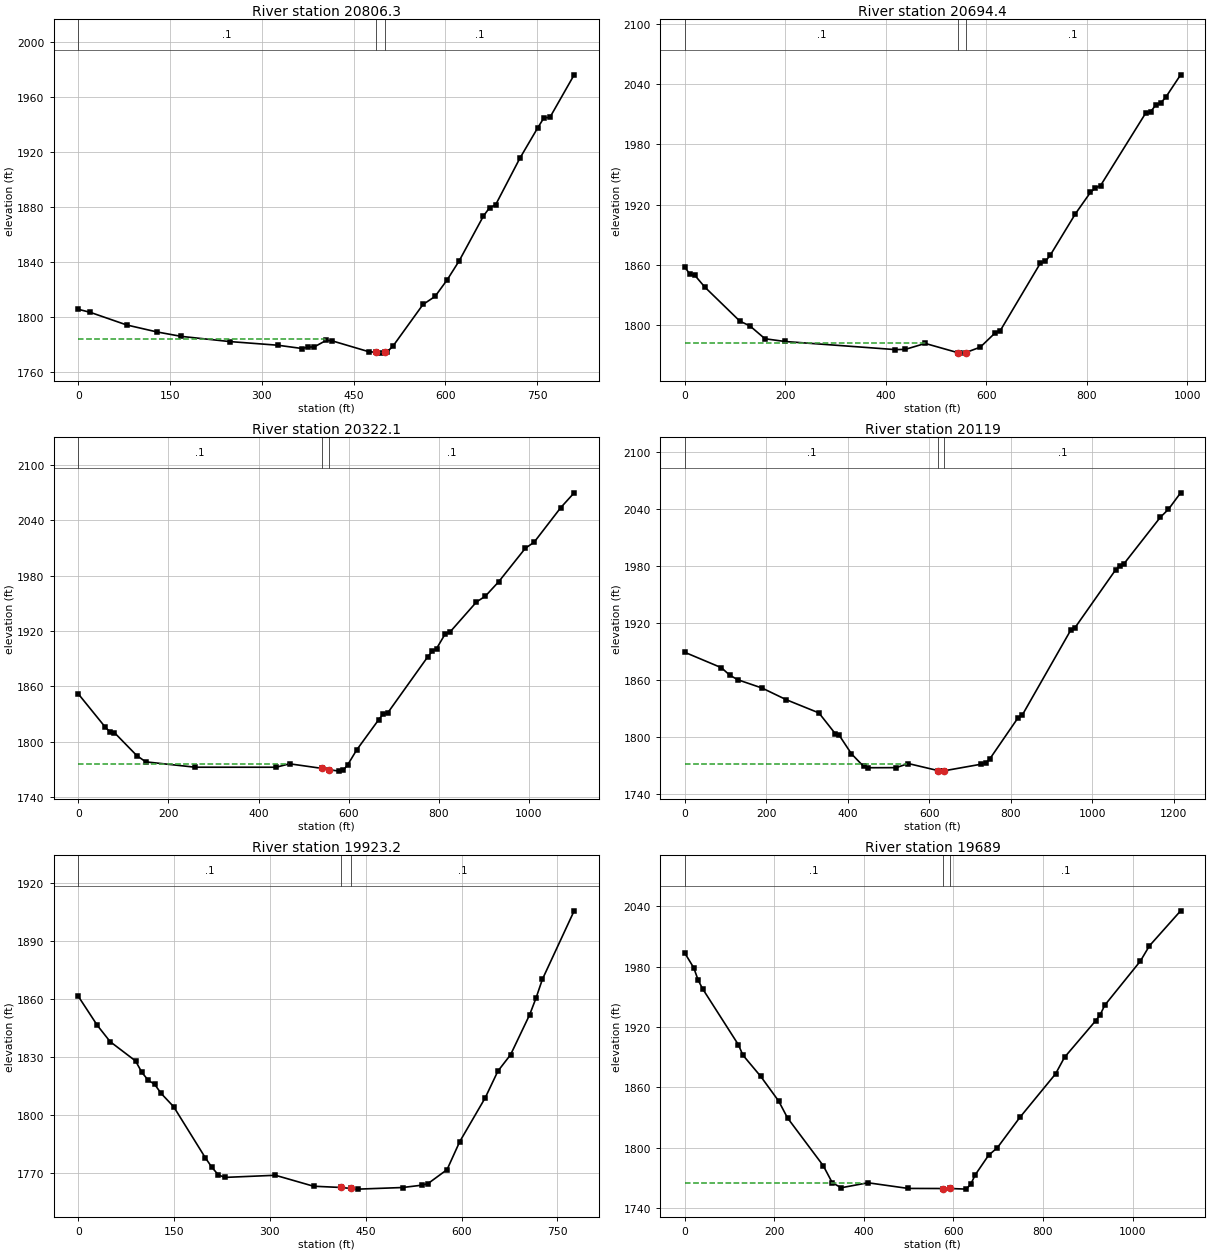
Type RM Length L Ch R = 1 ,20806.3 ,114.9,111.8,108.8
XS GIS Cut Line= 2
     1890020.739      216132.051     1890146.477      216933.047
#Sta/Elev= 30
       0 1805.75    19.8  1803.5    79.1 1794.36   128.5  1789.3   168.1 1786.08
   247.2 1782.31   326.3 1779.63   365.8 1777.25   375.7  1778.3   385.6 1778.38
   405.4 1783.18   415.3 1782.78   474.6 1774.98   486.5 1774.44   494.4 1773.89
   501.5 1774.37   504.3 1774.56   514.2 1778.78   563.6 1809.25   583.4 1815.12
   603.2 1827.21   622.9 1841.06   662.5  1873.6   672.4 1879.56   682.3 1881.66
   721.8 1915.39   751.5  1937.9   761.4 1944.97   771.2 1945.29   810.8 1976.22
#Mann= 3 , 0 , 0
       0      .1       0   486.5    .045       0   501.5      .1       0
#XS Ineff= 2 , 0
          402.64 1784.51
Permanent Ineff=
       F       F
Bank Sta=486.5,501.5
XS Rating Curve= 0 ,0
Exp/Cntr=0.3,0.1

Type RM Length L Ch R = 1 ,20694.4 ,372,372.4,370.7
XS GIS Cut Line= 2
     1889826.478       216104.51     1890113.266      217049.179
#Sta/Elev= 30
       0 1858.14      10 1850.79    19.9 1849.81    39.9 1838.02   109.7 1804.12
   129.6 1799.44   159.6 1786.63   199.4  1783.9   418.8 1775.84   438.8 1776.03
   478.7 1781.97   544.5 1772.65   548.5 1772.32   559.5 1772.91   588.4 1778.29
   618.3 1792.64   628.2 1794.79     708 1861.91     718 1863.66     728 1870.09
   777.8 1911.06   807.7 1932.34   817.7 1936.74   827.7 1938.99   917.4 2011.02
   927.4  2012.5   937.4 2019.02   947.4 2021.26   957.3 2026.78   987.2  2049.3
#Mann= 3 , 0 , 0
       0      .1       0   544.5    .045       0   559.5      .1       0
#XS Ineff= 2 , 0
          478.06 1782.04
Permanent Ineff=
       F       F
Bank Sta=544.5,559.5
XS Rating Curve= 0 ,0
Exp/Cntr=0.3,0.1

Type RM Length L Ch R = 1 ,20322.1 ,210,203.1,198.3
XS GIS Cut Line= 3
     1889490.637      216227.418     1889642.119      216754.935
     1889838.457      217270.747
#Sta/Elev= 30
       0 1851.77    59.9 1815.72    69.8 1810.92    79.8 1809.99   129.7 1785.02
   149.7 1778.19   259.4 1772.39   439.1 1772.37     469 1776.09   541.3 1771.08
   556.3 1769.77   578.4 1768.15   588.3 1769.15   598.1 1775.04   617.8    1791
   667.1 1824.04     677 1830.07   686.8 1831.17   775.5 1891.79   785.4 1897.84
   795.2 1900.87   814.9 1917.09   824.8 1918.64   883.9 1951.36   903.6 1957.65
   933.2 1973.28   992.3  2009.5    1012 2016.16  1071.2 2053.68  1100.8 2069.61
#Mann= 3 , 0 , 0
       0      .1       0   541.3    .045       0   556.3      .1       0
#XS Ineff= 2 , 0
          467.15 1776.01
Permanent Ineff=
       F       F
Bank Sta=541.3,556.3
XS Rating Curve= 0 ,0
Exp/Cntr=0.3,0.1

Type RM Length L Ch R = 1 ,20119   ,199.3,195.8,192.3
XS GIS Cut Line= 2
     1889109.157      216274.709     1889760.851      217302.062
#Sta/Elev= 30
       0 1889.54    89.8 1873.35   109.7  1865.7   129.6 1860.73   189.5 1851.96
   249.3 1839.61   329.1 1825.76     369 1804.04     379 1802.16   408.9 1782.74
   438.8 1769.41   448.8 1768.08   518.6 1768.17   548.5 1772.47     622 1765.02
   628.2 1764.51     637 1764.91     728 1771.86     738 1773.29   747.9 1777.06
   817.7 1820.67   827.7 1823.23   947.4 1913.19   957.3 1915.39  1057.1 1976.35
    1067 1980.87    1077  1982.4  1166.8 2031.64  1186.7 2040.04  1216.6 2057.38
#Mann= 3 , 0 , 0
       0      .1       0     622    .045       0     637      .1       0
#XS Ineff= 2 , 0
          545.85 1772.47
Permanent Ineff=
       F       F
Bank Sta=622,637
XS Rating Curve= 0 ,0
Exp/Cntr=0.3,0.1

Type RM Length L Ch R = 1 ,19923.2 ,239.2,234.2,229.1
XS GIS Cut Line= 2
     1889005.522      216597.746     1889542.624      217158.134
#Sta/Elev= 30
       0 1861.26    29.8 1846.26    49.8  1837.9    89.6 1827.94    99.5 1822.01
   109.5 1817.97   119.4 1815.93   129.4 1811.28   149.3  1804.3     199  1777.9
     209 1773.11   218.9 1769.25   228.9 1767.86   308.5 1768.97   368.2 1763.32
   411.2 1762.67   426.2 1762.17   437.9 1761.82   507.5 1762.65   537.4 1763.84
   547.3 1764.66   577.2 1771.87   597.1 1786.34   636.9 1808.89   656.8  1822.7
   676.7 1831.17   706.6 1851.84   716.5 1860.39   726.5 1870.09   776.2 1905.39
#Mann= 3 , 0 , 0
       0      .1       0   411.2    .045       0   426.2      .1       0
Bank Sta=411.2,426.2
XS Rating Curve= 0 ,0
Exp/Cntr=0.3,0.1

Type RM Length L Ch R = 1 ,19689   ,240.3,237.2,234
XS GIS Cut Line= 2
     1888740.365      216770.331     1889644.992       217408.76
#Sta/Elev= 30
       0 1993.54      20 1978.91    29.9 1966.52    39.9 1957.93   119.7  1902.3
   129.7 1892.03   169.6 1870.79   209.5 1846.35   229.4 1829.47   309.2 1781.91
   329.2 1765.07   349.1 1759.96     409 1764.94   498.8  1759.3   577.4 1759.22
   592.4 1759.25   628.4 1758.61   638.4 1763.34   648.4 1772.73   678.3 1792.26
   698.2 1799.96   748.1 1829.94   827.9  1873.3   847.9  1889.8   917.7 1926.32
   927.7 1932.21   937.6 1941.55  1017.4 1985.63  1037.4 2000.69  1107.2 2035.61
#Mann= 3 , 0 , 0
       0      .1       0   577.4    .045       0   592.4      .1       0
#XS Ineff= 2 , 0
          396.93 1765.09
Permanent Ineff=
       F       F
Bank Sta=577.4,592.4
XS Rating Curve= 0 ,0
Exp/Cntr=0.3,0.1

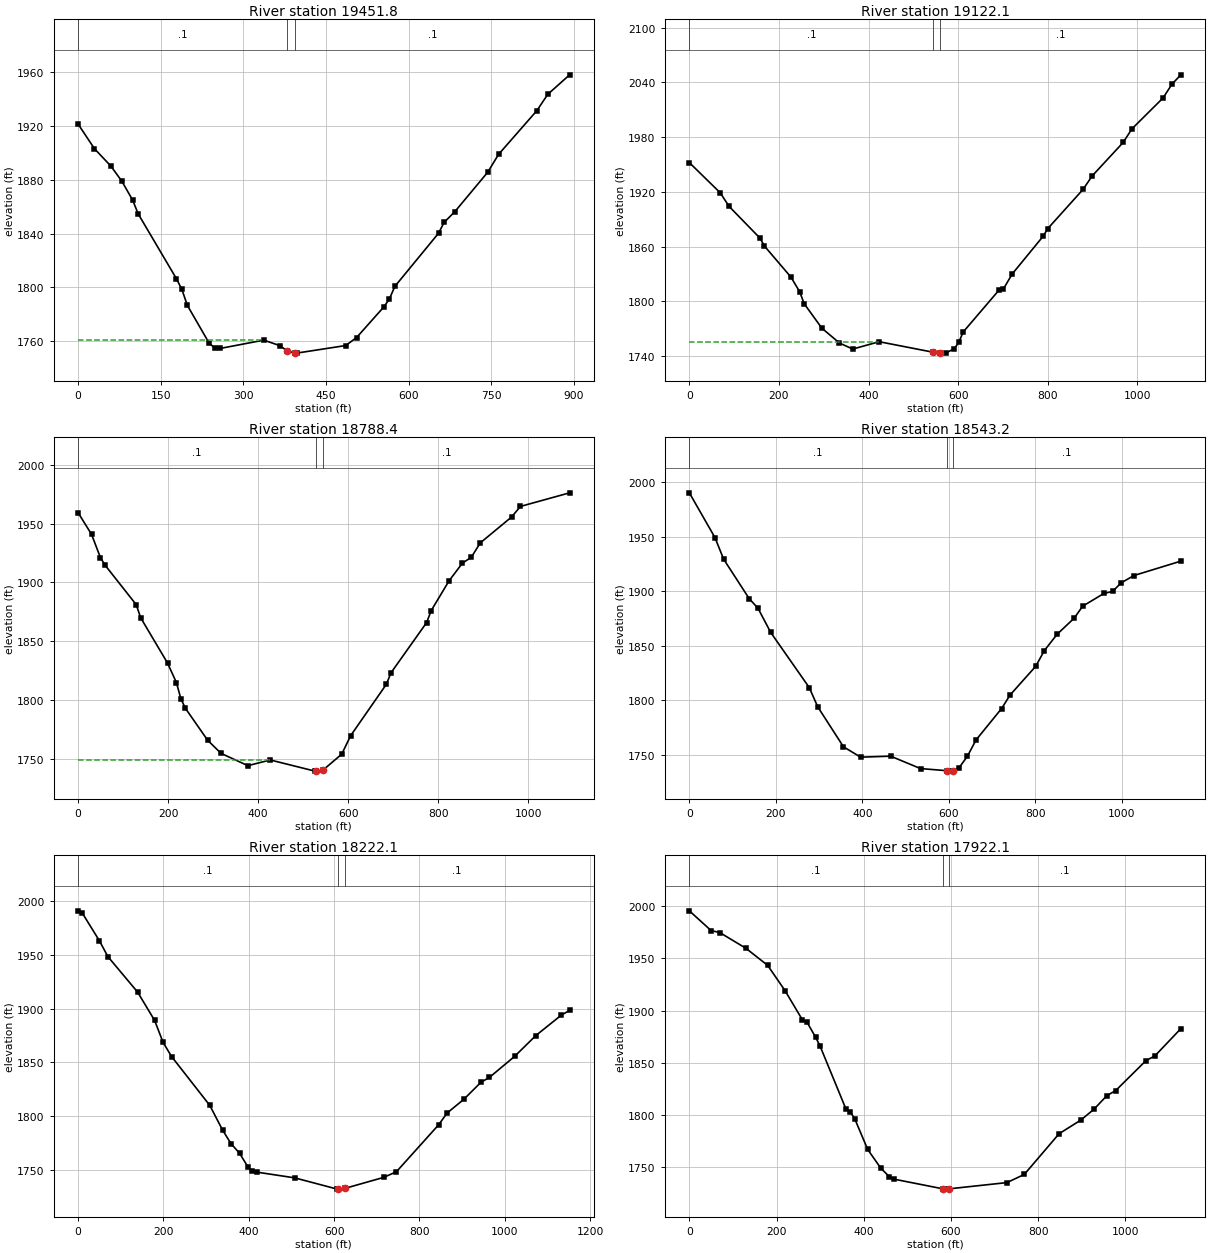
Type RM Length L Ch R = 1 ,19451.8 ,333,329.7,329.2
XS GIS Cut Line= 2
     1888683.648      217035.671     1889465.577      217465.541
#Sta/Elev= 30
       0  1921.3    29.7 1903.03    59.5 1890.12    79.3 1878.96    99.1  1864.8
   109.1 1854.61   178.5 1806.49   188.4  1798.5   198.3  1786.7     238 1758.55
   247.9 1755.11   257.8 1754.71   337.1 1760.88   366.8 1756.72   379.5 1752.83
   394.5 1751.25   396.6 1751.23   485.8 1756.86   505.6 1762.83   555.2 1785.63
   565.1 1791.47     575 1800.78   654.4 1840.31   664.3 1848.26   684.1 1856.38
   743.6 1885.56   763.4 1898.88   832.8  1931.3   852.6 1943.42   892.3 1957.91
#Mann= 3 , 0 , 0
       0      .1       0   379.5    .045       0   394.5      .1       0
#XS Ineff= 2 , 0
          335.62 1760.93
Permanent Ineff=
       F       F
Bank Sta=379.5,394.5
XS Rating Curve= 0 ,0
Exp/Cntr=0.3,0.1

Type RM Length L Ch R = 1 ,19122.1 ,330.6,333.7,333.9
XS GIS Cut Line= 3
     1888457.865      217331.081     1888975.231      217523.768
     1889458.296      217776.387
#Sta/Elev= 30
       0 1952.08      69 1918.96    88.7 1904.09   157.7 1869.28   167.6 1860.64
   226.8 1826.57   246.5 1810.35   256.3 1797.44   295.8 1770.57   335.2 1754.26
   364.8 1747.69   423.9 1755.72   544.6 1744.17   559.6 1743.52   571.9 1743.21
   591.7 1748.09   601.6 1755.31   611.6 1766.53   690.8 1812.01   700.8 1813.25
   720.6 1829.89     790 1871.47   799.9 1879.59   879.2 1922.86     899 1937.34
   968.4 1974.15   988.2 1989.16  1057.6    2023  1077.4 2038.07  1097.2  2048.3
#Mann= 3 , 0 , 0
       0      .1       0   544.6    .045       0   559.6      .1       0
#XS Ineff= 2 , 0
          423.35  1755.7
Permanent Ineff=
       F       F
Bank Sta=544.6,559.6
XS Rating Curve= 0 ,0
Exp/Cntr=0.3,0.1

Type RM Length L Ch R = 1 ,18788.4 ,252.2,245.2,238.2
XS GIS Cut Line= 3
     1888344.453      217562.521     1888824.947      217821.864
     1889307.213      218077.857
#Sta/Elev= 30
       0 1959.17    29.8 1940.83    49.6 1920.98    59.6 1914.72   129.1 1881.01
     139 1869.88   198.6 1831.45   218.4 1814.79   228.3 1801.03   238.3 1792.98
   287.9 1765.72   317.7  1754.6   377.2 1744.19   426.9 1749.02   526.2 1739.54
   529.3 1739.61   544.3  1740.5   585.7 1753.98   605.6 1769.73     685 1813.44
   694.9 1822.98   774.3  1865.8   784.3 1875.88     824 1901.22   853.8 1916.32
   873.6  1921.3   893.5 1933.54     963 1955.52   982.8 1964.53    1092 1976.08
#Mann= 3 , 0 , 0
       0      .1       0   529.3    .045       0   544.3      .1       0
#XS Ineff= 2 , 0
          426.46 1749.01
Permanent Ineff=
       F       F
Bank Sta=529.3,544.3
XS Rating Curve= 0 ,0
Exp/Cntr=0.3,0.1

Type RM Length L Ch R = 1 ,18543.2 ,304.4,321.1,336.7
XS GIS Cut Line= 3
     1888248.196      217720.166     1888647.627      218029.304
     1889268.721       218144.31
#Sta/Elev= 30
       0 1990.17    59.4 1949.06    79.2 1929.47   138.6 1893.11   158.5 1884.59
   188.2 1862.26   277.3 1811.75   297.1 1793.98   356.5 1757.46   396.2 1747.95
   465.5 1748.88   534.7 1737.51   594.9 1735.59   603.8 1735.17   609.9 1735.26
   623.5 1738.08   643.3 1748.92     663 1763.71   722.2 1792.54     742 1805.02
   801.2 1831.28   820.9 1845.54   850.5 1860.54     890 1875.32   909.7  1886.3
   959.1 1898.06   978.8 1899.78   998.6 1907.68  1028.2 1914.39  1136.7 1927.58
#Mann= 3 , 0 , 0
       0      .1       0   594.9    .045       0   609.9      .1       0
Bank Sta=594.9,609.9
XS Rating Curve= 0 ,0
Exp/Cntr=0.3,0.1

Type RM Length L Ch R = 1 ,18222.1 ,292.1,300,311.4
XS GIS Cut Line= 3
     1888196.174      217804.896     1888569.713      218296.521
     1888914.339      218705.457
#Sta/Elev= 30
       0 1990.84      10 1988.64    49.8 1963.06    69.7  1948.3   139.4 1915.29
   179.3 1888.96   199.2 1868.46   219.1 1855.34   308.7 1809.88   338.6 1786.98
   358.5 1774.28   378.4  1765.4   398.4  1752.5   408.3 1749.05   418.3 1747.88
   507.9  1742.5   607.5 1732.03   609.9 1732.04   624.9 1732.67   716.5 1742.97
   746.2 1748.21   845.2 1791.88     865 1802.79   904.6 1815.71   944.2 1831.34
   964.1  1835.9  1023.5 1855.56    1073 1874.86  1132.4 1893.73  1152.2 1898.29
#Mann= 3 , 0 , 0
       0      .1       0   609.9    .045       0   624.9      .1       0
Bank Sta=609.9,624.9
XS Rating Curve= 0 ,0
Exp/Cntr=0.3,0.1

Type RM Length L Ch R = 1 ,17922.1 ,379.5,383.3,384.7
XS GIS Cut Line= 3
     1888118.279      217839.026     1888292.501      218401.396
     1888398.122      218929.393
#Sta/Elev= 30
       0 1995.62    49.9  1976.7    69.8 1974.79   129.7 1959.73   179.6 1943.36
   219.5 1919.11   259.4 1891.04   269.4 1889.21   289.4 1874.61   299.4  1866.4
   359.2 1805.61   369.2 1802.74   379.2 1796.43   409.1 1766.87   439.1 1748.95
     459 1740.66     469 1738.45   581.2  1729.2   588.7 1728.87   596.2 1729.18
   728.3 1735.13   768.2 1742.96     848 1781.97   897.8 1795.05   927.8 1805.38
   957.7 1818.53   977.6 1823.26  1047.4 1852.12  1067.4 1856.43  1127.2 1882.68
#Mann= 3 , 0 , 0
       0      .1       0   581.2    .045       0   596.2      .1       0
Bank Sta=581.2,596.2
XS Rating Curve= 0 ,0
Exp/Cntr=0.3,0.1