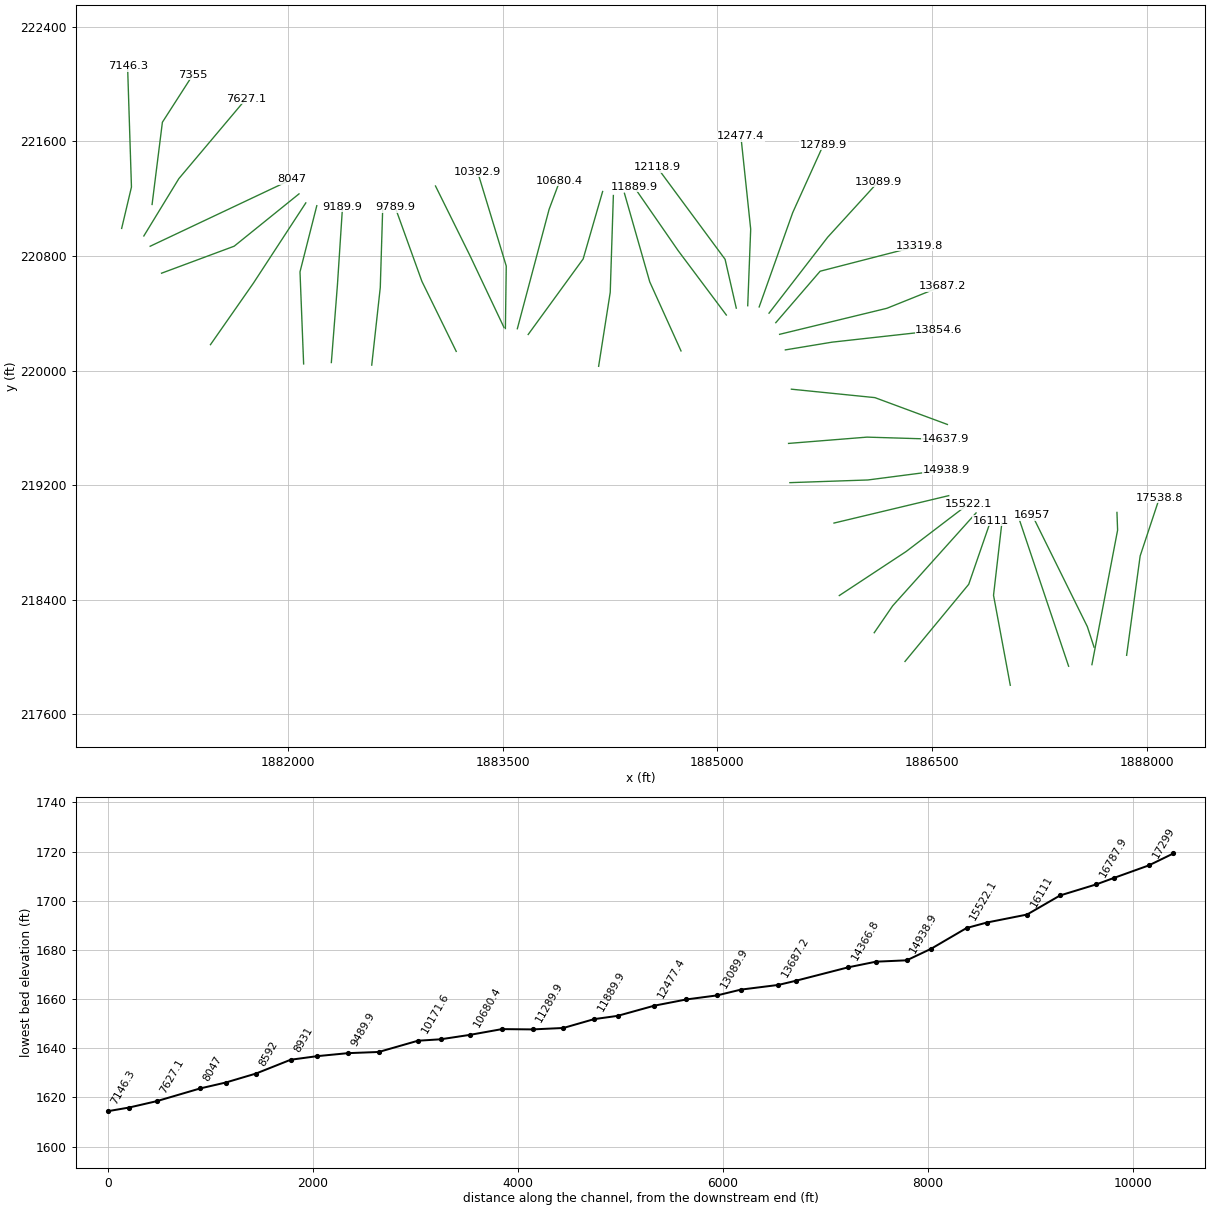
HEC-RAS study TmmyCrk.prj: TmmyCrk

--- TmmyCrk.g01 (geometry) --- (continued)

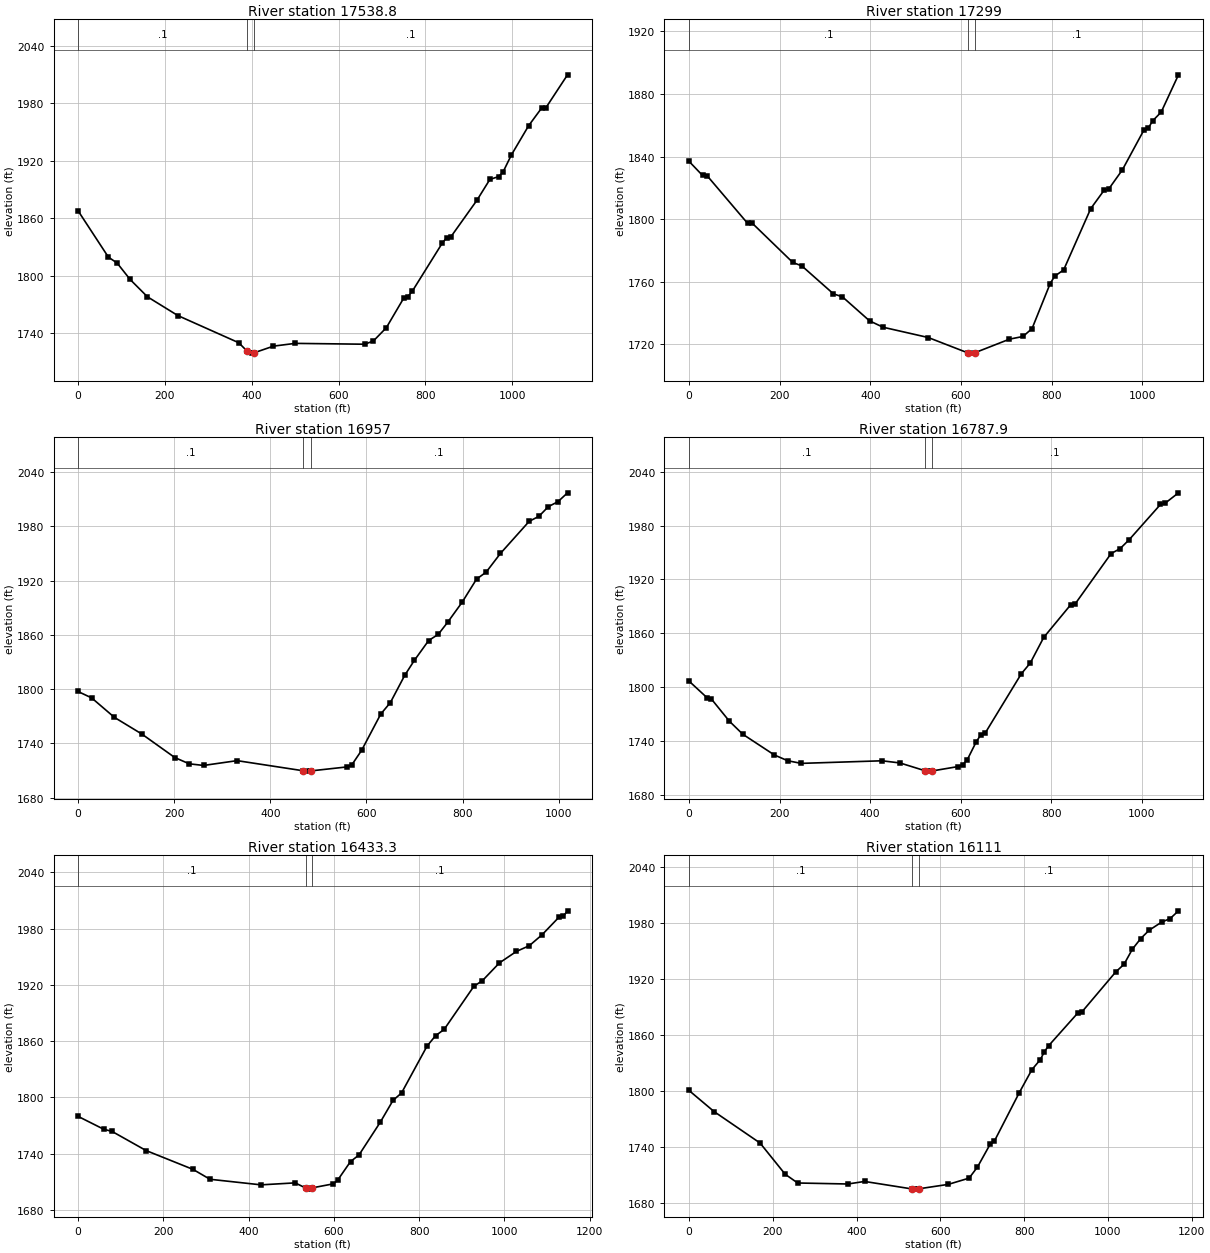
Type RM Length L Ch R = 1 ,17538.8 ,240.2,239.7,239.3
XS GIS Cut Line= 3
     1887859.653      218012.479     1887954.206      218706.184
     1888088.794      219111.654
#Sta/Elev= 30
       0 1867.97      70 1819.46      90 1813.35     120 1796.16     160 1778.02
     230 1758.45   370.1  1730.1   390.2 1720.97   400.1 1719.24   405.2 1719.54
   450.1 1726.54   500.1 1729.42   660.1 1728.54   680.1 1731.86     710 1745.76
   749.8 1776.46   759.7 1778.28   769.7  1783.8   839.2 1834.36   849.2 1839.94
   859.1 1840.97   918.7 1878.88   948.5 1900.64   968.4 1903.53   978.3 1907.93
   998.2 1926.33  1037.9 1956.82  1067.7 1975.18  1077.7 1975.61  1127.3 2009.86
#Mann= 3 , 0 , 0
       0      .1       0   390.2    .045       0   405.2      .1       0
Bank Sta=390.2,405.2
XS Rating Curve= 0 ,0
Exp/Cntr=0.3,0.1

Type RM Length L Ch R = 1 ,17299   ,328,342,355.9
XS GIS Cut Line= 3
     1887617.178      217947.137      1887796.61      218886.293
     1887792.108      219010.118
#Sta/Elev= 30
       0 1836.99    29.9 1827.94    39.8 1827.83   129.5 1797.27   139.4 1797.46
   229.1  1772.3     249 1770.13   318.7 1752.26   338.6 1750.35   398.4 1735.01
   428.3 1730.92   527.9 1724.35     616 1714.45   617.5 1714.37     631 1714.64
   707.2  1723.3     737 1725.01     757 1730.08   796.8 1758.72   806.8 1763.53
   826.7 1767.55   886.4  1806.7   916.3 1818.62   926.3 1819.32   956.1 1831.42
  1003.8 1856.96  1013.3 1858.05  1022.9 1862.77  1041.9 1868.42    1080 1892.23
#Mann= 3 , 0 , 0
       0      .1       0     616    .045       0     631      .1       0
Bank Sta=616,631
XS Rating Curve= 0 ,0
Exp/Cntr=0.3,0.1

Type RM Length L Ch R = 1 ,16957   ,172.2,169.1,166.1
XS GIS Cut Line= 3
     1887632.261      218069.047     1887584.982      218213.135
     1887200.701        218990.2
#Sta/Elev= 30
       0 1797.35    28.4 1790.24    75.8 1768.68   132.7  1750.3   201.5 1724.22
   231.4 1717.34   261.2 1715.52     331 1720.84   469.1 1709.59   480.5 1709.24
   484.1 1709.48   560.2 1713.93   570.2 1716.56   590.1 1732.25   629.9 1772.37
   649.9 1785.07   679.8 1815.22   699.7 1831.69   729.6 1853.76   749.5 1860.54
   769.4 1874.14   799.3 1896.15   829.2 1921.66   849.2  1929.4     879 1950.13
   938.8 1985.64   958.8 1991.09   978.7 2001.89   998.6 2007.34  1018.5 2017.15
#Mann= 3 , 0 , 0
       0      .1       0   469.1    .045       0   484.1      .1       0
Bank Sta=469.1,484.1
XS Rating Curve= 0 ,0
Exp/Cntr=0.3,0.1

Type RM Length L Ch R = 1 ,16787.9 ,357.9,354.7,351.5
XS GIS Cut Line= 2
     1887454.403      217936.217     1887109.766      218961.086
#Sta/Elev= 30
       0 1806.92    39.7 1788.48    49.6  1786.9    89.3 1762.22     119 1747.68
   188.5 1724.68   218.2 1718.21     248 1715.29   426.6 1718.17   466.2 1715.75
   521.3 1707.12   525.8 1706.66   536.3 1706.78   595.2  1711.8   605.1 1713.95
     615 1719.56   634.9  1739.6   644.8 1747.03   654.7 1749.28   734.1 1814.95
   753.9 1826.96   783.7 1855.51   843.2 1891.79   853.1 1892.77   932.5  1948.8
   952.3 1954.26   972.2 1964.09  1041.6 2003.48  1051.5 2004.69  1081.3  2016.4
#Mann= 3 , 0 , 0
       0      .1       0   521.3    .045       0   536.3      .1       0
Bank Sta=521.3,536.3
XS Rating Curve= 0 ,0
Exp/Cntr=0.3,0.1

Type RM Length L Ch R = 1 ,16433.3 ,342,322.2,303.6
XS GIS Cut Line= 3
     1887046.906      217803.386     1886929.835      218431.517
      1886988.12      218937.102
#Sta/Elev= 30
       0 1779.75    59.9 1766.08    79.9 1763.65   159.7 1743.26   269.6  1723.2
   309.5 1712.64   429.3 1706.69   509.2  1708.8   534.8 1703.11   539.1 1702.13
   549.8 1703.53     599 1707.79     609 1711.78     639 1731.51   658.9 1738.55
   708.8 1773.48   738.7 1796.76   758.7 1804.71   818.6 1854.76   838.5 1865.79
   858.5  1872.4   928.3 1918.45   948.3 1924.46   988.2 1943.38  1028.1 1955.65
  1058.1 1961.69    1088  1973.3  1127.9 1992.16  1137.9 1993.14  1147.9 1998.93
#Mann= 3 , 0 , 0
       0      .1       0   534.8    .045       0   549.8      .1       0
Bank Sta=534.8,549.8
XS Rating Curve= 0 ,0
Exp/Cntr=0.3,0.1

Type RM Length L Ch R = 1 ,16111   ,390.6,390.2,388.3
XS GIS Cut Line= 3
      1886311.35      217969.547     1886756.479      218508.064
     1886909.893      218952.016
#Sta/Elev= 30
       0 1800.12    59.9 1777.48   169.7 1743.76   229.6 1710.34   259.5 1700.93
   379.3 1699.86   419.2 1702.59   533.1 1694.51     539 1694.36   548.1 1694.67
   618.8 1699.44   668.7 1706.16   688.7 1718.06   718.7  1742.3   728.6 1745.44
   788.6 1797.87   818.6  1822.4   838.6 1833.07   848.6 1841.77   858.6 1848.08
   928.5 1883.26   938.5 1884.53  1018.5 1926.99  1038.5 1935.31  1058.4 1951.48
  1078.4 1962.88  1098.4 1971.76  1128.4 1980.53  1148.4 1984.19  1168.4 1992.57
#Mann= 3 , 0 , 0
       0      .1       0   533.1    .045       0   548.1      .1       0
Bank Sta=533.1,548.1
XS Rating Curve= 0 ,0
Exp/Cntr=0.3,0.1

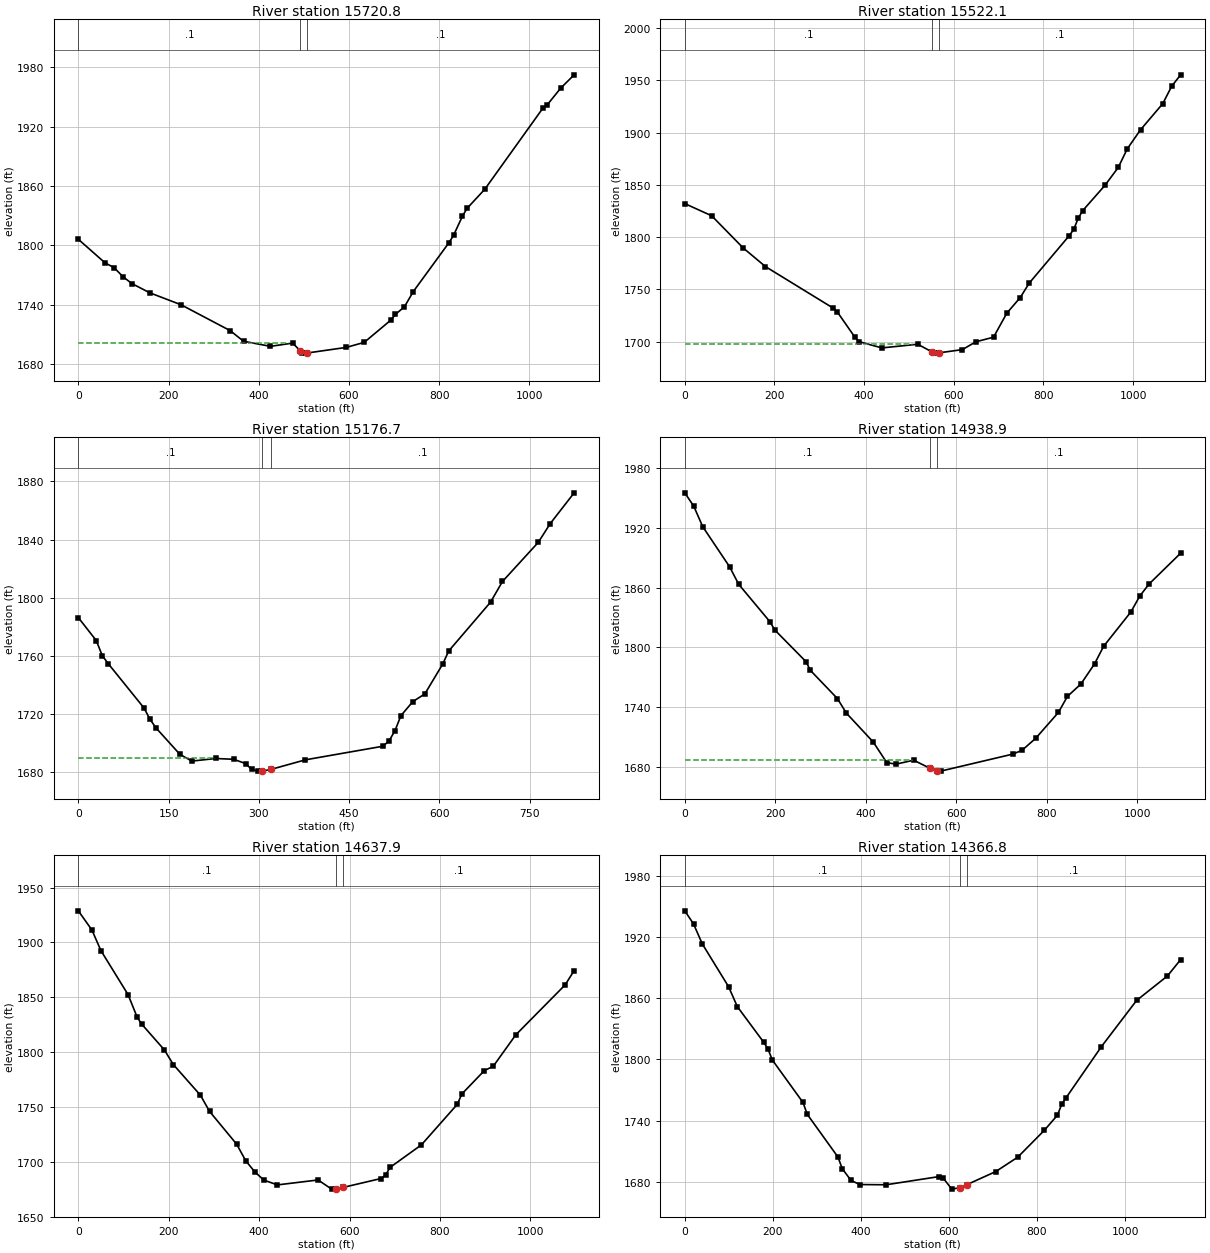
Type RM Length L Ch R = 1 ,15720.8 ,204.8,198.7,194.4
XS GIS Cut Line= 3
     1886096.475      218170.246     1886225.318      218358.077
     1886807.818      219006.519
#Sta/Elev= 30
       0 1806.08    59.4 1782.24    79.2  1777.5      99  1768.3   118.8 1761.38
   158.4 1752.06   227.8 1739.97   336.7 1713.84   366.4  1703.1   425.9 1697.99
   475.4 1701.26   492.3 1693.31   495.2  1691.6   505.1 1691.13   507.3 1691.25
   594.3 1696.92   633.9    1702   693.3 1724.62   703.2 1730.33     723 1737.89
   742.8 1753.36   822.1 1802.85     832 1810.14   851.8 1829.57   861.7  1837.2
   901.3 1856.67  1030.1 1938.56    1040 1942.07  1069.7 1958.82  1099.4  1972.2
#Mann= 3 , 0 , 0
       0      .1       0   492.3    .045       0   507.3      .1       0
#XS Ineff= 2 , 0
          464.69  1701.4
Permanent Ineff=
       F       F
Bank Sta=492.3,507.3
XS Rating Curve= 0 ,0
Exp/Cntr=0.3,0.1

Type RM Length L Ch R = 1 ,15522.1 ,353.6,345.4,335.6
XS GIS Cut Line= 3
     1885852.441      218429.725     1886319.817      218737.531
     1886754.598      219068.753
#Sta/Elev= 30
       0  1832.1      60 1820.42   129.9 1789.76   179.9  1771.8   329.8 1732.32
   339.8 1728.61   379.8 1703.95   389.7 1699.77   439.7 1693.88   519.7  1697.4
   552.1 1689.93   559.6 1688.89   567.1 1689.17   619.3 1692.26   649.1 1699.71
   688.8 1704.17   718.6 1727.27   748.4 1742.13   768.3 1755.88   857.8 1801.42
   867.7 1807.39   877.6 1817.93   887.6  1825.3   937.3 1849.53   967.1 1866.73
     987 1884.46  1016.8 1902.84  1066.4 1927.86  1086.3 1944.52  1106.2 1955.43
#Mann= 3 , 0 , 0
       0      .1       0   552.1    .045       0   567.1      .1       0
#XS Ineff= 2 , 0
          506.56 1697.97
Permanent Ineff=
       F       F
Bank Sta=552.1,567.1
XS Rating Curve= 0 ,0
Exp/Cntr=0.3,0.1

Type RM Length L Ch R = 1 ,15176.7 ,241.9,237.8,235.5
XS GIS Cut Line= 2
     1885815.408      218935.823     1886616.895      219127.189
#Sta/Elev= 30
       0 1786.21    29.8 1770.43    39.7  1760.1    49.6 1754.54   109.2 1723.93
   119.1 1716.14   129.1 1710.22   168.8 1692.02   188.6 1687.37   228.3 1689.16
   258.1 1688.62     278 1685.66   287.9 1681.69   297.8 1680.46   305.6 1680.46
   320.6 1681.71   377.3 1688.24   506.3 1697.62   516.2  1701.2   526.2 1708.28
   536.1 1718.67     556 1728.41   575.8 1733.62   605.6 1754.25   615.5 1763.22
     685 1796.85   704.9 1811.13   764.4 1838.08   784.3 1851.03     824 1872.19
#Mann= 3 , 0 , 0
       0      .1       0   305.6    .045       0   320.6      .1       0
#XS Ineff= 2 , 0
           227.9  1689.6
Permanent Ineff=
       F       F
Bank Sta=305.6,320.6
XS Rating Curve= 0 ,0
Exp/Cntr=0.3,0.1

Type RM Length L Ch R = 1 ,14938.9 ,302.6,300.8,297.3
XS GIS Cut Line= 3
     1885507.185      219217.941     1886052.147      219236.667
     1886597.621      219307.562
#Sta/Elev= 30
       0 1955.09    19.8 1941.64    39.7 1921.05    99.1 1880.77     119 1863.32
   188.4 1825.53   198.3 1817.65   267.7 1785.66   277.6 1776.81   337.1 1748.61
   356.9 1734.01   416.4  1704.9   446.1 1684.37     466 1682.72   505.6 1686.72
   541.7 1678.59   556.7 1675.88   565.3 1675.75   725.3 1692.91   745.3 1696.77
   775.3 1708.72   825.3 1734.61   845.3 1750.73   875.3  1763.3   905.3 1783.48
   925.3 1801.05   985.3  1835.4  1005.3 1851.53  1025.3 1863.38  1095.4  1894.5
#Mann= 3 , 0 , 0
       0      .1       0   541.7    .045       0   556.7      .1       0
#XS Ineff= 2 , 0
          502.01 1686.84
Permanent Ineff=
       F       F
Bank Sta=541.7,556.7
XS Rating Curve= 0 ,0
Exp/Cntr=0.3,0.1

Type RM Length L Ch R = 1 ,14637.9 ,278.5,271.2,263.9
XS GIS Cut Line= 3
     1885498.081      219491.884     1886046.602      219535.816
     1886592.622      219519.268
#Sta/Elev= 30
       0 1928.86      30  1911.4      50 1892.57   110.1 1852.39   130.1 1831.92
   140.1  1825.6   190.1 1802.18   210.1 1788.75   270.1 1760.75   290.2 1746.05
   350.2 1716.12   370.2 1701.06   390.2 1690.97   410.2 1683.44   440.2 1679.04
   530.3 1683.54   560.2 1675.19   570.1 1675.53   585.1  1676.7   669.5 1684.87
   679.4 1687.85   689.3 1694.97   758.8 1715.54   838.3 1752.58   848.2  1761.9
   897.9  1783.2   917.8 1787.25   967.4 1815.77  1076.7 1861.37  1096.6 1874.41
#Mann= 3 , 0 , 0
       0      .1       0   570.1    .045       0   585.1      .1       0
Bank Sta=570.1,585.1
XS Rating Curve= 0 ,0
Exp/Cntr=0.3,0.1

Type RM Length L Ch R = 1 ,14366.8 ,501,512.1,523.2
XS GIS Cut Line= 3
     1885517.713      219870.535     1886101.172      219811.566
     1886607.502      219624.276
#Sta/Elev= 30
       0 1945.67    19.9 1932.78    39.8  1913.2    99.4 1871.35   119.3 1851.78
   178.9 1817.06   188.8 1810.42   198.8 1799.47   268.4 1757.89   278.3 1746.12
   347.9 1704.36   357.8 1692.77   377.7  1681.4   397.6 1677.39   457.2 1677.16
   576.5 1685.11   586.4 1684.08   606.4 1672.89   626.1 1674.38   641.1 1677.35
   706.4 1690.11   756.4 1704.25   816.4  1730.4   846.4 1745.31   856.4 1756.29
   866.4 1762.62   946.3 1812.52  1026.3 1857.84  1096.3 1881.81  1126.3 1897.85
#Mann= 3 , 0 , 0
       0      .1       0   626.1    .045       0   641.1      .1       0
Bank Sta=626.1,641.1
XS Rating Curve= 0 ,0
Exp/Cntr=0.3,0.1

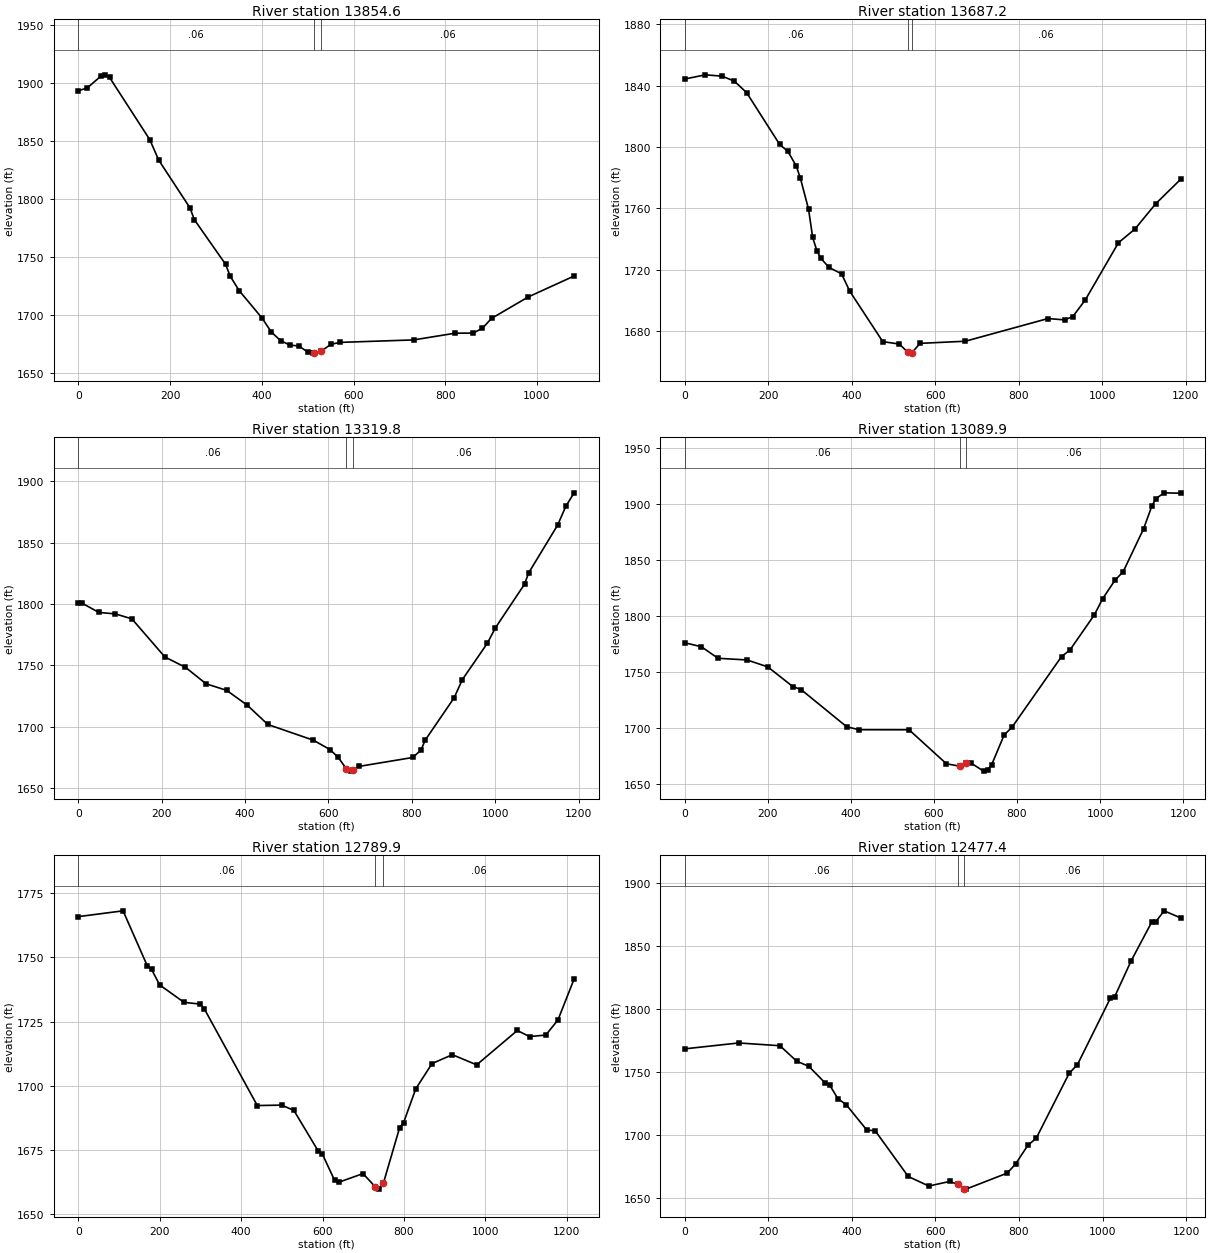
Type RM Length L Ch R = 1 ,13854.6 ,164.3,167.4,170.5
XS GIS Cut Line= 3
     1885475.452      220144.807       1885801.9      220198.839
     1886547.571      220281.582
#Sta/Elev= 30
       0 1893.47    19.5 1895.92    48.7 1905.88    58.4 1907.18    68.1  1904.9
   155.7 1851.38   175.2 1833.74   243.3 1792.63     253 1782.34   321.2 1743.87
   330.9 1733.84   350.9 1721.14   400.9 1697.47   420.9 1685.48   440.9 1678.25
   460.9 1674.37   480.9 1673.53     501 1668.11     511  1667.4   514.2 1667.48
   529.2 1669.01     551 1675.04     571 1676.66     731 1678.78     821 1684.54
   861.1  1684.7   881.1 1688.86   901.1 1697.37   981.1 1715.83  1081.1 1733.85
#Mann= 3 , 0 , 0
       0     .06       0   514.2    .045       0   529.2     .06       0
Bank Sta=514.2,529.2
XS Rating Curve= 0 ,0
Exp/Cntr=0.3,0.1

Type RM Length L Ch R = 1 ,13687.2 ,367.1,367.2,367.3
XS GIS Cut Line= 3
     1885435.445       220253.58     1886184.632      220435.233
     1886571.867      220590.577
#Sta/Elev= 30
       0 1844.34    49.4 1847.06      89  1846.2   118.6 1842.98   148.2 1835.42
   227.3 1801.72   247.1 1797.14   266.8 1787.76   276.7 1779.99   296.5 1759.56
   306.4 1741.16   316.3  1732.6   326.2  1727.4   345.9 1721.53   375.6 1717.41
   395.3 1706.06   474.4 1673.22   513.9 1671.68   533.7 1666.51   543.6 1665.74
   563.4  1672.1   672.1 1673.49   870.2 1688.27     910 1687.41   929.8 1689.58
   959.6 1700.38  1039.1 1737.65  1078.8 1746.64  1128.5 1763.09  1188.1 1778.97
#Mann= 3 , 0 , 0
       0     .06       0   533.7    .045       0   543.6     .06       0
Bank Sta=533.7,543.6
XS Rating Curve= 0 ,0
Exp/Cntr=0.3,0.1

Type RM Length L Ch R = 1 ,13319.8 ,215.1,230,243.2
XS GIS Cut Line= 3
     1885408.739      220334.894       1885718.6       220694.14
     1886410.911      220872.342
#Sta/Elev= 30
       0 1800.57     9.9 1800.56    49.4 1793.19      89 1792.01   128.5 1787.94
   207.6 1756.88     257 1748.46   306.4 1735.02   355.8 1729.67   405.2 1717.57
   454.6 1701.84   563.8 1689.02   603.5 1681.44   623.4 1675.06   643.2 1665.54
   653.1 1663.82   658.2 1664.83     673 1667.66   802.1 1674.94   821.9 1680.94
   831.9 1689.02   901.4 1723.62   921.2  1738.5   980.8 1767.93  1000.6 1780.73
  1070.2 1816.19  1080.1 1825.41  1149.6 1864.37  1169.4 1879.82  1189.3 1890.72
#Mann= 3 , 0 , 0
       0     .06       0   643.2    .045       0   658.2     .06       0
Bank Sta=643.2,658.2
XS Rating Curve= 0 ,0
Exp/Cntr=0.3,0.1

Type RM Length L Ch R = 1 ,13089.9 ,292.8,299.9,307
XS GIS Cut Line= 3
     1885361.486      220401.295     1885771.178      220931.459
     1886124.655      221318.434
#Sta/Elev= 30
       0 1775.93      40 1772.38      80 1762.09     150 1760.59     200  1754.4
     260  1736.9     280 1734.21     390    1701     420 1698.39     540 1698.35
     630 1668.06   662.5 1665.84   677.5  1668.6   689.8 1668.59   719.5 1661.48
   729.4 1662.64   739.2 1667.34   768.9 1693.57   788.7 1700.98   907.4 1763.68
   927.1 1769.24   986.5 1800.89  1006.2 1815.13  1035.9 1831.66  1055.7 1839.25
  1105.1  1877.7  1124.9 1897.96  1134.8 1904.52  1154.6 1909.61  1194.1 1909.25
#Mann= 3 , 0 , 0
       0     .06       0   662.5    .045       0   677.5     .06       0
Bank Sta=662.5,677.5
XS Rating Curve= 0 ,0
Exp/Cntr=0.3,0.1

Type RM Length L Ch R = 1 ,12789.9 ,302.3,312.4,324.3
XS GIS Cut Line= 3
     1885292.567      220444.773     1885527.128      221103.745
     1885741.259      221576.342
#Sta/Elev= 30
       0 1765.84   109.9  1768.1   169.9 1746.53   179.9 1745.33   199.8 1739.28
   259.8 1732.48   299.8 1731.82   309.8 1729.89   439.7 1692.35   499.6 1692.51
   529.6 1690.46   589.6 1674.61   599.6 1673.48   629.5 1663.29   639.5 1662.49
   699.5 1665.87   729.4 1660.76   739.4 1659.83   749.4 1662.06   789.3 1683.68
   799.2 1685.72   829.2 1698.88   869.1 1708.68     919 1712.13   978.8 1708.18
  1078.6 1721.55  1108.6 1719.18  1148.5 1719.77  1178.4 1725.61  1218.3 1741.63
#Mann= 3 , 0 , 0
       0     .06       0   729.4    .045       0   749.4     .06       0
Bank Sta=729.4,749.4
XS Rating Curve= 0 ,0
Exp/Cntr=0.3,0.1

Type RM Length L Ch R = 1 ,12477.4 ,346.5,358.5,370.5
XS GIS Cut Line= 3
     1885212.642      220453.197     1885233.386      220987.706
      1885164.93      221636.166
#Sta/Elev= 30
       0 1768.69   128.8 1773.36   227.8 1771.16   267.5    1759   297.2 1754.72
   336.8 1741.31   346.7    1740   366.5 1729.12   386.3 1724.42   435.8 1704.17
   455.7 1703.69   534.9 1667.33   584.3 1659.75   633.7 1663.38   653.8 1661.08
   668.8 1657.75   673.2  1657.3     772 1670.04   791.8 1677.24   821.4 1692.16
   841.2 1697.63   920.2 1749.31     940 1756.17    1019    1809  1028.9 1809.93
  1068.4 1838.46  1117.8 1869.32  1127.7  1869.7  1147.5 1878.28    1187 1872.68
#Mann= 3 , 0 , 0
       0     .06       0   653.8    .045       0   668.8     .06       0
Bank Sta=653.8,668.8
XS Rating Curve= 0 ,0
Exp/Cntr=0.3,0.1

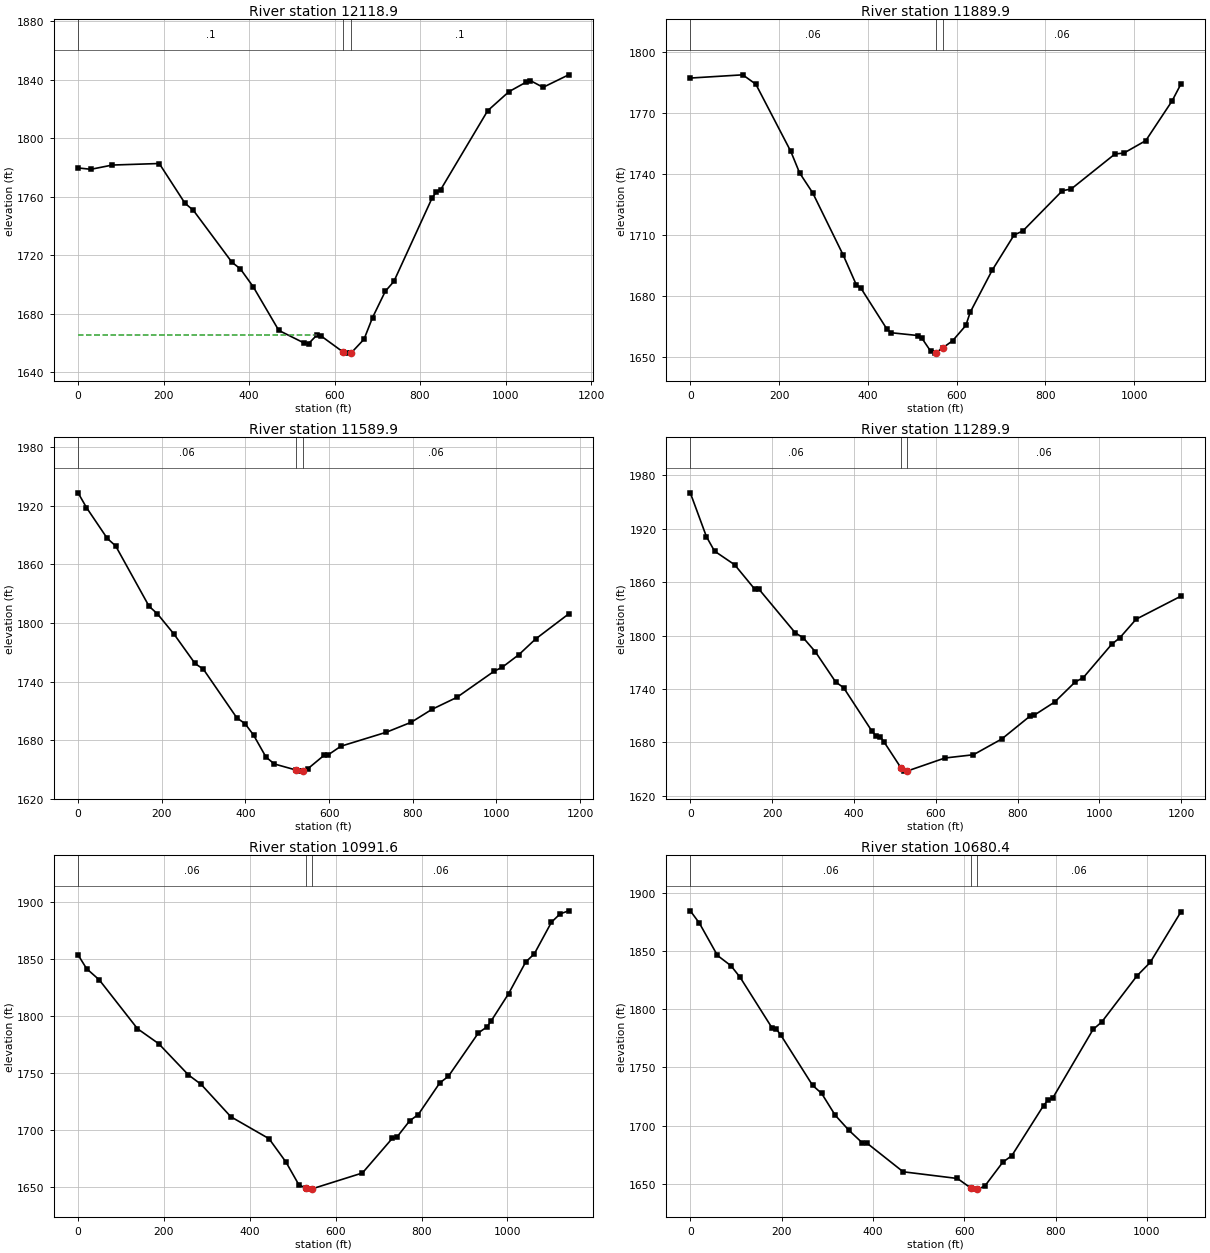
Type RM Length L Ch R = 1 ,12118.9 ,228.8,229,228.3
XS GIS Cut Line= 3
     1885132.608      220436.431     1885054.447       220777.44
     1884580.192      221418.999
#Sta/Elev= 30
       0 1779.72      30 1778.78      80 1781.69   189.9 1782.74   249.9 1755.65
   269.9 1750.68   359.8 1715.32   379.8 1710.68   409.7 1698.53   469.5  1668.7
   529.4 1659.97   539.3 1659.66   559.3 1665.68   569.2 1664.72   619.1 1654.11
   629.1 1653.15   639.1 1653.35     669 1662.66   688.9 1677.45   718.8 1695.45
   738.8 1702.13   828.5 1759.35   838.5 1763.38   848.5 1764.96   958.2  1818.8
    1008 1831.84  1047.9 1838.31  1057.9 1839.46  1087.8  1834.8  1147.7 1843.35
#Mann= 3 , 0 , 0
       0      .1       0   619.1    .045       0   639.1      .1       0
#XS Ineff= 2 , 0
          559.19 1665.68
Permanent Ineff=
       F       F
Bank Sta=619.1,639.1
XS Rating Curve= 0 ,0
Exp/Cntr=0.3,0.1

Type RM Length L Ch R = 1 ,11889.9 ,304.9,300,292.5
XS GIS Cut Line= 3
     1885063.085      220388.404     1884726.661      220837.764
     1884417.146      221284.959
#Sta/Elev= 30
       0 1787.13   118.2 1788.72   147.7 1784.09   226.5 1751.01   246.2 1740.49
   275.8 1730.64   344.7 1699.95   374.2 1685.33   384.1 1683.87   443.2 1663.55
     453 1661.84   512.1 1660.49     522 1659.08   541.6 1652.74   551.5 1651.82
   553.8 1652.11   568.8 1654.41     591 1657.92   620.7 1665.42   630.6 1671.93
     680 1692.57   729.4 1709.92   749.2 1711.92   838.2 1731.71     858 1732.54
   956.9 1749.81   976.6 1750.21  1026.1 1756.35  1085.4 1775.89  1105.2 1784.16
#Mann= 3 , 0 , 0
       0     .06       0   553.8    .045       0   568.8     .06       0
Bank Sta=553.8,568.8
XS Rating Curve= 0 ,0
Exp/Cntr=0.3,0.1

Type RM Length L Ch R = 1 ,11589.9 ,313.2,300.1,292.9
XS GIS Cut Line= 3
     1884746.654      220137.605     1884528.304      220619.515
     1884351.431       221238.13
#Sta/Elev= 30
       0 1933.27      20 1918.22    69.9 1886.52    89.8 1878.91   169.7 1817.06
   189.7  1809.3   229.6 1788.36   279.5 1758.47   299.5  1752.6   379.3 1702.87
   399.3 1696.71   419.3 1685.23   449.2 1662.56   469.2 1655.54   521.6 1649.26
   529.1 1648.22   536.6 1648.25   548.9 1650.56   588.5 1664.64   598.4 1665.08
     628 1673.71   736.9 1688.08   796.3  1698.3   845.8  1711.5   905.2 1723.74
   994.3 1750.52  1014.1 1754.73  1053.7 1767.59  1093.3 1783.49  1172.5 1809.24
#Mann= 3 , 0 , 0
       0     .06       0   521.6    .045       0   536.6     .06       0
Bank Sta=521.6,536.6
XS Rating Curve= 0 ,0
Exp/Cntr=0.3,0.1

Type RM Length L Ch R = 1 ,11289.9 ,309,298.1,284.6
XS GIS Cut Line= 3
     1884171.121      220030.358     1884252.158      220546.926
     1884274.047      221222.862
#Sta/Elev= 30
       0  1960.5    39.5 1911.17    59.2    1895   108.5 1879.61   157.8 1852.06
   167.7 1852.22   256.5 1803.13   276.2 1797.46   305.8 1781.74   355.2 1747.96
   374.9 1741.36     444 1692.59   453.8 1687.47   463.7 1686.52   473.6 1680.44
   515.4 1651.03   522.9 1647.64   530.4 1647.76   622.3 1662.39     692 1666.04
   761.6 1683.85   831.2  1709.8   841.1 1710.66   890.9 1725.39   940.6 1747.79
   960.5 1752.67  1030.1 1790.24    1050 1797.57  1089.8 1818.42  1199.2 1844.32
#Mann= 3 , 0 , 0
       0     .06       0   515.4    .045       0   530.4     .06       0
Bank Sta=515.4,530.4
XS Rating Curve= 0 ,0
Exp/Cntr=0.3,0.1

Type RM Length L Ch R = 1 ,10991.6 ,302.6,311.1,319.5
XS GIS Cut Line= 3
     1883678.984      220252.449     1884062.937      220779.695
     1884199.095      221250.812
#Sta/Elev= 30
       0 1853.74    19.8 1841.64    49.4 1831.74   138.4 1788.81   187.8 1775.63
   256.9 1748.23   286.6 1739.87   355.8  1711.4   444.7 1692.12   484.2 1671.57
   513.9 1651.78   530.7 1648.44   533.6 1647.76   545.7  1648.1   662.2 1661.95
   732.3 1692.61   742.3 1693.39   772.3  1707.8   792.4 1713.37   842.4 1741.16
   862.4 1746.92   932.5 1785.19   952.5 1790.45   962.5 1795.89  1002.5 1819.49
  1042.6  1847.5  1062.6 1854.64  1102.6 1882.51  1122.6 1889.76  1142.6 1892.47
#Mann= 3 , 0 , 0
       0     .06       0   530.7    .045       0   545.7     .06       0
Bank Sta=530.7,545.7
XS Rating Curve= 0 ,0
Exp/Cntr=0.3,0.1

Type RM Length L Ch R = 1 ,10680.4 ,275,287.5,300
XS GIS Cut Line= 3
     1883603.226      220292.695     1883825.201      221126.402
     1883899.496      221324.522
#Sta/Elev= 30
       0 1884.34    19.8 1873.84    59.5 1846.03    89.2 1837.14   109.1 1827.26
   178.5 1784.14   188.4 1782.75   198.3 1777.63   267.8 1734.53   287.6 1727.61
   317.3 1708.89   347.1 1696.02   376.8 1685.11   386.8 1684.93   466.1 1660.32
   585.1 1654.56   613.8 1646.51   624.8 1645.43   628.8 1645.46   644.6 1647.86
   684.2  1668.5   704.1 1674.17   773.5 1717.14   783.4  1721.9   793.3 1723.36
     882 1782.49   901.2 1789.02   978.2 1828.55    1007    1840  1074.3  1883.4
#Mann= 3 , 0 , 0
       0     .06       0   613.8    .045       0   628.8     .06       0
Bank Sta=613.8,628.8
XS Rating Curve= 0 ,0
Exp/Cntr=0.3,0.1

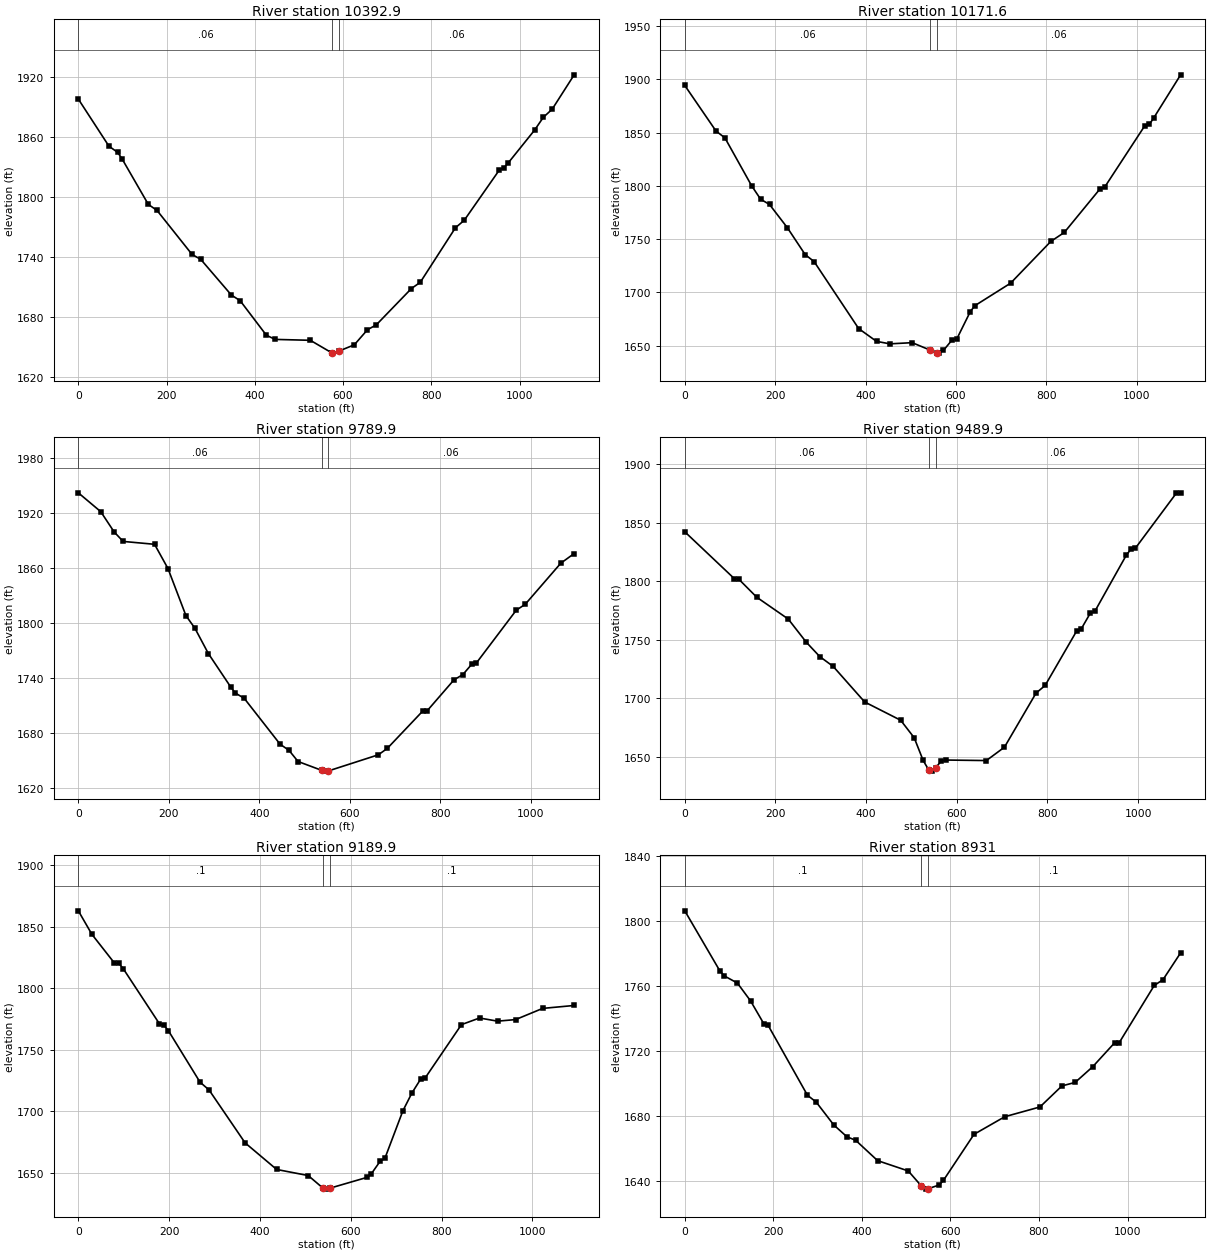
Type RM Length L Ch R = 1 ,10392.9 ,217.9,221.2,224.9
XS GIS Cut Line= 3
     1883519.741      220294.101      1883525.77      220730.162
     1883325.585       221388.08
#Sta/Elev= 30
       0 1898.07    69.4 1850.89    89.2 1844.68    99.1  1838.2   158.6 1792.61
   178.4 1786.52   257.7 1742.49   277.5 1737.52   346.9 1701.78   366.7 1696.18
   426.2 1661.54   446.1 1657.36   525.8 1656.47   575.6 1643.62   575.8 1643.64
   590.8  1645.7   625.5 1651.95   655.4 1667.07   675.3 1671.92     755 1708.35
     775 1714.53   854.7 1769.19   874.6 1776.63   954.4 1827.16   964.3 1829.22
   974.3 1834.11  1034.1    1867    1054 1879.85    1074 1887.94  1123.8 1922.37
#Mann= 3 , 0 , 0
       0     .06       0   575.8    .045       0   590.8     .06       0
Bank Sta=575.8,590.8
XS Rating Curve= 0 ,0
Exp/Cntr=0.3,0.1

Type RM Length L Ch R = 1 ,10171.6 ,381.5,381.7,379.2
XS GIS Cut Line= 3
     1883509.848      220301.441     1883273.282      220800.944
     1883031.419      221289.135
#Sta/Elev= 30
       0 1894.16    69.1  1851.4    88.8    1845     148 1800.01   167.8 1787.45
   187.5  1782.5     227 1760.71   266.5 1735.45   286.2 1728.93   384.9 1666.04
   424.4 1654.06     454 1651.74   503.3 1652.84   542.8 1645.91   557.8  1643.2
   562.6 1643.03   572.5 1645.56   592.3 1655.76   602.2 1656.47   631.9 1681.91
   641.8 1687.48   721.1 1708.65   810.2 1747.84     840 1756.26   919.2 1797.19
   929.1 1798.59  1018.3 1856.44  1028.2  1857.6  1038.1  1863.8  1097.5 1904.14
#Mann= 3 , 0 , 0
       0     .06       0   542.8    .045       0   557.8     .06       0
Bank Sta=542.8,557.8
XS Rating Curve= 0 ,0
Exp/Cntr=0.3,0.1

Type RM Length L Ch R = 1 ,9789.9  ,312.7,300.1,291.6
XS GIS Cut Line= 3
      1883176.29       220134.33     1882936.367      220623.823
      1882749.38      221142.052
#Sta/Elev= 30
       0 1942.08    49.6 1921.51    79.3 1899.31    99.1 1889.06   168.5 1885.93
   198.2 1859.45   237.9 1808.08   257.7 1794.36   287.4 1766.78     337 1730.15
   346.9 1723.72   366.7 1717.89     446 1667.84   465.8  1661.1   485.7 1648.96
   537.6 1639.38   545.1 1638.46   552.6 1638.66   663.2 1656.27   682.9 1663.19
   761.6 1704.12   771.4 1704.43   830.4 1738.03   850.1 1743.82   869.8 1755.13
   879.6  1756.2   968.2 1814.09   987.8  1820.4  1066.6 1865.31  1096.1 1875.84
#Mann= 3 , 0 , 0
       0     .06       0   537.6    .045       0   552.6     .06       0
Bank Sta=537.6,552.6
XS Rating Curve= 0 ,0
Exp/Cntr=0.3,0.1

Type RM Length L Ch R = 1 ,9489.9  ,299.3,299.9,299.1
XS GIS Cut Line= 3
     1882586.052      220038.546     1882645.735      220580.906
     1882662.496      221128.724
#Sta/Elev= 30
       0 1842.24   109.1 1802.31     119 1801.82   158.7  1786.4   228.2 1767.76
   267.9 1748.05   297.6 1735.78   327.4 1727.31   396.8 1696.99   476.2  1681.4
     506 1666.47   525.8 1647.08   538.1 1638.95   545.6 1637.98   553.1 1640.84
   565.6 1646.48   575.5 1647.45   665.2    1647   705.1 1658.42   774.8 1704.59
   794.8 1711.07   864.5 1757.68   874.5 1759.39   894.4 1772.75   904.4  1774.3
   974.1 1822.43   984.1 1827.38   994.1 1828.35  1083.7 1874.94  1093.7  1875.5
#Mann= 3 , 0 , 0
       0     .06       0   538.1    .045       0   553.1     .06       0
Bank Sta=538.1,553.1
XS Rating Curve= 0 ,0
Exp/Cntr=0.3,0.1

Type RM Length L Ch R = 1 ,9189.9  ,256,258.7,261
XS GIS Cut Line= 3
     1882303.848      220056.487     1882346.562      220600.803
     1882382.058      221145.707
#Sta/Elev= 30
       0    1863    29.8 1843.93    79.4 1820.58    89.3 1820.24    99.3 1815.74
   178.7 1771.12   188.6 1769.94   198.5 1765.47     268 1723.73   287.9 1717.38
   367.3 1674.37   436.8 1652.74   506.3  1647.8   538.5 1637.67     546 1636.76
   553.5 1637.46   635.3 1646.26   645.3 1649.22   665.1 1659.62   675.1 1661.72
   714.8 1700.44   734.6 1714.85   754.5 1726.53   764.4 1727.43   843.8  1770.5
   883.6 1775.87   923.3 1773.31     963 1774.58  1022.6 1783.68    1092 1786.06
#Mann= 3 , 0 , 0
       0      .1       0   538.5    .045       0   553.5      .1       0
Bank Sta=538.5,553.5
XS Rating Curve= 0 ,0
Exp/Cntr=0.3,0.1

Type RM Length L Ch R = 1 ,8931    ,353.6,339.1,325
XS GIS Cut Line= 3
     1882110.223      220046.797     1882084.896      220689.637
     1882202.212      221151.618
#Sta/Elev= 30
       0 1806.23    79.2 1769.34    89.1 1766.28   118.8 1761.86   148.5 1750.94
   178.2 1737.01     188    1736   277.1 1692.95   296.9 1688.74   336.5 1674.72
   366.2 1667.45     386 1665.29   435.5  1652.8   504.8 1646.46   533.8 1637.41
   544.4  1635.3   548.8  1635.5   574.1 1637.78     584  1640.6   653.3 1668.96
   722.8 1679.78   802.2 1685.76   851.9  1698.7   881.7 1700.83   921.4 1710.47
     971 1725.21     981 1725.12  1060.4 1760.38  1080.3 1763.99    1120 1780.43
#Mann= 3 , 0 , 0
       0      .1       0   533.8    .045       0   548.8      .1       0
Bank Sta=533.8,548.8
XS Rating Curve= 0 ,0
Exp/Cntr=0.3,0.1

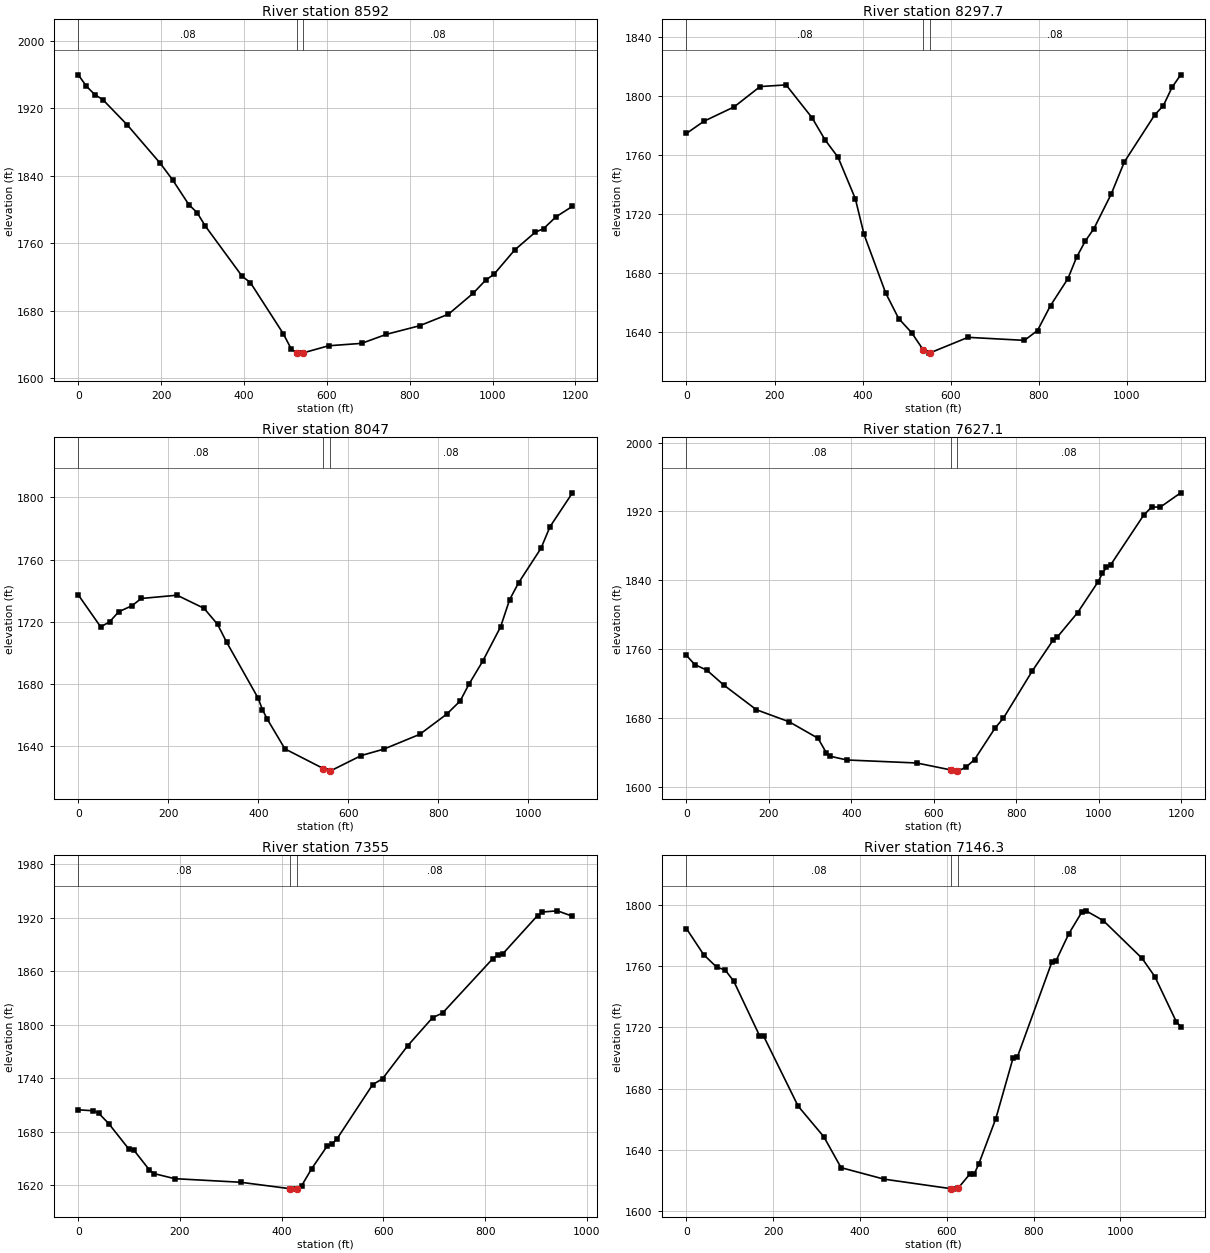
Type RM Length L Ch R = 1 ,8592    ,307.2,294.1,287.1
XS GIS Cut Line= 3
     1881459.448      220181.413     1881759.666      220611.305
     1882125.418      221171.123
#Sta/Elev= 30
       0  1959.6    19.8 1946.08    39.6 1936.26    59.4 1930.14   118.7 1900.01
   197.9 1854.73   227.6  1835.2   267.1 1805.61   286.9 1796.24   306.7 1780.35
   395.7 1720.74   415.5 1713.31   494.7  1652.9   514.4 1634.35   527.8 1629.98
   534.3 1629.67   542.8 1629.94   604.2 1638.38     684 1641.25   743.9 1651.98
   823.8 1662.11   893.6 1675.82   953.5 1700.73   983.5 1716.22  1003.4 1723.04
  1053.3 1751.85  1103.2 1773.01  1123.2 1777.22  1153.1 1791.19    1193 1803.74
#Mann= 3 , 0 , 0
       0     .08       0   527.8    .045       0   542.8     .08       0
Bank Sta=527.8,542.8
XS Rating Curve= 0 ,0
Exp/Cntr=0.3,0.1

Type RM Length L Ch R = 1 ,8297.7  ,249.8,250.7,245.1
XS GIS Cut Line= 3
     1881117.714      220680.323     1881624.969      220868.721
     1882077.932      221234.064
#Sta/Elev= 30
       0 1774.74    39.4 1782.95   108.2 1792.69   167.2 1806.45   226.3 1807.58
   285.3 1785.35   314.8 1770.39   344.3 1758.62   383.7  1730.5   403.4 1706.43
   452.6 1666.73   482.1 1649.45   511.6 1639.87   537.6 1628.38     551 1626.03
   552.6 1626.11   639.7 1636.72     768 1634.67   797.6 1641.34   827.2 1658.25
   866.6 1676.38   886.3 1690.85     906 1701.79   925.8 1710.31   965.2 1733.78
   994.8 1755.37  1063.9 1787.26  1083.6 1793.57  1103.3 1805.92    1123  1814.4
#Mann= 3 , 0 , 0
       0     .08       0   537.6    .045       0   552.6     .08       0
Bank Sta=537.6,552.6
XS Rating Curve= 0 ,0
Exp/Cntr=0.3,0.1

Type RM Length L Ch R = 1 ,8047    ,410.3,420,429.8
XS GIS Cut Line= 2
      1881038.15      220868.488     1882031.111      221337.431
#Sta/Elev= 30
       0 1737.24    49.9 1716.58    69.9 1719.92    89.8 1726.32   119.8 1730.29
   139.8  1734.9   219.6 1737.01   279.5 1728.56   309.5 1718.26   329.4 1706.87
   399.3 1670.85   409.3 1663.26   419.3 1657.44   459.2 1637.96   544.7 1625.25
     559 1623.61   559.7 1623.65   628.9 1633.66   678.8 1637.78   758.7 1647.31
   818.6 1660.31   848.6 1668.82   868.5 1679.84   898.5 1694.38   938.4  1716.6
   958.4 1734.08   978.3 1744.97  1028.2 1767.28  1048.2 1781.16  1098.1 1803.01
#Mann= 3 , 0 , 0
       0     .08       0   544.7    .045       0   559.7     .08       0
Bank Sta=544.7,559.7
XS Rating Curve= 0 ,0
Exp/Cntr=0.3,0.1

Type RM Length L Ch R = 1 ,7627.1  ,259.1,272.1,285.1
XS GIS Cut Line= 3
     1880994.008      220940.319     1881238.382      221340.282
     1881708.917       221898.62
#Sta/Elev= 30
       0 1752.79      20 1742.28    49.9 1735.54    89.8 1718.67   169.5 1689.78
   249.3 1675.72   319.1 1656.62   339.1 1639.81     349 1635.71   388.9 1631.42
   558.7 1627.92     642 1619.78     657 1618.53   658.8 1618.47   678.8 1623.35
   698.8 1631.95   748.8 1668.66   768.8 1679.99   838.8 1734.76   888.8 1770.23
   898.8 1773.74   948.8 1802.51   998.8 1838.59  1008.8 1848.11  1018.8 1855.14
  1028.8 1857.87  1108.9 1915.62  1128.9 1925.37  1148.9 1924.91  1198.9 1941.66
#Mann= 3 , 0 , 0
       0     .08       0     642    .045       0     657     .08       0
Bank Sta=642,657
XS Rating Curve= 0 ,0
Exp/Cntr=0.3,0.1

Type RM Length L Ch R = 1 ,7355    ,205,208.6,212.1
XS GIS Cut Line= 3
     1881051.519      221160.173     1881123.562      221734.271
     1881336.037      222064.786
#Sta/Elev= 30
       0 1704.68    29.9 1703.57    39.9 1701.02    59.9 1689.22    99.8 1660.46
   109.7 1659.25   139.7 1637.41   149.6 1633.16   189.5 1627.57   319.2 1623.54
   415.7 1616.37     429 1615.85   430.7 1616.48   438.9 1619.49   458.9 1638.78
   488.8 1663.68   498.8 1666.23   508.8 1672.29   578.6 1732.77   598.2 1739.51
   647.4 1776.27   696.5 1807.85   716.1 1813.02   814.4 1873.62   824.2 1877.89
     834 1878.98   902.8 1922.14   912.6 1926.15     942 1927.48   971.5 1921.42
#Mann= 3 , 0 , 0
       0     .08       0   415.7    .045       0   430.7     .08       0
Bank Sta=415.7,430.7
XS Rating Curve= 0 ,0
Exp/Cntr=0.3,0.1

Type RM Length L Ch R = 1 ,7146.3  ,317.5,315.2,313
XS GIS Cut Line= 3
     1880838.979      220992.902     1880907.431      221281.746
     1880880.415      222123.757
#Sta/Elev= 30
       0  1784.5    39.6 1767.54    69.3 1759.43      89 1757.54   108.8 1750.28
   168.2 1714.71   178.1 1714.15   257.3 1668.59   316.7 1648.52   356.3 1628.38
   455.4 1620.87   610.7  1614.6     614 1614.35   625.7 1614.81   653.6 1624.34
   663.6 1624.48   673.5 1630.56   713.1 1660.44   752.8 1699.97   762.7  1700.6
     842 1762.48   851.9 1763.56   881.6 1781.33   911.3 1795.28   921.2 1796.17
   960.9 1789.77  1050.1 1765.19  1079.8 1753.14  1129.4 1723.59  1139.3 1720.58
#Mann= 3 , 0 , 0
       0     .08       0   610.7    .045       0   625.7     .08       0
Bank Sta=610.7,625.7
XS Rating Curve= 0 ,0
Exp/Cntr=0.3,0.1