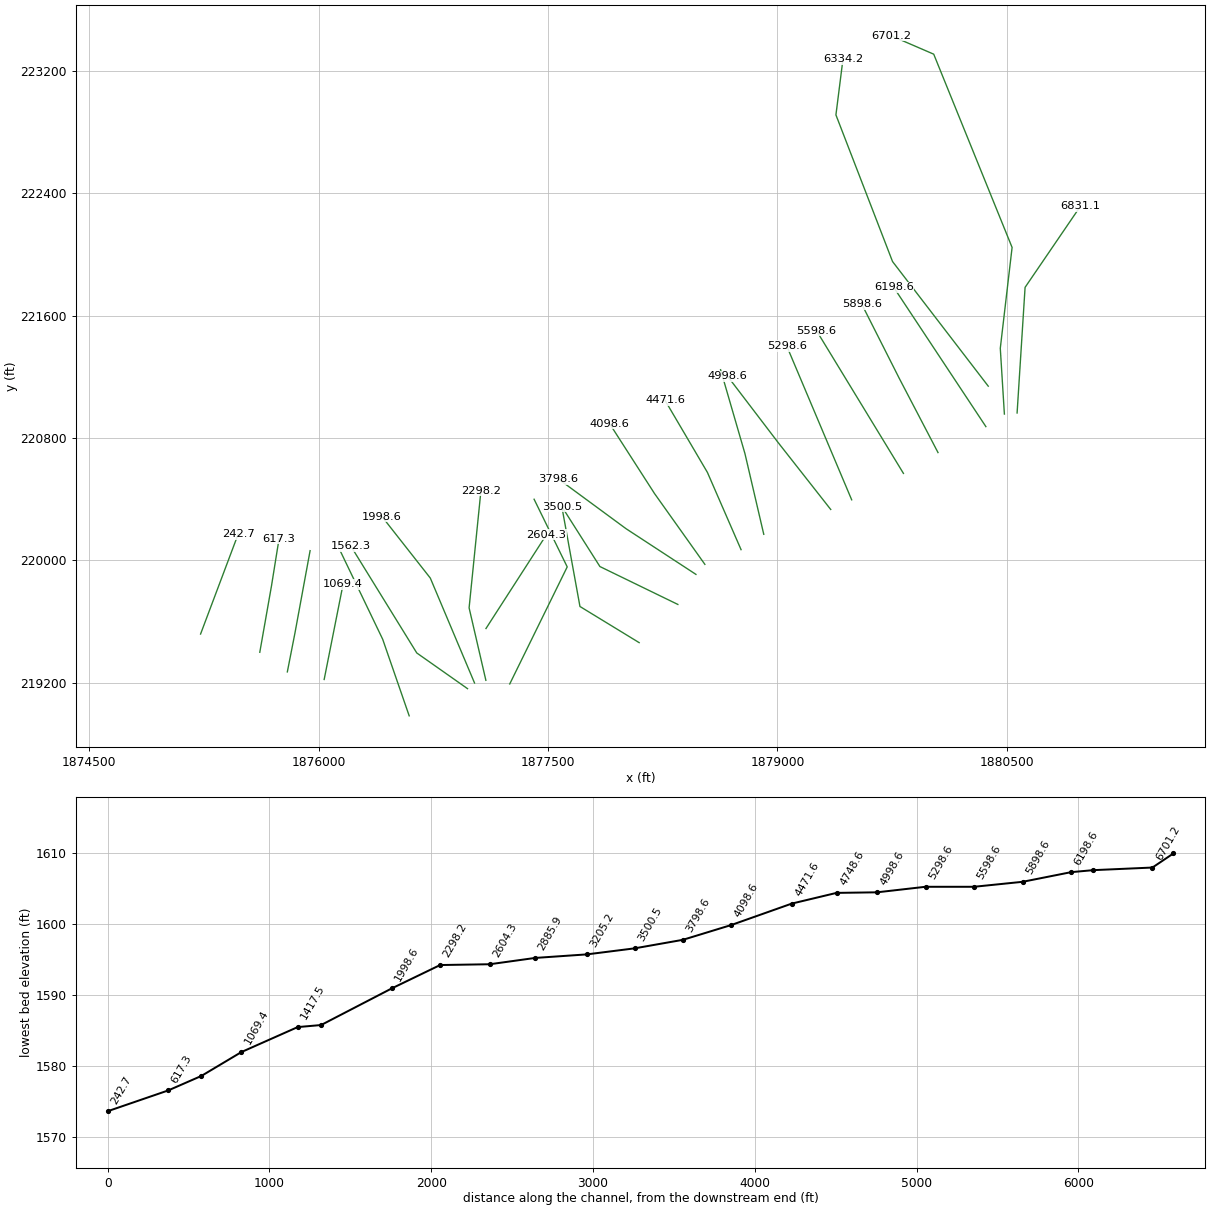
HEC-RAS study TmmyCrk.prj: TmmyCrk

--- TmmyCrk.g01 (geometry) --- (continued)

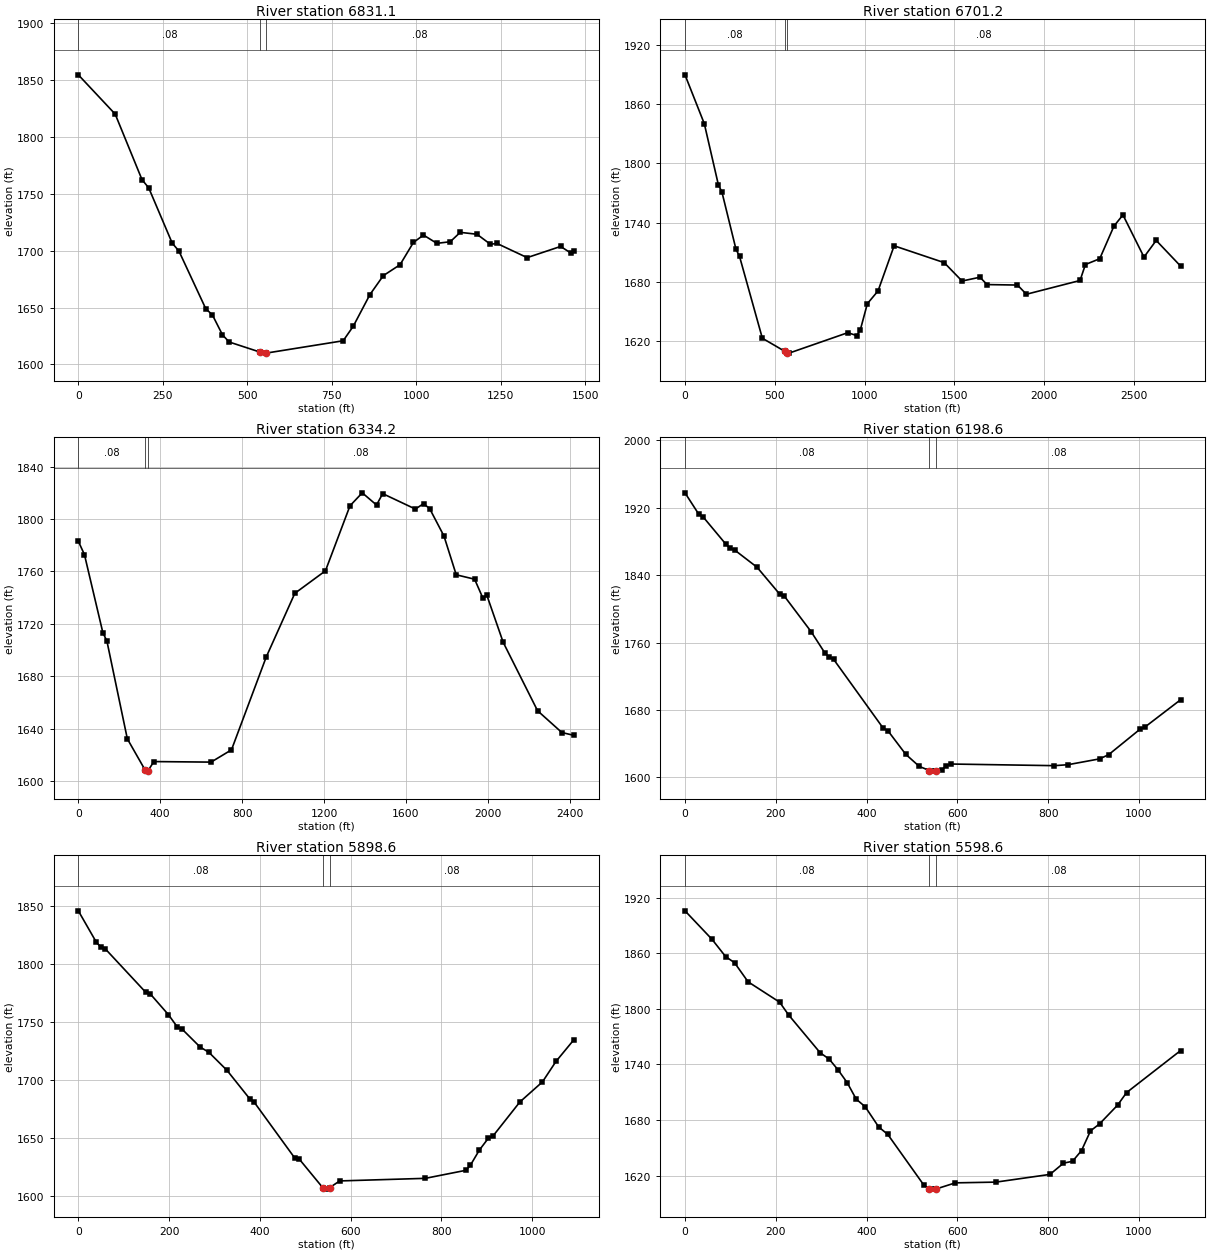
Type RM Length L Ch R = 1 ,6831.1  ,131.1,129.9,128.8
XS GIS Cut Line= 3
      1880567.05       220964.55     1880619.256      221786.052
     1880981.726      222317.374
#Sta/Elev= 30
       0 1854.75   109.1 1820.18   188.4 1762.55   208.3 1755.31   277.7 1706.76
   297.5 1699.83   376.9 1649.13   396.7 1643.57   426.5 1626.06   446.3 1619.78
   538.8 1610.79   553.8 1610.01   555.4    1610   783.5 1620.87   813.2 1633.56
   862.7  1661.5   902.3 1678.15   951.8 1687.76   991.4 1707.35  1021.1 1713.84
  1060.6 1706.55  1100.2 1707.95  1129.9 1716.22  1179.4 1714.53    1219 1705.76
  1238.8 1706.42  1327.8 1693.99  1426.8 1703.82  1456.4 1698.15  1466.3 1699.99
#Mann= 3 , 0 , 0
       0     .08       0   538.8    .045       0   553.8     .08       0
Bank Sta=538.8,553.8
XS Rating Curve= 0 ,0
Exp/Cntr=0.3,0.1

Type RM Length L Ch R = 1 ,6701.2  ,349,367,385
XS GIS Cut Line= 5
     1880483.931      220957.539     1880457.158       221387.56
     1880534.343      222047.136     1880021.793      223311.018
     1879745.213      223430.559
#Sta/Elev= 30
       0 1889.57   107.7 1840.07     186 1778.23   205.6 1771.04     284 1713.08
   303.6 1705.96   430.8 1623.07   554.2 1610.01   569.2 1608.11   579.5 1608.01
   906.6 1628.69   956.2 1625.76     976 1631.29  1015.6 1658.05  1075.1 1670.97
  1164.6 1716.59  1443.4 1699.56  1542.9 1680.95  1642.5  1684.8  1682.3 1677.36
  1851.5 1676.88  1901.3 1667.58    2200  1681.5  2229.8 1697.65  2309.5  1703.5
  2389.1 1736.64  2438.9 1747.83    2556 1705.17    2624 1722.02  2760.1 1696.03
#Mann= 3 , 0 , 0
       0     .08       0   554.2    .045       0   569.2     .08       0
Bank Sta=554.2,569.2
XS Rating Curve= 0 ,0
Exp/Cntr=0.3,0.1

Type RM Length L Ch R = 1 ,6334.2  ,137.1,135.5,134
XS GIS Cut Line= 4
      1880378.36       221139.91     1879752.481      221954.905
     1879382.235      222913.874     1879428.077      223276.522
#Sta/Elev= 30
       0 1783.06    29.9 1772.86   119.7  1713.4   139.7 1706.83   239.4 1632.28
   325.4 1608.71   339.2 1607.64   340.4 1607.97   369.1 1614.93   648.5 1614.52
   748.2 1623.89   917.8  1694.7  1057.5 1743.31  1207.2  1760.5    1327 1810.11
  1386.9    1820  1456.7  1810.7  1486.7 1819.39  1646.4 1807.62  1686.3 1811.72
  1716.2 1807.94  1786.1 1787.03    1846 1757.45  1935.8 1754.09  1975.7 1739.82
  1995.7 1741.77  2075.3 1705.95  2243.3 1653.72  2361.8 1637.11  2421.1 1634.91
#Mann= 3 , 0 , 0
       0     .08       0   325.4    .045       0   340.4     .08       0
Bank Sta=325.4,340.4
XS Rating Curve= 0 ,0
Exp/Cntr=0.3,0.1

Type RM Length L Ch R = 1 ,6198.6  ,302.3,300,297.4
XS GIS Cut Line= 3
     1880362.853      220875.391     1880061.552       221330.73
     1879760.251      221786.069
#Sta/Elev= 30
       0 1937.75    29.8 1912.84    39.7 1909.32    89.4  1877.2    99.3 1871.85
   109.2 1869.93   158.8 1849.38   208.5 1817.58   218.4 1815.45     278 1772.85
   307.8 1747.98   317.7 1742.57   327.6 1739.98   436.8 1658.26   446.7 1655.56
   486.4 1627.29   516.2 1612.98   538.5  1608.1     546 1607.36   553.5 1607.38
   565.8 1609.09   575.8 1613.87   585.7  1615.8     814 1613.84   843.8 1614.99
   913.3  1621.9   933.2 1626.81  1002.6 1657.14  1012.6 1659.37    1092 1692.14
#Mann= 3 , 0 , 0
       0     .08       0   538.5    .045       0   553.5     .08       0
Bank Sta=538.5,553.5
XS Rating Curve= 0 ,0
Exp/Cntr=0.3,0.1

Type RM Length L Ch R = 1 ,5898.6  ,298.5,300,301.8
XS GIS Cut Line= 3
     1880049.859      220705.641     1879797.126      221189.691
     1879550.809      221676.962
#Sta/Elev= 30
       0 1845.75    39.7  1818.7    49.6 1814.47    59.6  1812.9   148.9  1775.4
   158.8 1774.04   198.6 1756.25   218.4 1745.53   228.4 1743.92   268.1 1728.51
   287.9 1723.76   327.6 1708.31   377.3 1683.96   387.2 1681.04   476.6 1632.92
   486.5 1631.99   538.6 1607.22   546.1    1606   553.6 1607.24   575.8 1613.06
   764.4 1615.29   853.8 1622.21   863.7  1626.5   883.6 1639.66   903.4 1649.89
   913.4 1651.67   972.9 1681.12  1022.6  1698.4  1052.3 1715.97    1092  1734.8
#Mann= 3 , 0 , 0
       0     .08       0   538.6    .045       0   553.6     .08       0
Bank Sta=538.6,553.6
XS Rating Curve= 0 ,0
Exp/Cntr=0.3,0.1

Type RM Length L Ch R = 1 ,5598.6  ,303.3,300,296.7
XS GIS Cut Line= 3
     1879823.746      220569.433     1879539.704      221035.734
     1879255.663      221502.035
#Sta/Elev= 30
       0 1905.86    59.6 1875.05    89.4 1856.51   109.2 1849.79     139  1829.2
   208.5 1807.21   228.3 1793.42   297.8 1752.59   317.7 1745.71   337.5 1733.92
   357.4 1720.28   377.2  1702.5   397.1 1694.22   426.9 1672.37   446.7 1664.42
   526.2 1609.69   538.5  1605.5     546  1605.3   553.5  1605.5   595.6 1612.08
     685 1612.87   804.1  1621.2   833.9 1633.33   853.8 1635.37   873.6 1646.89
   893.4 1668.21   913.3 1675.74     953 1695.95   972.9 1709.57    1092 1754.98
#Mann= 3 , 0 , 0
       0     .08       0   538.5    .045       0   553.5     .08       0
Bank Sta=538.5,553.5
XS Rating Curve= 0 ,0
Exp/Cntr=0.3,0.1

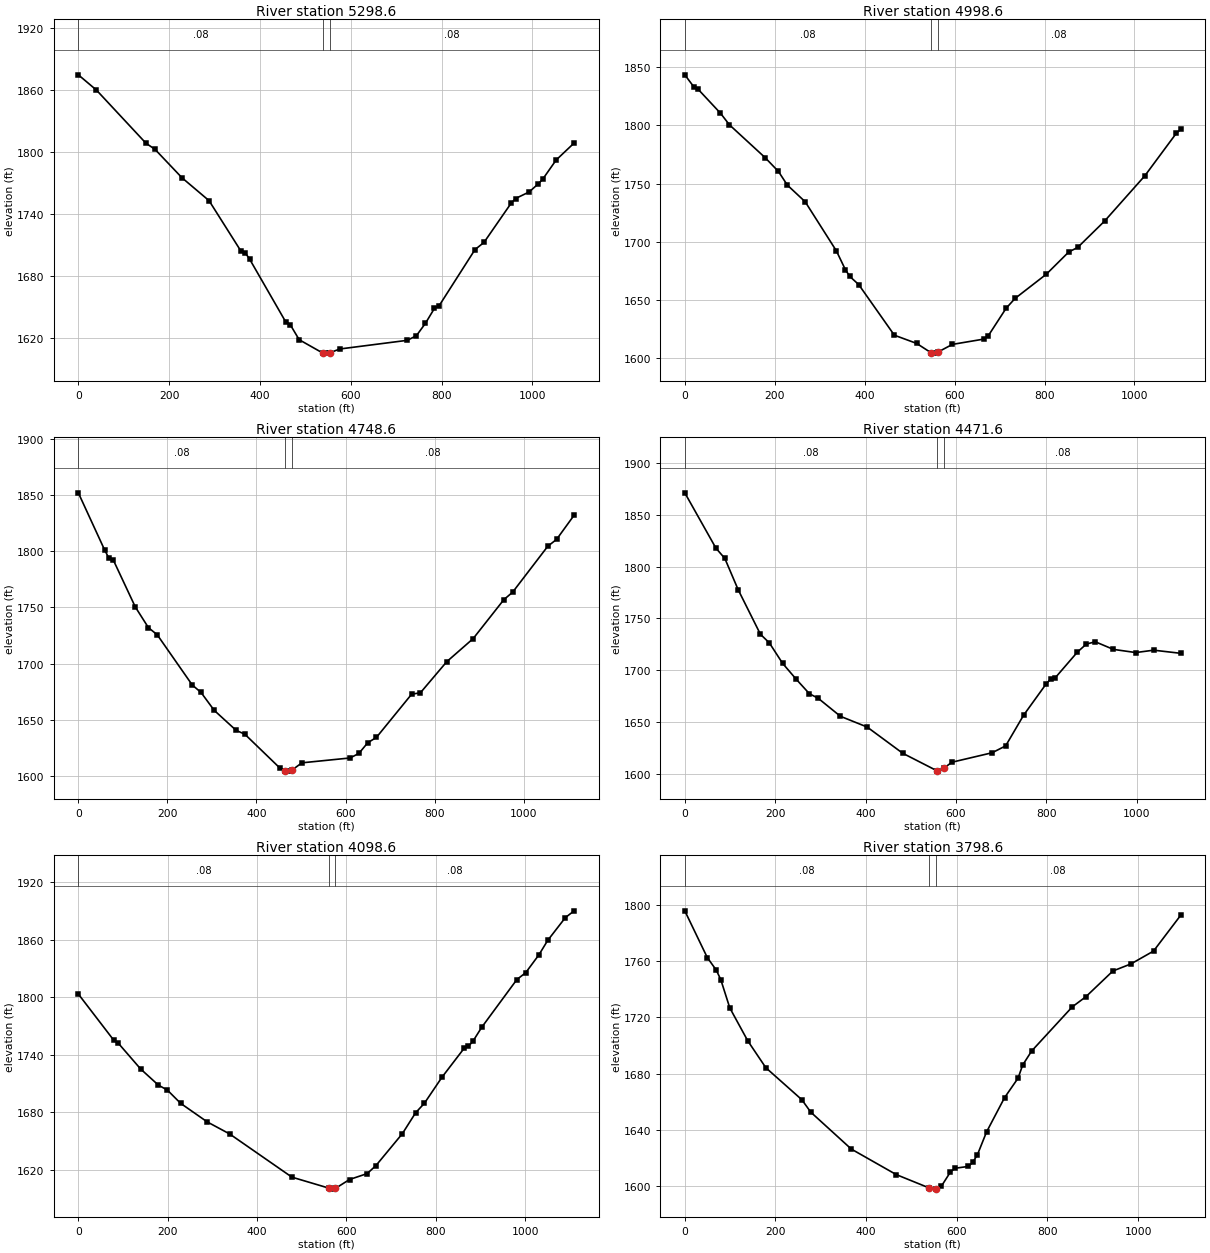
Type RM Length L Ch R = 1 ,5298.6  ,293.9,300,305.7
XS GIS Cut Line= 3
     1879485.231       220396.68     1879272.873      220899.691
     1879060.516      221402.702
#Sta/Elev= 30
       0 1874.93    39.7 1860.23   148.9 1808.68   168.8 1802.76   228.3 1775.19
   287.9 1753.02   357.4 1704.65   367.3 1702.68   377.2  1696.4   456.6 1635.67
   466.6 1632.95   486.4  1618.3   538.5 1605.35     546  1605.3   553.5 1605.58
   575.8 1609.31   724.7 1617.72   744.6 1622.21   764.4 1634.16   784.2 1648.61
   794.2 1650.93   873.6 1705.61   893.4 1712.56     953 1750.43     963 1755.11
   992.7  1761.4  1012.6 1769.16  1022.5 1773.66  1052.3 1792.38    1092 1808.89
#Mann= 3 , 0 , 0
       0     .08       0   538.5    .045       0   553.5     .08       0
Bank Sta=538.5,553.5
XS Rating Curve= 0 ,0
Exp/Cntr=0.3,0.1

Type RM Length L Ch R = 1 ,4998.6  ,260.2,250,240.2
XS GIS Cut Line= 3
     1879348.168      220333.586     1879005.057      220770.193
     1878673.184      221205.409
#Sta/Elev= 30
       0  1843.3    19.8 1833.12    29.8 1830.84    79.3 1810.38    99.2 1800.43
   178.5 1772.29   208.2 1760.41   228.1 1748.66   267.7  1734.4   337.1 1692.24
     357  1676.2   366.9 1670.32   386.7 1663.36     466  1619.9   515.6 1612.85
   547.8 1604.82   555.3 1604.52   562.8  1605.4   595.1 1612.02   664.8 1616.55
   674.7 1619.31   714.5 1642.99   734.4 1651.44   804.1 1672.28   853.8  1691.3
   873.7  1695.2   933.4 1717.77    1023 1756.66  1092.7 1792.99  1102.6 1796.59
#Mann= 3 , 0 , 0
       0     .08       0   547.8    .045       0   562.8     .08       0
Bank Sta=547.8,562.8
XS Rating Curve= 0 ,0
Exp/Cntr=0.3,0.1

Type RM Length L Ch R = 1 ,4748.6  ,271,277,284
XS GIS Cut Line= 3
     1878910.321      220171.091     1878787.445      220698.078
     1878627.942        221247.5
#Sta/Elev= 30
       0 1851.96      59 1801.17    68.9 1793.64    78.7 1792.05   127.9 1750.46
   157.4 1732.03   177.1 1725.73   255.8 1681.04   275.5 1674.41     305 1658.52
   354.2 1640.73   373.9 1637.25   452.6 1607.15   464.7 1604.58   472.2 1604.44
   479.7 1605.35   501.8 1611.82   610.2 1616.15   629.9  1620.2   649.6 1629.62
   669.4  1634.5   748.3 1672.86     768 1674.12   827.2 1701.79   886.4 1722.28
   955.4 1756.97   975.1  1763.6    1054 1804.44  1073.8 1810.57  1113.2 1832.11
#Mann= 3 , 0 , 0
       0     .08       0   464.7    .045       0   479.7     .08       0
Bank Sta=464.7,479.7
XS Rating Curve= 0 ,0
Exp/Cntr=0.3,0.1

Type RM Length L Ch R = 1 ,4471.6  ,370.1,372.9,373.8
XS GIS Cut Line= 3
     1878761.805      220070.744     1878541.773      220576.005
     1878265.016      221046.632
#Sta/Elev= 30
       0 1871.05    68.9 1817.73    88.6 1807.84   118.1 1777.68   167.3 1734.81
     187 1726.52   216.5 1706.72     246 1691.72   275.6 1677.54   295.2  1673.1
   344.4 1655.74   403.5 1645.41   482.2 1620.15   559.1 1603.02     561 1602.93
   574.1    1606   590.8 1611.48   680.1 1620.65   709.9 1627.24   749.6 1656.76
   799.3 1686.78   809.2 1691.58   819.1 1692.58   868.8 1717.66   888.6 1725.38
   908.4 1727.53   948.2 1720.23   997.8 1717.16  1037.5 1719.45  1097.1 1716.45
#Mann= 3 , 0 , 0
       0     .08       0   559.1    .045       0   574.1     .08       0
Bank Sta=559.1,574.1
XS Rating Curve= 0 ,0
Exp/Cntr=0.3,0.1

Type RM Length L Ch R = 1 ,4098.6  ,291.5,300,308.4
XS GIS Cut Line= 3
     1878525.215      219974.533     1878196.205      220437.172
     1877903.044      220893.248
#Sta/Elev= 30
       0 1803.42    79.7    1755    89.6 1752.05   139.4 1725.27   179.3 1708.37
   199.2 1703.28   229.1 1689.38   288.8 1669.97   338.6 1657.51   478.1 1612.41
   560.2 1601.05   567.7 1599.92   575.2  1600.6   607.1 1609.96   646.6 1616.13
   666.3 1624.54   725.4 1657.82     755 1679.57   774.7 1689.51   814.1  1716.7
   863.4 1746.71   873.3 1748.95   883.1 1754.02   902.9 1768.69   981.7 1818.57
  1001.4 1825.66    1031 1844.32  1050.7 1859.38  1090.2 1883.14  1109.9 1890.22
#Mann= 3 , 0 , 0
       0     .08       0   560.2    .045       0   575.2     .08       0
Bank Sta=560.2,575.2
XS Rating Curve= 0 ,0
Exp/Cntr=0.3,0.1

Type RM Length L Ch R = 1 ,3798.6  ,295.1,298,302
XS GIS Cut Line= 3
     1878466.828      219908.976     1878009.655      220207.803
     1877568.317      220532.294
#Sta/Elev= 30
       0 1795.62    49.6 1762.43    69.5 1753.45    79.4 1746.71    99.3 1726.61
     139 1703.19   178.8 1684.12   258.2 1661.39     278 1652.52   367.4  1626.3
   466.7 1608.14   538.7 1598.74   553.7 1597.83   566.1 1599.89     586 1609.96
     596 1612.66   625.8 1613.97   635.8 1617.11   645.8 1622.38   665.7 1638.41
   705.5 1662.83   735.4 1676.74   745.4 1685.97   765.3 1695.99   854.9 1727.36
   884.8 1734.53   944.6 1752.87   984.4 1757.89  1034.2 1767.01    1094 1792.39
#Mann= 3 , 0 , 0
       0     .08       0   538.7    .045       0   553.7     .08       0
Bank Sta=538.7,553.7
XS Rating Curve= 0 ,0
Exp/Cntr=0.3,0.1

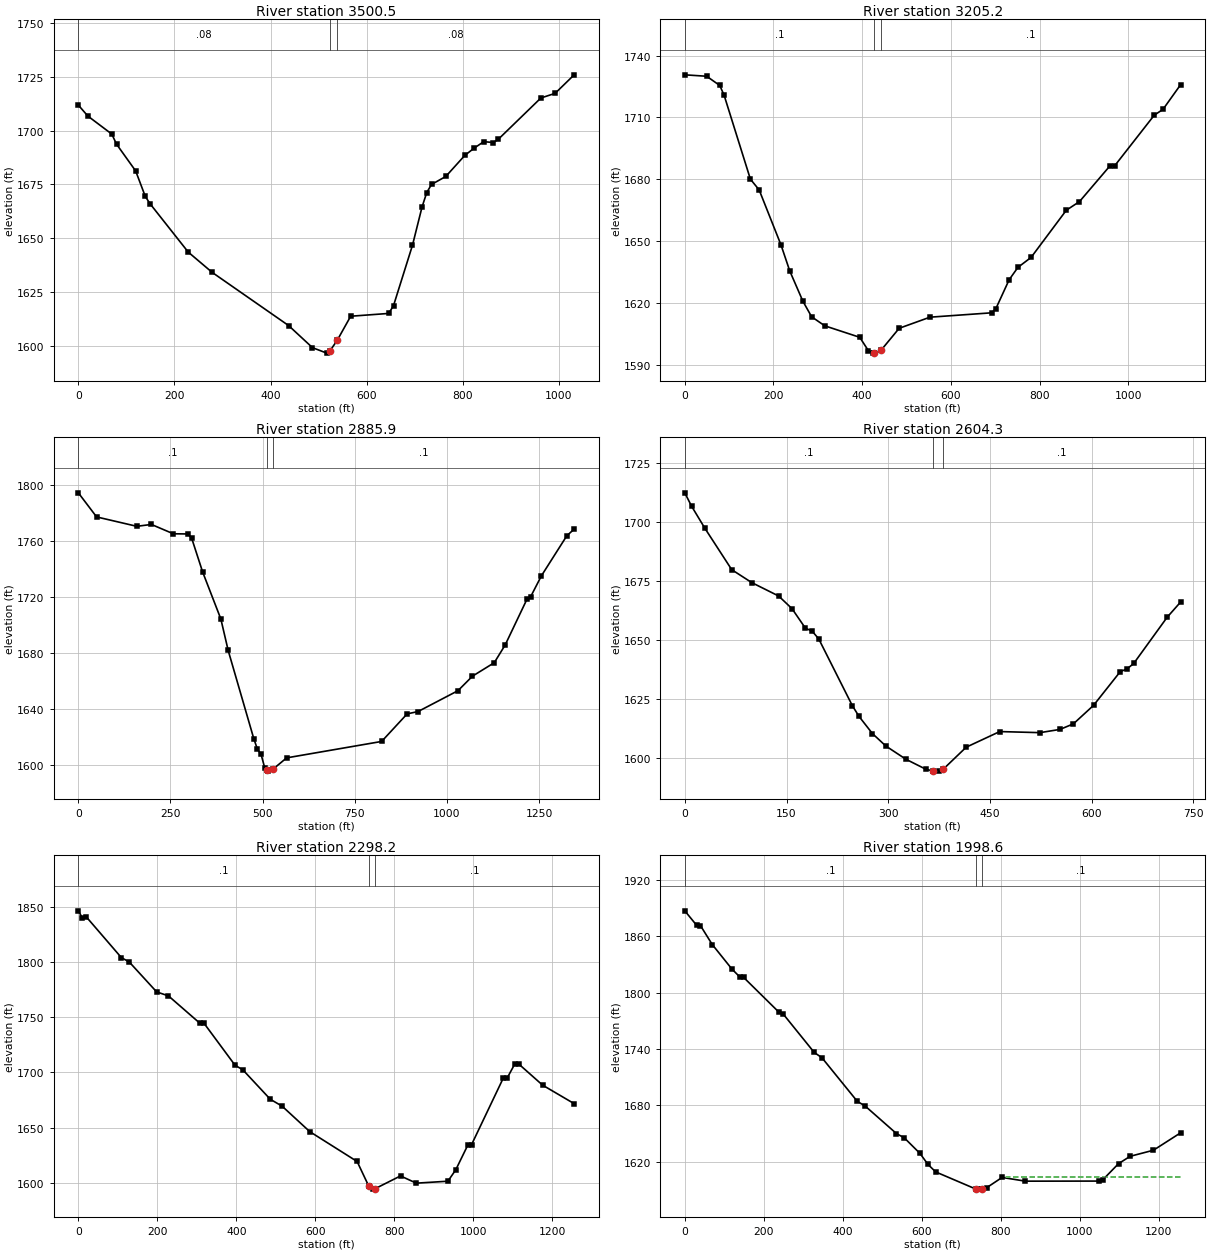
Type RM Length L Ch R = 1 ,3500.5  ,297.4,295.3,289.4
XS GIS Cut Line= 3
     1878348.491      219712.422      1877838.82      219960.195
     1877589.579      220352.753
#Sta/Elev= 30
       0 1711.85    19.9 1706.74    69.6 1698.39    79.5 1693.69   119.3 1681.26
   139.2 1669.49   149.1 1666.06   228.7 1643.56   278.4 1634.15   437.5 1609.44
   487.2 1599.17     517 1596.63   523.8 1597.74   538.8 1602.63   566.7 1613.77
   645.8 1615.07   655.8 1618.68   695.3 1646.76   715.1 1664.45     725 1671.24
   734.9 1674.98   764.6  1678.7   804.2 1688.48   823.9 1691.91   843.7 1694.87
   863.5 1694.45   873.4 1695.87   962.4 1715.14   992.1 1717.31  1031.7 1725.91
#Mann= 3 , 0 , 0
       0     .08       0   523.8    .045       0   538.8     .08       0
Bank Sta=523.8,538.8
XS Rating Curve= 0 ,0
Exp/Cntr=0.3,0.1

Type RM Length L Ch R = 1 ,3205.2  ,353.3,319.4,289.2
XS GIS Cut Line= 3
     1878095.476      219462.643     1877708.241      219699.036
     1877589.579      220352.753
#Sta/Elev= 30
       0 1730.68    49.3 1729.99    78.9 1725.52    88.8 1720.69   147.9 1680.11
   167.7 1674.88     217 1648.19   236.7  1635.6   266.3 1620.94     286  1613.4
   315.6 1609.02   394.5 1603.45   414.2 1596.91   424.1 1595.78   427.3 1595.82
   442.3 1597.12   483.4 1607.82   552.8  1613.2   691.7 1615.32   701.6  1617.4
   731.4 1631.35   751.2 1637.34   780.9 1642.18   860.3 1665.04     890 1669.23
   959.4 1686.72   969.3 1686.56  1058.6 1711.11  1078.4 1713.95  1118.1 1725.91
#Mann= 3 , 0 , 0
       0      .1       0   427.3    .045       0   442.3      .1       0
Bank Sta=427.3,442.3
XS Rating Curve= 0 ,0
Exp/Cntr=0.3,0.1

Type RM Length L Ch R = 1 ,2885.9  ,283,281.4,279.1
XS GIS Cut Line= 3
     1877249.132      219192.428      1877624.94      219957.943
      1877408.34      220400.385
#Sta/Elev= 30
       0 1794.26    49.6 1777.03   158.7 1770.32   198.3 1771.65   257.8 1764.98
   297.5 1764.85   307.4 1761.95   337.2 1737.74   386.7 1704.06   406.6 1681.56
     476 1618.57   485.9 1610.97   495.8 1607.34   505.7 1597.67   512.7 1595.98
   515.6 1595.28   527.7 1596.56   565.2 1604.76     823  1616.5   892.2 1636.21
   921.8 1637.88  1030.1 1652.79  1069.5 1663.18  1128.6  1672.8  1158.2 1685.48
  1217.3 1718.18  1227.2  1719.9  1256.7    1735  1325.7 1763.63  1345.4 1768.28
#Mann= 3 , 0 , 0
       0      .1       0   512.7    .045       0   527.7      .1       0
Bank Sta=512.7,527.7
XS Rating Curve= 0 ,0
Exp/Cntr=0.3,0.1

Type RM Length L Ch R = 1 ,2604.3  ,295.8,306.1,317
XS GIS Cut Line= 2
     1877093.618      219554.949     1877489.858      220169.572
#Sta/Elev= 30
       0 1712.29     9.9 1706.67    29.6 1697.28    69.2 1679.74    98.8 1674.25
   138.4 1668.58   158.1 1663.23   177.9 1654.94   187.8 1653.72   197.6 1650.38
     247 1622.18   256.9 1617.59   276.7 1610.31   296.5 1605.03   326.1 1599.43
   355.8 1595.15   366.5 1594.44   375.5 1594.39   381.5 1595.29     415 1604.52
   464.5 1611.15   523.8 1610.69   553.4 1612.06   573.2 1614.43   602.8 1622.23
   642.3 1636.55   652.2 1637.68   662.1 1639.99   711.5  1659.6   731.3 1666.03
#Mann= 3 , 0 , 0
       0      .1       0   366.5    .045       0   381.5      .1       0
Bank Sta=366.5,381.5
XS Rating Curve= 0 ,0
Exp/Cntr=0.3,0.1

Type RM Length L Ch R = 1 ,2298.2  ,288.6,299.8,317
XS GIS Cut Line= 3
     1877092.934      219216.362     1876983.301      219690.031
     1877060.693      220455.785
#Sta/Elev= 30
       0 1846.38     9.9 1840.15    19.8 1841.05   109.1 1803.96     129 1800.03
   198.4 1772.92   228.2 1769.34   307.6 1744.63   317.5 1744.93   396.9  1706.5
   416.7 1702.34   486.2 1675.68   516.2 1669.41   586.2 1646.36   706.1 1619.31
   735.5 1597.05   746.1 1594.28   750.5 1594.47     816 1606.24     856 1599.69
     936 1601.45     956 1611.82     986 1633.84     996 1634.61  1075.9 1694.58
  1085.9 1694.78  1105.9 1707.96  1115.9 1707.48  1175.9 1688.47  1255.8 1671.71
#Mann= 3 , 0 , 0
       0      .1       0   735.5    .045       0   750.5      .1       0
#XS Ineff= 2 , 0
                          816.02         1606.22
Permanent Ineff=
       F       F
Bank Sta=735.5,750.5
XS Rating Curve= 0 ,0
Exp/Cntr=0.3,0.1

Type RM Length L Ch R = 1 ,1998.6  ,432.4,436,433.7
XS GIS Cut Line= 3
     1877018.802       219198.84     1876729.604      219884.884
     1876413.933      220286.682
#Sta/Elev= 30
       0 1886.85    29.8 1871.55    39.7 1871.12    69.5 1851.04   119.1 1825.07
     139 1816.65   148.9  1816.1   238.2 1779.16   248.2 1777.64   327.6 1736.36
   347.4 1730.59   436.8  1684.3   456.6 1679.36     536 1650.01   555.9 1645.45
   595.6 1628.89   615.5 1617.36   635.3 1609.28     737 1591.05   744.5 1590.98
     752 1591.11   764.2 1592.45   803.5 1603.42   862.4 1599.45  1049.1 1599.54
    1059 1601.16  1098.3 1618.07  1127.7 1625.88  1186.7 1632.34  1255.5 1650.85
#Mann= 3 , 0 , 0
       0      .1       0     737    .045       0     752      .1       0
#XS Ineff= 2 , 0
                          813.35         1603.65
Permanent Ineff=
       F       F
Bank Sta=737,752
XS Rating Curve= 0 ,0
Exp/Cntr=0.3,0.1

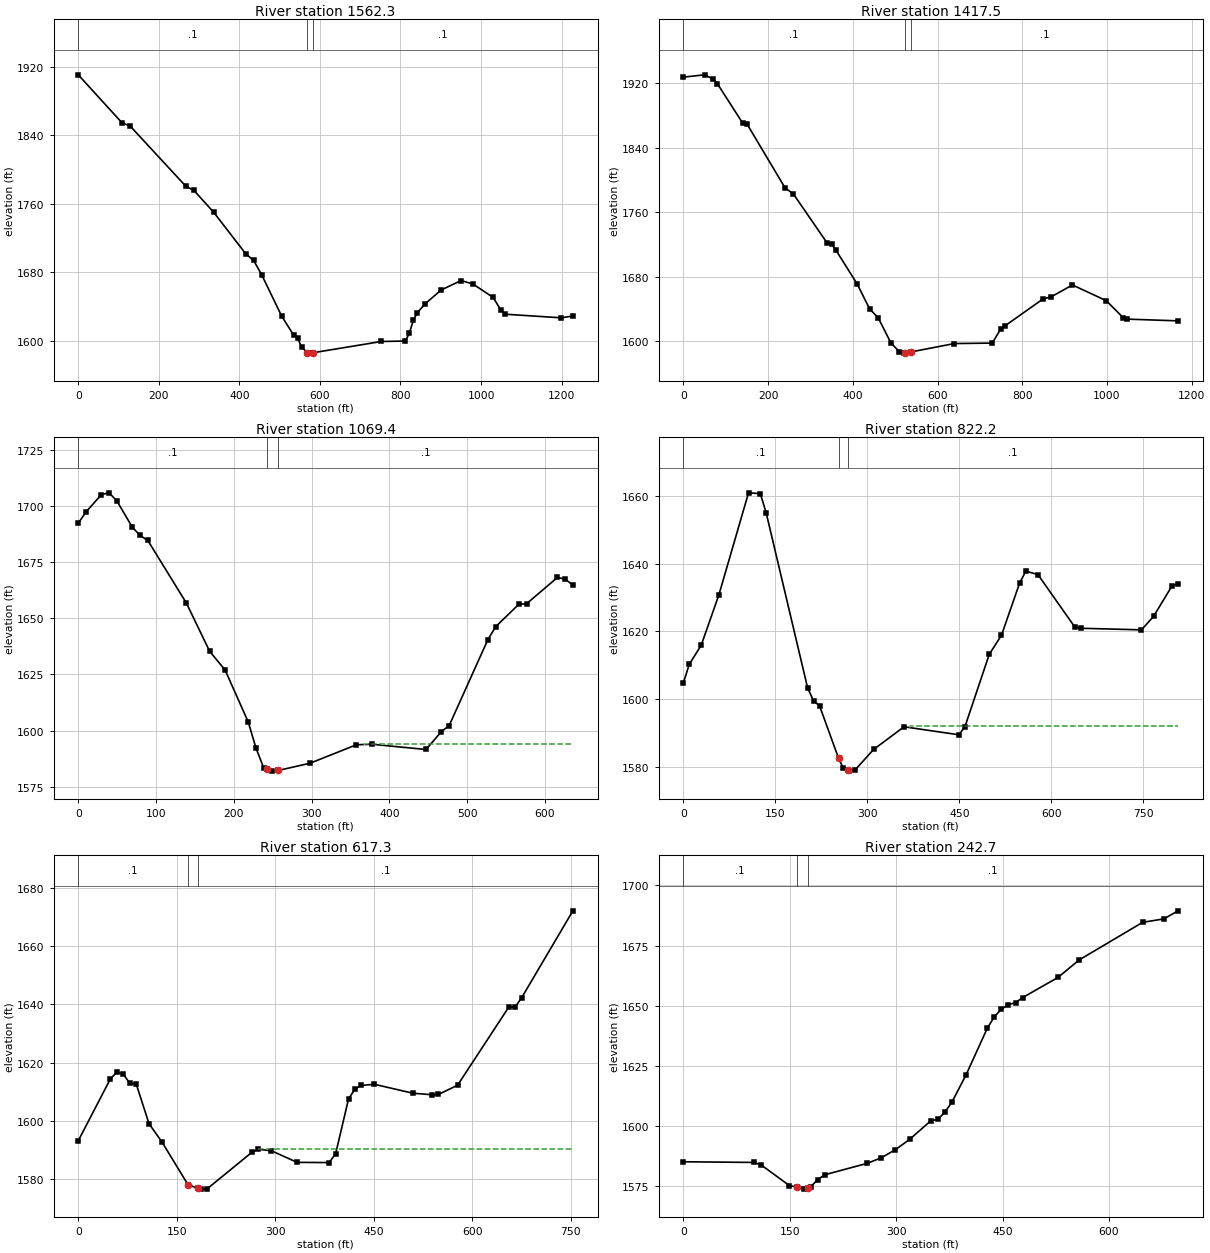
Type RM Length L Ch R = 1 ,1562.3  ,149.7,144.9,142.5
XS GIS Cut Line= 3
     1876972.954      219161.728     1876641.093      219395.102
     1876209.237      220094.984
#Sta/Elev= 30
       0 1910.37   108.8  1854.3   128.6 1850.76   267.2 1780.36     287  1775.7
   336.4 1750.01   415.6 1701.78   435.4 1693.93   455.2 1677.41   504.8 1629.21
   534.5 1606.96   544.4 1603.52   554.3 1593.18   568.6 1586.35   574.2 1585.83
   583.6 1586.34   752.5  1599.4     812 1599.92   821.9 1608.93   831.8 1623.97
   841.7 1632.93   861.5 1643.44   901.1 1659.47   950.7 1670.52   980.4 1666.28
  1029.9 1650.83  1049.8 1635.72  1059.7 1631.23  1198.4 1627.03  1228.1 1629.08
#Mann= 3 , 0 , 0
       0      .1       0   568.6    .045       0   583.6      .1       0
Bank Sta=568.6,583.6
XS Rating Curve= 0 ,0
Exp/Cntr=0.3,0.1

Type RM Length L Ch R = 1 ,1417.5  ,360.3,348,333.1
XS GIS Cut Line= 3
     1876591.436      218984.082     1876418.159      219484.728
     1876141.998      220059.738
#Sta/Elev= 30
       0 1927.62      50 1930.47      70 1925.27      80 1919.64   139.9 1870.61
   149.9 1869.74   239.9 1790.44   259.9 1782.66   339.9 1721.53   349.9  1720.5
   359.8 1713.35   409.8 1671.67   439.8 1640.26   459.8  1629.4   489.8 1598.27
   509.8  1587.2   519.8 1585.54   522.3 1585.64   537.3 1587.03   639.4  1597.4
   729.1    1598   749.1 1615.37     759 1619.27   848.7 1652.57   868.7 1655.45
   918.5    1670   998.2  1650.6  1038.1 1629.57  1048.1 1627.68  1167.7 1625.54
#Mann= 3 , 0 , 0
       0      .1       0   522.3    .045       0   537.3      .1       0
Bank Sta=522.3,537.3
XS Rating Curve= 0 ,0
Exp/Cntr=0.3,0.1

Type RM Length L Ch R = 1 ,1069.4  ,247.1,247.2,247.5
XS GIS Cut Line= 2
     1876035.476      219221.747     1876159.301      219845.375
#Sta/Elev= 30
       0 1692.29     9.9 1697.26    29.8 1705.02    39.7 1705.79    49.7 1702.12
    69.5  1690.5    79.5 1686.82    89.4  1684.6   139.1 1656.69   168.9 1635.29
   188.8 1626.96   218.6 1603.77   228.5 1592.21   238.4 1583.45     242 1582.94
   248.4 1582.02     257 1582.32     298 1585.54   357.6 1593.75   377.5 1593.97
     447 1591.64   466.9 1599.63   476.8 1602.29   526.5 1640.49   536.5 1646.22
   566.3 1656.24   576.2 1656.43   615.9 1668.15   625.9  1667.4   635.8 1664.74
#Mann= 3 , 0 , 0
       0      .1       0     242    .045       0     257      .1       0
#XS Ineff= 2 , 0
                          367.63         1594.01
Permanent Ineff=
       F       F
Bank Sta=242,257
XS Rating Curve= 0 ,0
Exp/Cntr=0.3,0.1

Type RM Length L Ch R = 1 ,822.2   ,204.4,204.9,205
XS GIS Cut Line= 3
      1875794.58      219271.277     1875844.705      219526.963
     1875943.487      220063.953
#Sta/Elev= 30
       0 1604.78     9.6 1610.26      29 1615.87    57.9  1630.8   106.2 1660.94
   125.4 1660.71   135.1 1654.93   202.6 1603.22   212.3 1599.44     222 1597.97
   253.1 1582.44   260.6 1579.58   268.1 1578.88   270.5 1578.66   280.4  1579.1
   310.2 1585.07   359.8 1591.77   449.2 1589.41   459.1 1591.79   498.8  1613.2
   518.7 1618.84   548.4 1634.31   558.4 1637.79   578.2 1636.76   637.8 1621.39
   647.7  1620.9     747 1620.43   766.8 1624.43   796.6 1633.37   806.6 1634.04
#Mann= 3 , 0 , 0
       0      .1       0   253.1    .045       0   268.1      .1       0
#XS Ineff= 2 , 0
                          369.76         1591.92
Permanent Ineff=
       F       F
Bank Sta=253.1,268.1
XS Rating Curve= 0 ,0
Exp/Cntr=0.3,0.1

Type RM Length L Ch R = 1 ,617.3   ,378.7,374.5,370.3
XS GIS Cut Line= 3
     1875614.471      219399.605     1875691.017      219834.118
     1875740.547      220142.555
#Sta/Elev= 30
       0 1593.21      49 1614.47    58.8  1616.7    68.6 1616.08    78.4 1612.93
    88.2 1612.74   107.8 1599.06   127.5  1592.8   167.2 1578.13   182.2 1576.89
   186.3 1576.62   196.1 1576.68   264.7 1589.28   274.5 1590.26   294.1  1589.8
   333.4  1585.8   382.4 1585.73   392.2 1588.83   411.8 1607.58   421.6 1610.97
   431.4 1612.19     451 1612.59   509.5 1609.53   538.8 1608.99   548.6 1609.08
   577.9 1612.26     656 1639.08   665.7 1639.11   675.5 1642.26   753.6 1672.08
#Mann= 3 , 0 , 0
       0      .1       0   167.2    .045       0   182.2      .1       0
#XS Ineff= 2 , 0
                          274.56         1590.31
Permanent Ineff=
       F       F
Bank Sta=167.2,182.2
XS Rating Curve= 0 ,0
Exp/Cntr=0.3,0.1

Type RM Length L Ch R = 1 ,242.7   ,211.5,242.7,274
XS GIS Cut Line= 2
     1875227.236      219518.927     1875472.859      220171.683
#Sta/Elev= 30
       0 1585.07    99.6 1584.79   109.6 1583.75   149.4 1575.18   160.2 1574.58
   169.4 1573.69   175.2 1574.22   179.3  1574.6   189.3 1577.66   199.3 1579.66
     259  1584.4     279 1586.72   298.9 1590.09   318.8 1594.35   348.7 1602.09
   358.7  1602.7   368.6 1605.65   378.6 1609.88   398.5 1621.19   428.4 1640.55
   438.4  1645.4   448.4 1648.53   458.3 1650.42   468.3 1651.23   478.2 1653.33
   528.1 1661.72     558    1669   647.6 1684.66   677.5 1686.07   697.4 1689.43
#Mann= 3 , 0 , 0
       0      .1       0   160.2    .045       0   175.2      .1       0
Bank Sta=160.2,175.2
XS Rating Curve= 0 ,0
Exp/Cntr=0.3,0.1

Chan Stop Cuts=-1
Use User Specified Reach Order=0
Composite Channel Slope=5